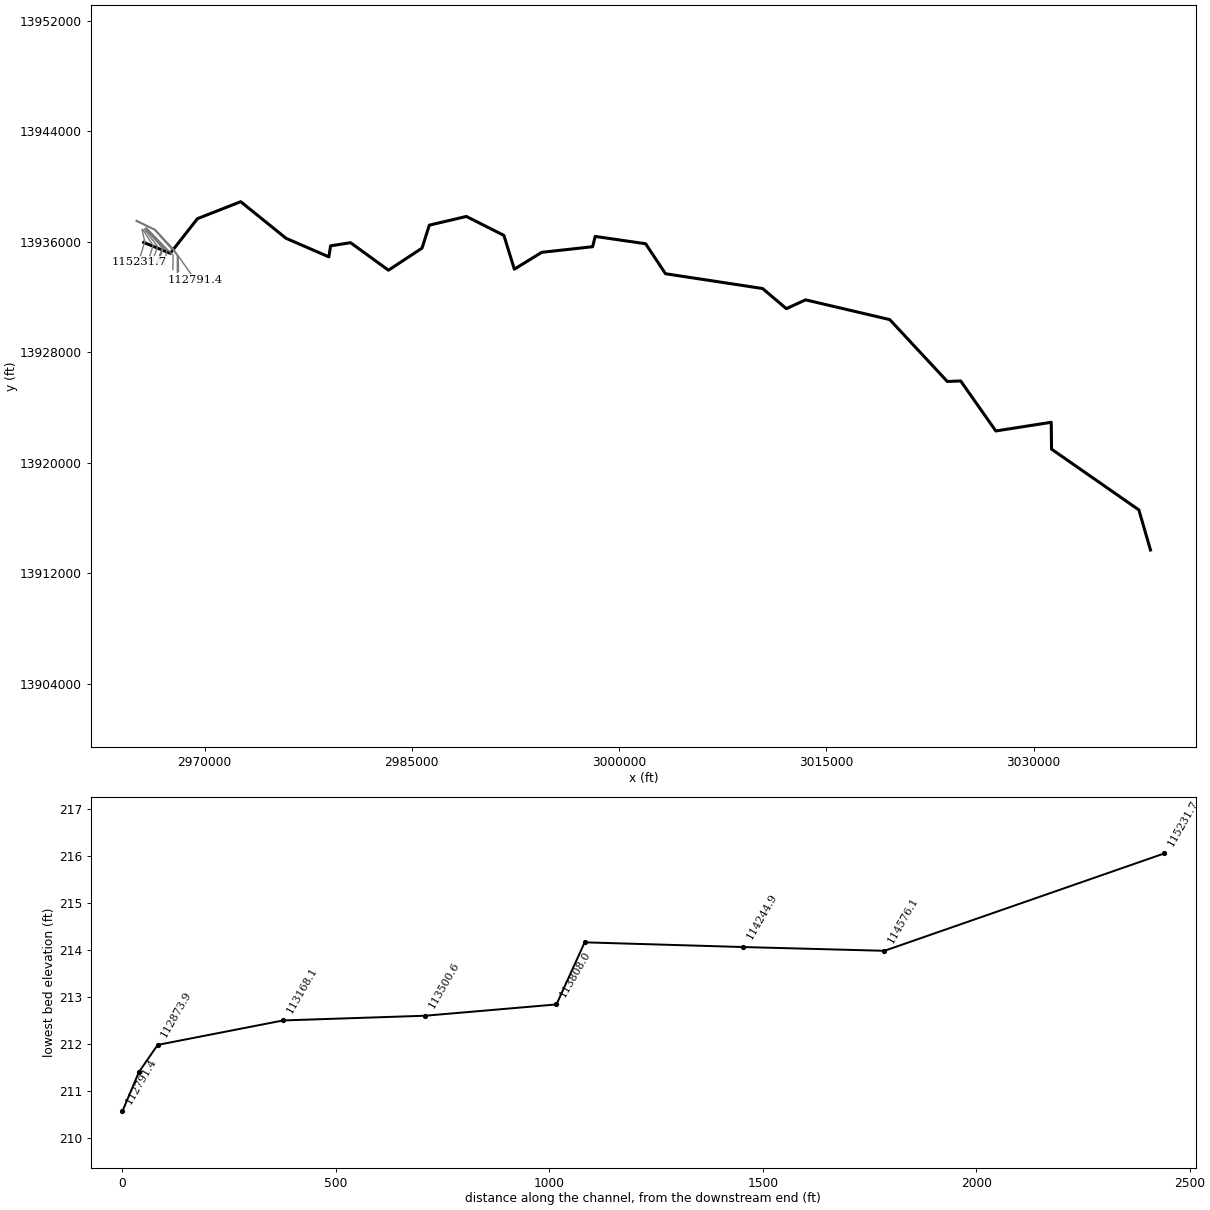
--- L100-00-00.prj (project) ---

Proj Title=L100-00-00
Current Plan=p01
Default Exp/Contr=.3,.1
English Units
Geom File=g01
Flow File=f01
Flow File=f02
Plan File=p01
Plan File=p02
Y Axis Title=Elevation
X Axis Title(PF)=Main Channel Distance
X Axis Title(XS)=Station
BEGIN DESCRIPTION:
HCFCD MODEL SUMMARY METADATA
The purpose of this summary is to document the high points of hydrologic and hydraulic models filed within the HCFCD Model and Map Management (M3) system.  The document includes references to the project that prompted the creation or update of the model.
DESCRIPTION OF PROJECT:
The following model was the hydraulic model which represented the effective condition of Harris County’s watersheds.
PURPOSE OF PROJECT:
Development of effective models to support the National Flood Insurance Program.
HCFCD Watershed Unit ID: L
M3 Study Identifier: 2007_Effective_L
Engineer: HCFCD
Project Name: EffectiveFEMA Study for watershed Little Cypress Creek (L)
Study Completion Date: 6/18/2007
FEMA Case Number: [No Data]
FEMA Approval Date: [No Date in Database]
Vertical Datum: NAVD 1988
Datum Note: 2001 ADJ
HYDRAULICS
HCFCD Unit No.:  L100-00-00
Hydraulic Program Name: HEC-RAS
Hydraulic Program Version: 3.0.1
Steady Hydraulic Model: Yes
Unsteady Hydraulic Model: No
Update1: The effective FEMA hydraulic model for unit number L100-00-00 has been updated by FEMA LOMR 12-06-2602P with an effective date of 5/31/2013.
Update2: The effective FEMA hydraulic model for unit number L100-00-00 has been updated by FEMA LOMR 14-06-1335P with an effective date of 7/03/2014.
Update3: The effective FEMA hydraulic model for unit number L100-00-00 has been updated by FEMA LOMR 16-06-3975P with an effective date of 04/14/2017.
Update4: The effective FEMA hydraulic model for unit number L100-00-00 has been updated by FEMA LOMR 16-06-1650P with an effective date of 04/28/2017.
Update5: The effective FEMA hydraulic model for unit number L100-00-00 has been updated by FEMA LOMR 16-06-0884P with an effective date of 10/02/2017.
END DESCRIPTION:
DSS Export Rating Curves= 0
DSS Export Rating Curve Sorted= 0
DSS Export Volume Flow Curves= 0
DXF Filename=..\..\..\Superseded\20170309\HEC-RAS_301\L100-00-00\115231.7.dxf
DXF OffsetX= 0
DXF OffsetY= 0
DXF ScaleX= 1
DXF ScaleY= 10

--- L100-00-00.p01 (plan) ---

Plan Title=FEMA Effective Multi-Profile 2017
Program Version=4.10
Short Identifier=Eff+LOMR_MP
Geom File=g01
Flow File=f01
Subcritical Flow
K Sum by GR= 0
Std Step Tol= 0.01
Critical Tol= 0.01
Num of Std Step Trials= 20
Max Error Tol= 0.3
Flow Tol Ratio= 0.001
Split Flow NTrial= 30
Split Flow Tol= 0.02
Split Flow Ratio= 0.02
Log Output Level= 0
Friction Slope Method= 1
Unsteady Friction Slope Method= 2
Unsteady Bridges Friction Slope Method= 1
Parabolic Critical Depth
Global Vel Dist= 0 , 0 , 0
Global Log Level= 0
CheckData=True
Encroach Param=-1 ,0,0, 0
BEGIN DESCRIPTION:
FEMA Effective June 2007 + LOMR 12-06-2602P + LOMR 14-06-1335P + LOMR 17-06-0884P
END DESCRIPTION:
Computation Interval=1HOUR
Output Interval=1HOUR
Run HTab= 0
Run UNet= 0
Run PostProcess= 0
Run WQNet= 0
UNET Theta= 1
UNET Theta Warmup= 1
UNET ZTol= 0.02
UNET ZSATol= 0.05
UNET MxIter= 20
UNET MaxInSteps= 0
UNET DtIC= 0
UNET DtMin= 0
UNET MaxCRTS= 20
UNET WFStab= 2
UNET SFStab= 1
UNET WFX= 1
UNET SFX= 1
UNET DSS MLevel= 4
UNET DZMax Abort= 100
UNET Convert EG Bridges= 0
UNET Use Existing IB Tables=-1
UNET Froude Reduction=False
UNET Froude Limit= 1
UNET Froude Power= 10
UNET Time Slicing=0,0, 5
UNET Junction Losses=0
Instantaneous Interval=1HOUR
Write IC File= 0
IC Time=0,,
Write IC File at Sim End=0
Echo Input=False
Echo Parameters=False
Echo Output=False
Write Detailed= 0
WQ AD Non Conservative
WQ ULTIMATE=-1
WQ Max Comp Step=1HOUR
WQ Output Interval=15MIN
WQ Output Selected Increments= 0
WQ Output face flow=0
WQ Output face velocity=0
WQ Output face area=0
WQ Output face dispersion=0
WQ Output cell volume=0
WQ Output cell surface area=0
WQ Output cell continuity=0
WQ Output cumulative cell continuity=0
WQ Output face conc=0
WQ Output face dconc_dx=0
WQ Output face courant=0
WQ Output face peclet=0
WQ Output face adv mass=0
WQ Output face disp mass=0
WQ Output cell mass=0
WQ Output cell source sink temp=0
WQ Output cell source sink nsm=0
WQ Output MaxMinRange=-1
WQ Daily Max Min Mean=-1
WQ Daily Range=0
WQ Daily Time=0
WQ Create Restart=0
WQ Fixed Restart=0
WQ System Summary=0
WQ Use Fixed Temperature=0
Sorting and Armoring Iterations= 10
XS Update Threshold= 0.02
Hydraulics Update Threshold= 0.02
Energy Slope Method= 1
Volume Change Method= 0
XS Weighting Method= 0
Number of US Weighted Cross Sections= 1
Number of DS Weighted Cross Sections= 1
Upstream XS Weight=0.25
Main XS Weight=0.5
Downstream XS Weight=0.25
Number of DS XS's Weighted with US Boundary= 1
Upstream Boundary Weight= 1
Weight of XSs Associated with US Boundary= 0
Number of US XS's Weighted with DS Boundary= 1
Downstream Boundary Weight= 0.5
Weight of XSs Associated with DS Boundary= 0.5
Sediment Output Level= 4
Mass or Volume Output= 0
Output Increment Type= 1
Profile and TS Output Increment= 10
XS Output Flag= 0
XS Output Increment= 10
Disregard all LS=0
Disregard all Conn=0
Disregard all Breaches=0
Disregard all Pumps=0

--- L100-00-00.p02 (plan) ---

Plan Title=FEMA Effective Floodway 2017
Program Version=4.10
Short Identifier=Eff+LOMR_FW
Geom File=g01
Flow File=f02
Subcritical Flow
K Sum by GR= 0
Std Step Tol= 0.01
Critical Tol= 0.01
Num of Std Step Trials= 20
Max Error Tol= 0.3
Flow Tol Ratio= 0.001
Split Flow NTrial= 30
Split Flow Tol= 0.02
Split Flow Ratio= 0.02
Log Output Level= 0
Friction Slope Method= 1
Unsteady Friction Slope Method= 2
Unsteady Bridges Friction Slope Method= 1
Parabolic Critical Depth
Global Vel Dist= 0 , 0 , 0
Global Log Level= 0
CheckData=True
Encroach Param=-1 ,0,0, 2
Encroach River=L100-00-00
Encroach Reach=L100-00-00_0013
Encroach Node=115231.7
       1    4815    5135
Encroach Node=114576.1
       1    4684    5137
Encroach Node=114244.9
       1    4684    5137
Encroach Node=113874.0
       1    4647    5131
Encroach Node=113841.0
       1    4697    5131
Encroach Node=113808.0
       1    4697    5131
Encroach Node=113500.6
       1    4548    5100
Encroach Node=113168.1
       1    4427    5166
Encroach Node=112873.9
       1    4765    5172
Encroach Node=112851.9
       1    4813    5176
Encroach Node=112829.9
       1    4860    5182
Encroach Node=112791.4
       1    4936    5200
Encroach Node=112531.4
       1    4936    5200
Encroach Node=112271.4
       1    4936    5200
Encroach Node=112091.0
       1    4872    5336
Encroach Node=111753.7
       1    4870    5284
Encroach Node=111127.2
       1    4860    5054
Encroach Node=109779.9
       1    4940    5645
Encroach Node=108780.6
       1    4423    5346
Encroach Node=107635.9
       1    4439    5175
Encroach Node=106065.8
       1    4871    5441
Encroach Node=104700.3
       1    4380    5094
Encroach Node=104254.5
       1    4257    5140
Encroach Node=103292.2
       1    4195    5792
Encroach Node=103235.5
       1    4271    5705
Encroach Node=103203.5
       1    4290    5608
Encroach Node=103171.5
       1    4308    5510
Encroach Node=102990.5
       1    4343    5307
Encroach Node=101479.0
       1    4452    5279
Encroach Node=100630.4
       1    4725    5338
Encroach Node=99719.3
       1    4475    5111
Encroach Node=99213.1
       1    4560    5246
Encroach Node=98957.5
       1    4546    5247
Encroach Node=98856
       1    4560    5302
Encroach Node=98824.5
       1    4560    5302
Encroach Node=98793
       1    4560    5302
Encroach Node=98425.4
       1    4759    5564
Encroach Node=97585.0
       1    4508    5230
Encroach Node=96799.1
       1    4395    5073
Encroach Node=96629.4
       1    4377    5086
Encroach Node=95662.1
       1    4807    5675
Encroach Node=94013.2
       1    4917    6305
Encroach Node=93301.9
       1    4733    6146
Encroach Node=91677.9
       1    4259    5485
Encroach Node=91390.6
       1    4551    5400
Encroach Node=91366.6
       1    4331    5400
Encroach Node=91342.6
       1    4551    5400
Encroach Node=90841.5
       1    4464    5512
Encroach Node=90003.9
       1    4766    5675
Encroach Node=88589.8
       1    4879    5199
Encroach Node=86973.6
       1    4592    5156
Encroach Node=85719.3
       1    4777    5439
Encroach Node=84555.7
       1    4930    5586
Encroach Node=84132.0
       1    4604    5363
Encroach Node=83109.9
       1    4831    5842
Encroach Node=82298.4
       1    4900    6167
Encroach Node=81903.8
       1    4689    6050
Encroach Node=81626.4
       1    4568    5600
Encroach Node=81556.3
       1    4568    5435
Encroach Node=81532.8
       1    4568    5420
Encroach Node=81509.3
       1    4568    5405
Encroach Node=81307.7
       1    4409    5202
Encroach Node=80718.0
       1    4334    5208
Encroach Node=78110.5
       1    4576    5860
Encroach Node=77617.6
       1    4222    5493
Encroach Node=75631.5
       1    4221    5235
Encroach Node=74479.9
       1    4526    5332
Encroach Node=73225.6
       1    4547    5351
Encroach Node=71648.4
       1    4105    5175
Encroach Node=70258.2
       1    4350    5237
Encroach Node=68627.3
       1    4867    5330
Encroach Node=67931.8
       1    4589    5206
Encroach Node=66940.0
       1    4765    5726
Encroach Node=66026.7
       1    4373    5300
Encroach Node=65223.5
       1    4524    5130
Encroach Node=63590.0
       1    4514    5428
Encroach Node=63041.7
       1    4613    5203
Encroach Node=61906.7
       1    3793    5218
Encroach Node=60219.9
       1    4081    5182
Encroach Node=59633.4
       1    4394    5558
Encroach Node=58155.1
       1    4562    5838
Encroach Node=56802.3
       1    4325    5600
Encroach Node=55570.1
       1    4291    5613
Encroach Node=54861.7
       1    4683    6345
Encroach Node=54327.6
       1    4634    6432
Encroach Node=53948
       1    4879    6406
Encroach Node=53878
       1    4879    6007
Encroach Node=53848
       1    4879    6385
Encroach Node=53736.9
       1    4876    6309
Encroach Node=53547.5
       1    4851    6136
Encroach Node=51947.2
       1    4842    5935
Encroach Node=51047.3
       1    4696    5444
Encroach Node=49256.9
       1    3963    5164
Encroach Node=48304.3
       1    4073    5100
Encroach Node=47154.7
       1    3757    5263
Encroach Node=46345.6
       1    4443    6275
Encroach Node=45538.4
       1    4223    5962
Encroach Node=44470.6
       1    3963    5852
Encroach Node=43144.3
       1    3099    5092
Encroach Node=41600.8
       1    3213    5085
Encroach Node=41282.3
       1    3340    5287
Encroach Node=40766.4
       1    3730    5652
Encroach Node=40737.1
       1    3705    5642
Encroach Node=40713.6
       1    3680    5632
Encroach Node=40408.9
       1    3665    5400
Encroach Node=39390.5
       1    3922    5299
Encroach Node=38375.8
       1    4076    5490
Encroach Node=36687.4
       1    4133    5600
Encroach Node=36388.7
       1    4118    5715
Encroach Node=36370.7
       1    4118    5715
Encroach Node=36352.7
       1    4118    5715
Encroach Node=36149.4
       1    4100    5800
Encroach Node=35828.4
       1    3807    5677
Encroach Node=35138.1
       1    3525    5640
Encroach Node=34834.6
       1    3320    5445
Encroach Node=33738.3
       1    3890    5550
Encroach Node=33396.7
       1    3830    5540
Encroach Node=32244.7
       1    3950    5674
Encroach Node=31349.8
       1    3705    5827
Encroach Node=30322.9
       1    3441    5730
Encroach Node=29256.0
       1    3837    5575
Encroach Node=28216.5
       1    4015    5445
Encroach Node=27560.8
       1    4213    5145
Encroach Node=26938.5
       1    3900    5138
Encroach Node=25770.7
       1    4438    5985
Encroach Node=25381.2
       1    4262    5596
Encroach Node=24316.2
       1    3936    5393
Encroach Node=23254.4
       1    4142    5405
Encroach Node=22696.6
       1    4307    5637
Encroach Node=21449.3
       1    3659    5240
Encroach Node=20847.2
       1    4063    5642
Encroach Node=20009.6
       1    3663    5660
Encroach Node=19829.2
       1    3737    5623
Encroach Node=19797.2
       1    3769    5513
Encroach Node=19765.2
       1    3801    5654
Encroach Node=19461.1
       1    3980    5449
Encroach Node=19256.9
       1    4065    5437
Encroach Node=18628.5
       1    4408    5470
Encroach Node=18013.6
       1    4371    5463
Encroach Node=17532.1
       1    4629    5593
Encroach Node=16613.8
       1  4947.8    6072
Encroach Node=15684.8
       1    4860    6662
Encroach Node=15249.5
       1    4823    6607
Encroach Node=15234.5
       1    4810    6580
Encroach Node=15219.5
       1    4798    6552
Encroach Node=15137.7
       1    4764    6488
Encroach Node=14781.3
       1    4879    6528
Encroach Node=14285.5
       1    4846    6098
Encroach Node=13791.4
       1    4725    5763
Encroach Node=12691.0
       1  4428.3    5472
Encroach Node=12300.2
       1    4556    5643
Encroach Node=11996.9
       1    4435    5617
Encroach Node=11843.8
       1  4431.5    5710
Encroach Node=11809.8
       1  4431.5    5710
Encroach Node=11775.8
       1  4431.5    5710
Encroach Node=11150.2
       1    4412    5823
Encroach Node=10916.2
       1    4245    5665
Encroach Node=10637.3
       1    4109    5570
Encroach Node=10320.3
       1    4085    5635
Encroach Node=10107.5
       1    3955    5503
Encroach Node=9844.6
       1    3883    5427
Encroach Node=9229.5
       1    3386    5118
Encroach Node=8871.2
       1    3472    5144
Encroach Node=8067.1
       1    3800    5170
Encroach Node=7669.1
       1    4000    5190
Encroach Node=7604.1
       1    4030    5205
Encroach Node=7529.1
       1    4060    5220
Encroach Node=7350.4
       1    4200    5325
Encroach Node=6763.7
       1    4700    5504
Encroach Node=5874.5
       1    4350    5095
Encroach Node=5582.9
       1    4443    5152
Encroach Node=4930.1
       1    4325    5104
Encroach Node=4101.1
       1    4464    5511
Encroach Node=3777.8
       1    4470    5586
Encroach Node=2940.8
       1    4320    5485
Encroach Node=2124.2
       1    4066    5128
Encroach Node=1315.9
       1    4420    5410
BEGIN DESCRIPTION:
FEMA Effective June 2007 + LOMR 12-06-2602P + LOMR 14-06-1335P + LOMR 17-06-0884P
END DESCRIPTION:
Computation Interval=1HOUR
Output Interval=1HOUR
Run HTab= 0
Run UNet= 0
Run PostProcess= 0
Run WQNet= 0
UNET Theta= 1
UNET Theta Warmup= 1
UNET ZTol= 0.02
UNET ZSATol= 0.1
UNET MxIter= 20
UNET MaxInSteps= 20
UNET DtIC= 0
UNET DtMin= 0
UNET MaxCRTS= 20
UNET WFStab= 2
UNET SFStab= 1
UNET WFX= 1
UNET SFX= 1
UNET DSS MLevel= 4
UNET DZMax Abort= 100
UNET Convert EG Bridges=-1
UNET Use Existing IB Tables=-1
UNET Froude Reduction=False
UNET Froude Limit= 1
UNET Froude Power= 10
UNET Time Slicing=0,0, 5
UNET Junction Losses=0
Instantaneous Interval=1HOUR
Write IC File= 0
IC Time=0,,
Write IC File at Sim End=0
Echo Input=False
Echo Parameters=False
Echo Output=False
Write Detailed= 0
WQ AD Non Conservative
WQ ULTIMATE=-1
WQ Max Comp Step=1HOUR
WQ Output Interval=15MIN
WQ Output Selected Increments= 0
WQ Output face flow=0
WQ Output face velocity=0
WQ Output face area=0
WQ Output face dispersion=0
WQ Output cell volume=0
WQ Output cell surface area=0
WQ Output cell continuity=0
WQ Output cumulative cell continuity=0
WQ Output face conc=0
WQ Output face dconc_dx=0
WQ Output face courant=0
WQ Output face peclet=0
WQ Output face adv mass=0
WQ Output face disp mass=0
WQ Output cell mass=0
WQ Output cell source sink temp=0
WQ Output cell source sink nsm=0
WQ Output MaxMinRange=-1
WQ Daily Max Min Mean=-1
WQ Daily Range=0
WQ Daily Time=0
WQ Create Restart=0
WQ Fixed Restart=0
WQ System Summary=0
WQ Use Fixed Temperature=0
Sorting and Armoring Iterations= 10
XS Update Threshold= 0.02
Hydraulics Update Threshold= 0.02
Energy Slope Method= 1
Volume Change Method= 0
XS Weighting Method= 0
Number of US Weighted Cross Sections= 1
Number of DS Weighted Cross Sections= 1
Upstream XS Weight=0.25
Main XS Weight=0.5
Downstream XS Weight=0.25
Number of DS XS's Weighted with US Boundary= 1
Upstream Boundary Weight= 1
Weight of XSs Associated with US Boundary= 0
Number of US XS's Weighted with DS Boundary= 1
Downstream Boundary Weight= 0.5
Weight of XSs Associated with DS Boundary= 0.5
Sediment Output Level= 4
Mass or Volume Output= 0
Output Increment Type= 1
Profile and TS Output Increment= 10
XS Output Flag= 0
XS Output Increment= 10
Disregard all LS=0
Disregard all Conn=0
Disregard all Breaches=0
Disregard all Pumps=0

--- L100-00-00.f01 (steady flow) ---

Flow Title=Effective Multi-Profile 2017
Version=Version 3.0.1  Mar 2001
Number of Profiles= 4
Profile Names=10PCT_10yr,2PCT_50yr,1PCT_100yr,0.2PCT_500yr
River Rch & RM=L100-00-00,L100-00-00_0013 ,115231.7
     170     340     360     600
River Rch & RM=L100-00-00,L100-00-00_0013 ,114576.1
     180     360     380     640
River Rch & RM=L100-00-00,L100-00-00_0013 ,114244.9
     180     370     390     660
River Rch & RM=L100-00-00,L100-00-00_0013 ,113874.0
     190     390     410     680
River Rch & RM=L100-00-00,L100-00-00_0013 ,113500.6
     190     400     420     700
River Rch & RM=L100-00-00,L100-00-00_0013 ,113168.1
     200     410     430     720
River Rch & RM=L100-00-00,L100-00-00_0013 ,112791.4
     200     430     450     750
River Rch & RM=L100-00-00,L100-00-00_0013 ,112091.0
     200     430     460     770
River Rch & RM=L100-00-00,L100-00-00_0013 ,111127.2
     210     410     480     790
River Rch & RM=L100-00-00,L100-00-00_0013 ,108780.6
     623    1329    1774    3261
River Rch & RM=L100-00-00,L100-00-00_0013 ,107635.9
     640    1370    1830    3370
River Rch & RM=L100-00-00,L100-00-00_0013 ,104700.3
     680    1450    1940    3610
River Rch & RM=L100-00-00,L100-00-00_0013 ,102990.5
     710    1520    2040    3800
River Rch & RM=L100-00-00,L100-00-00_0013 ,100630.4
     700    1600    2100    4000
River Rch & RM=L100-00-00,L100-00-00_0013 ,98957.5
     771    1655    2227    4191
River Rch & RM=L100-00-00,L100-00-00_0013 ,91342.6
     860    1830    2470    4620
River Rch & RM=L100-00-00,L100-00-00_0013 ,84555.7
     950    2020    2730    5070
River Rch & RM=L100-00-00,L100-00-00_0013 ,78110.5
    1548    3275    4435    8167
River Rch & RM=L100-00-00,L100-00-00_0013 ,70258.2
    1600    3300    4500    8500
River Rch & RM=L100-00-00,L100-00-00_0013 ,60219.9
    2654    4669    6242   11315
River Rch & RM=L100-00-00,L100-00-00_0013 ,51947.2
    2600    4900    6500   11900
River Rch & RM=L100-00-00,L100-00-00_0013 ,40766.4
    2582    5136    6932   12825
River Rch & RM=L100-00-00,L100-00-00_0013 ,19829.2
    2676    5771    7686   14060
Boundary for River Rch & Prof#=L100-00-00,L100-00-00_0013 , 1
Up Type= 0
Dn Type= 3
Dn Slope=.0014
Boundary for River Rch & Prof#=L100-00-00,L100-00-00_0013 , 2
Up Type= 0
Dn Type= 3
Dn Slope=.0014
Boundary for River Rch & Prof#=L100-00-00,L100-00-00_0013 , 3
Up Type= 0
Dn Type= 3
Dn Slope=.0014
Boundary for River Rch & Prof#=L100-00-00,L100-00-00_0013 , 4
Up Type= 0
Dn Type= 3
Dn Slope=.0014
DSS Import GetInterval= 0
DSS Import GetPeak= 0
DSS Import FillOption= 0

--- L100-00-00.f02 (steady flow) ---

Flow Title=Effective Floodway 2017
Version=Version 3.0.1  May 2012
Number of Profiles= 2
Profile Names=1PCT_100yr,1PCTFloodway_100yrFW
River Rch & RM=L100-00-00,L100-00-00_0013 ,115231.7
     360     360
River Rch & RM=L100-00-00,L100-00-00_0013 ,114576.1
     380     380
River Rch & RM=L100-00-00,L100-00-00_0013 ,114244.9
     390     390
River Rch & RM=L100-00-00,L100-00-00_0013 ,113874.0
     410     410
River Rch & RM=L100-00-00,L100-00-00_0013 ,113500.6
     420     420
River Rch & RM=L100-00-00,L100-00-00_0013 ,113168.1
     430     430
River Rch & RM=L100-00-00,L100-00-00_0013 ,112791.4
     450     450
River Rch & RM=L100-00-00,L100-00-00_0013 ,112091.0
     460     460
River Rch & RM=L100-00-00,L100-00-00_0013 ,111127.2
     480     480
River Rch & RM=L100-00-00,L100-00-00_0013 ,108780.6
    1774    1774
River Rch & RM=L100-00-00,L100-00-00_0013 ,107635.9
    1830    1830
River Rch & RM=L100-00-00,L100-00-00_0013 ,104700.3
    1940    1940
River Rch & RM=L100-00-00,L100-00-00_0013 ,102990.5
    2040    2040
River Rch & RM=L100-00-00,L100-00-00_0013 ,100630.4
    2100    2100
River Rch & RM=L100-00-00,L100-00-00_0013 ,98957.5
    2227    2227
River Rch & RM=L100-00-00,L100-00-00_0013 ,91342.6
    2470    2470
River Rch & RM=L100-00-00,L100-00-00_0013 ,84555.7
    2730    2730
River Rch & RM=L100-00-00,L100-00-00_0013 ,78110.5
    4435    4435
River Rch & RM=L100-00-00,L100-00-00_0013 ,70258.2
    4500    4500
River Rch & RM=L100-00-00,L100-00-00_0013 ,60219.9
    6242    6242
River Rch & RM=L100-00-00,L100-00-00_0013 ,51947.2
    6500    6500
River Rch & RM=L100-00-00,L100-00-00_0013 ,40766.4
    6932    6932
River Rch & RM=L100-00-00,L100-00-00_0013 ,19829.2
    7686    7686
Boundary for River Rch & Prof#=L100-00-00,L100-00-00_0013 , 1
Up Type= 0
Dn Type= 1
Dn Known WS=130.46
Boundary for River Rch & Prof#=L100-00-00,L100-00-00_0013 , 2
Up Type= 0
Dn Type= 1
Dn Known WS=131.46
DSS Import GetInterval= 0
DSS Import GetPeak= 0
DSS Import FillOption= 0

--- L100-00-00.g01 (geometry) ---

Geom Title=L100-00-00
Program Version=4.10

River Reach=L100-00-00      ,L100-00-00_0013
Reach XY= 30
      2965593.77   13935940.7171    2967518.6328   13935159.0002
    2969484.3046   13937663.9228    2972614.8094   13938890.0391
    2975895.1913   13936242.4697    2978994.0896   13934897.3376
    2979121.0428   13935695.9487    2980564.1851   13935923.8133
    2983308.6513   13933932.8194     2985737.492   13935529.8647
    2986266.1379   13937192.1911    2988949.2976   13937823.2675
    2991663.0328   13936450.8082    2992419.9765   13934006.3625
    2994400.8784   13935225.9806     2998087.469   13935633.3584
    2998270.8213   13936377.7584    3001921.9173   13935846.5505
    3003361.1541   13933676.4127    3010389.4169   13932606.6031
    3012109.9052   13931148.2695     3013497.926   13931787.1572
    3019592.3099   13930357.1079    3023757.2416   13925878.8101
    3024724.2545   13925917.0037    3027268.5264   13922297.2124
    3031278.9427   13922923.9494    3031302.3795    13920981.241
    3037620.9558   13916584.5399    3038463.2406   13913680.7976

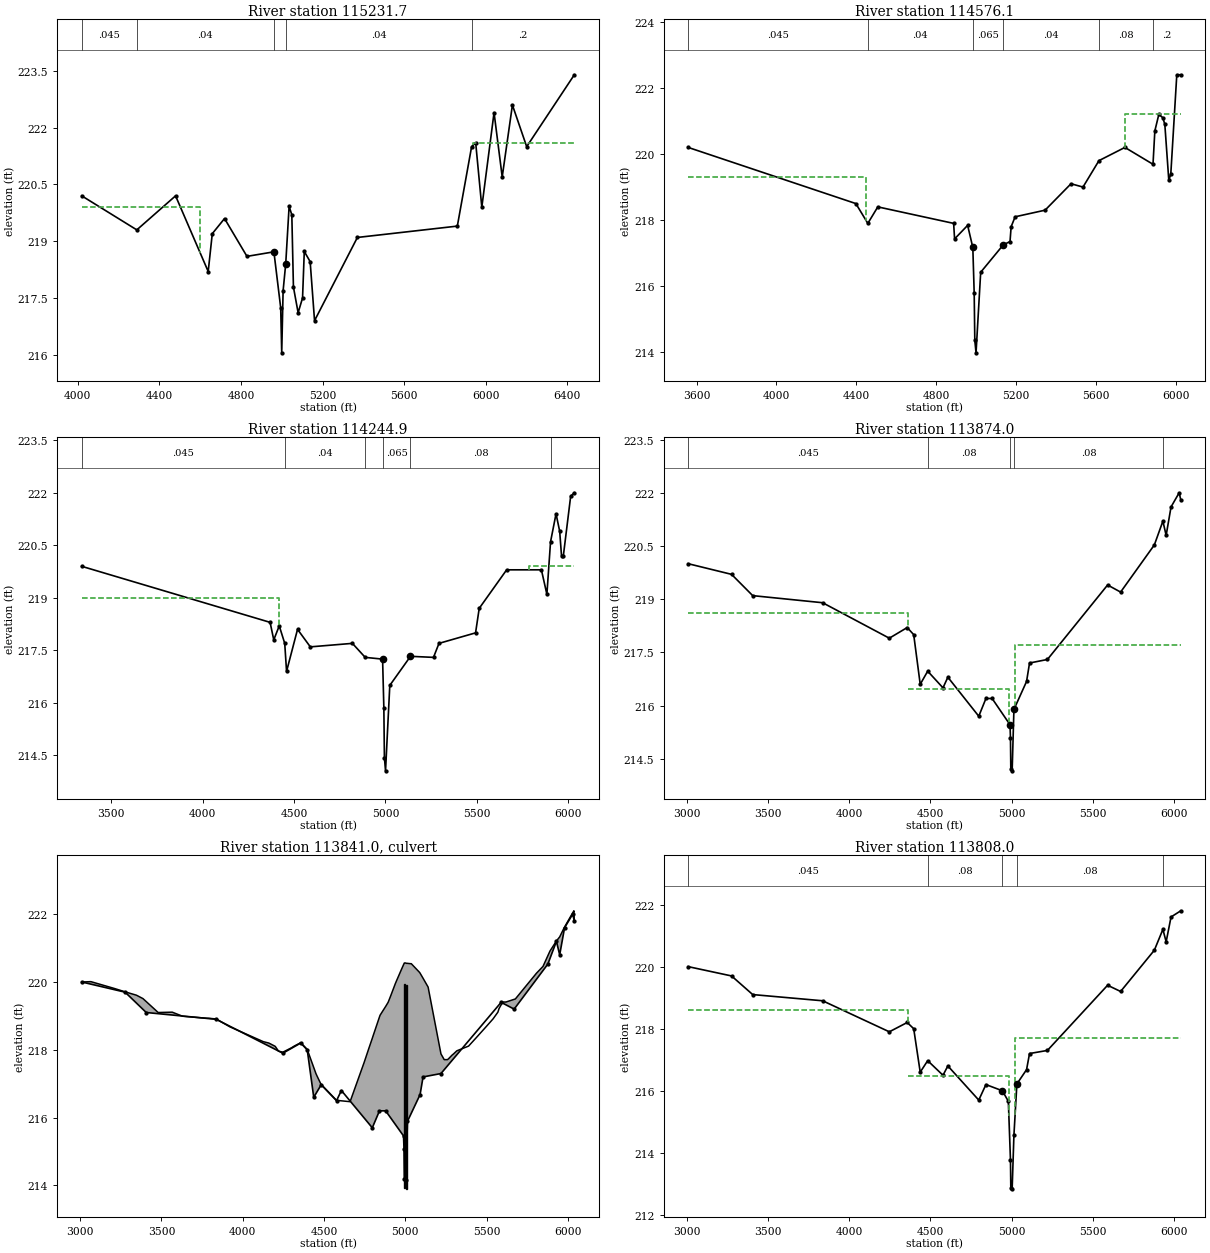
Type RM Length L Ch R = 1 ,115231.7,464.3,655.6,653.1
BEGIN DESCRIPTION:
Cross Section XS119
END DESCRIPTION:
XS GIS Cut Line= 3
     2965472.873   13936872.8946    2965670.0061   13935993.3775
    2965230.2475   13934545.2072
#Sta/Elev= 30
  4019.5   220.2  4289.5   219.3  4479.5   220.2  4639.5   218.2  4659.5   219.2
  4719.5   219.6  4829.5   218.6  4961.6  218.72  4994.9  217.24  4999.9  216.05
 5006.69  217.69  5019.6  218.41  5036.1  219.92  5049.4   219.7  5057.3  217.79
  5080.3  217.11    5102   217.5  5110.5  218.73  5139.3  218.46  5160.8   216.9
  5370.8   219.1  5860.8   219.4  5930.8   221.5  5950.8   221.6  5980.8   219.9
  6040.8   222.4  6080.8   220.7  6130.8   222.6  6200.8   221.5  6434.3   223.4
#Mann= 5 ,-1 , 0
  4019.5    .045       0  4289.5     .04       0  4961.6    .065       0
  5019.6     .04       0  5930.8      .2       0
#XS Ineff= 2 , 0
       0    4600   219.9    5940       0   221.6
Permanent Ineff=
       F       F
Bank Sta=4961.6,5019.6
XS Rating Curve= 0 ,0
Exp/Cntr=0.3,0.1

Type RM Length L Ch R = 1 ,114576.1,310.3,331.2,320.7
BEGIN DESCRIPTION:
Cross Section XS118
END DESCRIPTION:
XS GIS Cut Line= 3
     2965518.365   13936888.0587    2966268.9875   13935720.4239
    2965948.8919   13934689.0047
#Sta/Elev= 30
  3558.2   220.2  4398.2   218.5  4458.2   217.9  4508.2   218.4  4888.2   217.9
  4892.9  217.43  4958.3  217.84  4984.3  217.17  4991.2  215.78  4994.2  214.36
  5000.4  213.98  5023.7  216.42  5136.9  217.25  5170.7  217.35  5176.3   217.8
  5196.3   218.1  5346.3   218.3  5476.3   219.1  5536.3     219  5616.3   219.8
  5746.3   220.2  5887.1  219.69  5896.3   220.7  5916.3   221.2  5936.3   221.1
  5946.3   220.9  5966.3   219.2  5976.3   219.4  6006.3   222.4  6026.3   222.4
#Mann= 6 ,-1 , 0
  3558.2    .045       0  4458.2     .04       0  4984.3    .065       0
  5136.9     .04       0  5616.3     .08       0  5887.1      .2       0
#XS Ineff= 2 , 0
       0    4450   219.3    5745       0   221.2
Permanent Ineff=
       F       F
Bank Sta=4984.3,5136.9
XS Rating Curve= 0 ,0
Exp/Cntr=0.3,0.1

Type RM Length L Ch R = 1 ,114244.9,363.9,370.9,352.2
BEGIN DESCRIPTION:
Cross Section XS117
END DESCRIPTION:
XS GIS Cut Line= 3
      2965647.26   13936888.0587    2966595.0154   13935644.6035
    2966224.7308   13934576.9495
#Sta/Elev= 30
  3339.2   219.9  4369.2   218.3  4389.2   217.8  4419.2   218.2  4449.2   217.7
  4459.2   216.9  4519.2   218.1  4589.2   217.6  4819.2   217.7  4889.2   217.3
  4984.3  217.25  4991.2  215.86  4994.2  214.44  5000.4  214.06  5023.7   216.5
  5136.9  217.33  5262.7   217.3  5292.7   217.7  5492.7     218  5512.7   218.7
  5662.7   219.8  5852.7   219.8  5882.7   219.1  5902.7   220.6  5932.7   221.4
  5952.7   220.9  5962.7   220.2  5972.7   220.2  6012.7   221.9  6032.7     222
#Mann= 6 ,-1 , 0
  3339.2    .045       0  4449.2     .04       0  4889.2     .08       0
  4984.3    .065       0  5136.9     .08       0  5902.7      .2       0
#XS Ineff= 2 , 0
       0  4419.1     219    5784       0   219.9
Permanent Ineff=
       F       F
Bank Sta=4984.3,5136.9
XS Rating Curve= 0 ,0
Exp/Cntr=0.5,0.3

Type RM Length L Ch R = 1 ,113874.0,66,66,66
BEGIN DESCRIPTION:
Upstream Section of Bridge/Culvert/Weir
END DESCRIPTION:
XS GIS Cut Line= 4
     2965703.714   13936924.0164    2966904.5069   13935589.8023
    2966942.4171   13935521.5639     2966521.048   13934445.4521
#Sta/Elev= 30
  3010.2     220  3276.8   219.7  3406.8   219.1  3836.8   218.9  4246.8   217.9
  4356.8   218.2  4396.8     218  4436.8   216.6  4482.8  216.97  4576.8   216.5
  4606.8   216.8  4796.8   215.7  4840.9   216.2    4879   216.2  4988.9  215.46
  4991.8  215.08  4993.9   214.2  5002.1  214.16    5013  215.89  5090.7  216.68
    5109   217.2    5219   217.3    5589   219.4    5669   219.2  5876.5  220.53
    5929   221.2    5949   220.8    5979   221.6    6029     222    6039   221.8
#Mann= 5 ,-1 , 0
  3010.2    .045       0  4482.8     .08       0  4988.9    .065       0
    5013     .08       0    5929      .2       0
#XS Ineff= 3 ,-1
  3010.2    4360   218.6    4360    4982  216.47    5020    6039  217.71
Permanent Ineff=
       F       F       F
Bank Sta=4988.9,5013
XS Rating Curve= 0 ,0
Exp/Cntr=0.5,0.3

Type RM Length L Ch R = 2 ,113841.0,,,
BEGIN DESCRIPTION:
HEGAR ROAD
Structure ID: L100-00-00-S13
END DESCRIPTION:
Bridge Culvert--1,0,-1,-1, 0
Deck Dist Width WeirC Skew NumUp NumDn MinLoCord MaxHiCord MaxSubmerge Is_Ogee
10,46,3,0, 90, 90, , , 0.95, 0, 1,1,,
  3010.2  3066.8  3210.2  3230.2  3276.8  3346.8  3386.8  3480.2  3566.8  3630.2
  3780.2  3790.2  3836.8  3920.2  4126.8  4160.2  4196.8  4200.2  4220.2  4246.8
  4300.2  4316.8  4356.8  4396.8  4450.2  4456.8  4476.8  4480.2  4482.8  4500.2
  4576.8  4660.2  4746.8  4776.8  4796.8  4800.9  4840.9  4844.6    4879  4894.1
    4909    4939  4941.9  4943.4  4978.7  4988.9  4991.8  4993.8  4993.9  5002.1
  5006.8  5008.3    5013  5031.2  5036.5    5088  5090.7    5109    5140    5219
    5239    5259  5266.5  5276.5  5286.5  5296.5  5316.5    5389  5396.5  5436.5
  5466.5  5496.5    5539    5569  5576.5    5599    5619  5676.5  5806.5  5846.5
    5889  5891.6  5926.5    5929    5949  5976.5    5979    6029  6036.5    6039
     220  220.01  219.81  219.78  219.71  219.61  219.51   219.1  219.11  218.99
  218.93  218.93  218.91  218.68  218.24   218.2  218.11   218.1  217.96  217.93
  218.06  218.11  218.21  218.01   217.3  217.23  217.03     217  216.98  216.89
  216.51  216.47  217.63  218.06  218.34   218.4  218.97  219.02  219.28   219.4
  219.58  219.96  219.99  220.01   220.4  220.51  220.54  220.56  220.56  220.56
  220.55  220.55  220.55  220.54  220.54  220.28  220.26  220.11  219.85  217.88
  217.71  217.71  217.74  217.79  217.84  217.88  217.97  218.11  218.15  218.36
  218.52  218.68  218.91  219.11  219.22  219.41  219.41   219.5  220.26  220.46
  220.91  220.93  221.19  221.21  221.33   221.6  221.62  222.04   222.1   221.8
                                                                                
                                                                                
                                                                                
                                                                                
                                                  215.08  214.24   214.2  214.16
  214.77  214.99  215.89
                                                                                
                                                                                
                                                                                
  3010.2  3066.8  3210.2  3230.2  3276.8  3346.8  3386.8  3480.2  3566.8  3630.2
  3780.2  3790.2  3836.8  3920.2  4126.8  4160.2  4196.8  4200.2  4220.2  4246.8
  4300.2  4316.8  4356.8  4396.8  4450.2  4456.8  4476.8  4480.2  4482.8  4500.2
  4576.8  4660.2  4746.8  4776.8  4796.8  4800.9  4840.9  4844.6    4879  4894.1
    4909    4939  4941.9  4943.4  4978.7  4988.9  4991.8  4993.8  4993.9  5002.1
  5006.8  5008.3    5013  5031.2  5036.5    5088  5090.7    5109    5140    5219
    5239    5259  5266.5  5276.5  5286.5  5296.5  5316.5    5389  5396.5  5436.5
  5466.5  5496.5    5539    5569  5576.5    5599    5619  5676.5  5806.5  5846.5
    5889  5891.6  5926.5    5929    5949  5976.5    5979    6029  6036.5    6039
     220  220.01  219.81  219.78  219.71  219.61  219.51   219.1  219.11  218.99
  218.93  218.93  218.91  218.68  218.24   218.2  218.11   218.1  217.96  217.93
  218.06  218.11  218.21  218.01   217.3  217.23  217.03     217  216.98  216.89
  216.51  216.47  217.63  218.06  218.34   218.4  218.97  219.02  219.28   219.4
  219.58  219.96  219.99  220.01   220.4  220.51  220.54  220.56  220.56  220.56
  220.55  220.55  220.55  220.54  220.54  220.28  220.26  220.11  219.85  217.88
  217.71  217.71  217.74  217.79  217.84  217.88  217.97  218.11  218.15  218.36
  218.52  218.68  218.91  219.11  219.22  219.41  219.41   219.5  220.26  220.46
  220.91  220.93  221.19  221.21  221.33   221.6  221.62  222.04   222.1   221.8
                                                                                
                                                                                
                                                                                
                                                                                
                                                  213.75  212.91  212.87  212.83
  213.44  213.66  214.56
                                                                                
                                                                                
                                                                                
BR Coef= 1 , 1 , 1 ,1.25, 0 ,,,0.8,-1,2,0,
WSPro=,,,, 1 ,,,, 0 ,,,, 0 ,,,,-1 ,-1 ,-1 , 0 , 0 , 0 , 0 , 0
Culvert=2,6,10,46,0.015,0.5,1,8,1,213.93,4993.8,213.94,4993.8,Culvert #1  , 0 ,10
Culvert Bottom n=0.015
Culvert=2,6,10,46,0.015,0.4,1,8,1,213.9,5006.8,213.97,5006.8,Culvert #2  , 0 ,10
Culvert Bottom n=0.015
BC Design=,, 0 ,, 0 ,,,,,,
BC HTab HWMax=222
BC Use User HTab Curves=0
BC User HTab FreeFlow(D)= 0

Type RM Length L Ch R = 1 ,113808.0,81.8,307.4,366.3
BEGIN DESCRIPTION:
Downstream Section of Bridge/Culvert/Weir
END DESCRIPTION:
XS GIS Cut Line= 3
     2965817.104   13936880.8488    2967037.1984   13935577.3943
    2966599.8592   13934413.5076
#Sta/Elev= 30
  3010.2     220  3276.8   219.7  3406.8   219.1  3836.8   218.9  4246.8   217.9
  4356.8   218.2  4396.8     218  4436.8   216.6  4482.8  216.97  4576.8   216.5
  4606.8   216.8  4796.8   215.7  4840.9   216.2  4941.9     216  4978.7  215.66
  4991.8  213.76  4993.9  212.88  5002.1  212.84    5013  214.57  5031.2  216.22
  5090.7  216.68    5109   217.2    5219   217.3    5589   219.4    5669   219.2
  5876.5  220.53    5929   221.2    5949   220.8    5979   221.6    6039   221.8
#Mann= 5 ,-1 , 0
  3010.2    .045       0  4482.8     .08       0  4941.9    .065       0
  5031.2     .08       0    5929      .2       0
#XS Ineff= 3 ,-1
  3010.2    4360   218.6    4360    4982  216.47    5020    6039  217.71
Permanent Ineff=
       F       F       F
Bank Sta=4941.9,5031.2
XS Rating Curve= 0 ,0
Exp/Cntr=0.5,0.3

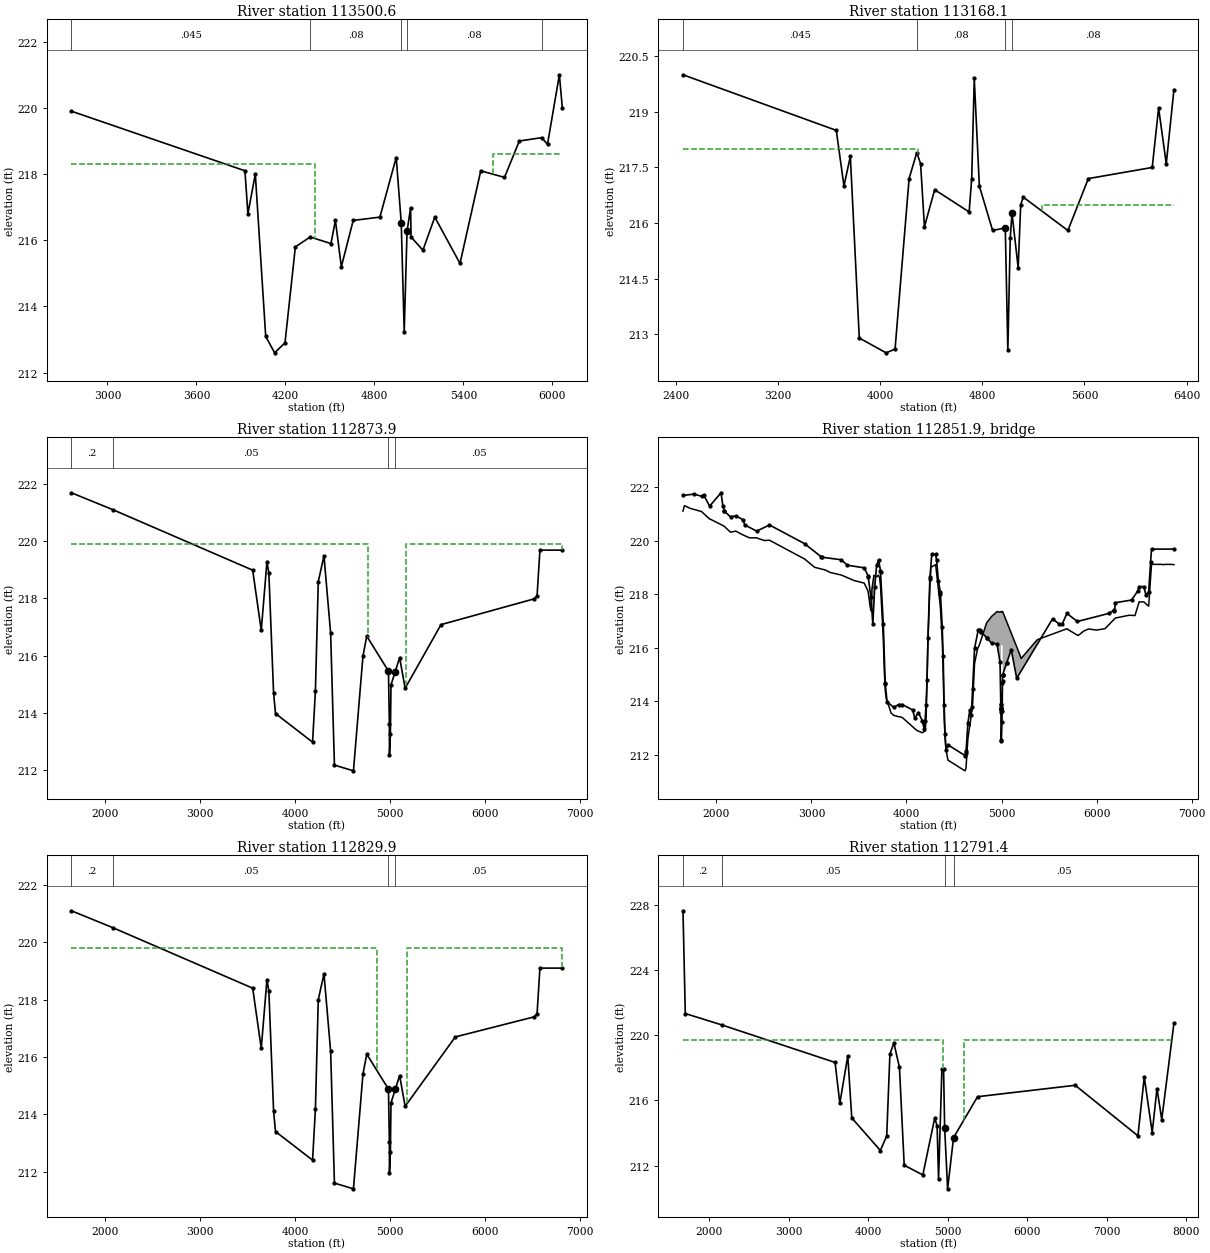
Type RM Length L Ch R = 1 ,113500.6,184,332.5,521
BEGIN DESCRIPTION:
Cross Section XS116
END DESCRIPTION:
XS GIS Cut Line= 3
     2965798.901   13936925.9689    2967269.8173   13935371.6499
    2967062.9367   13934220.0148
#Sta/Elev= 30
    2757   219.9    3927   218.1    3947   216.8    3997     218    4067   213.1
    4127   212.6    4197   212.9    4267   215.8    4367   216.1    4507   215.9
    4537   216.6    4577   215.2    4657   216.6    4837   216.7    4947   218.5
  4980.8  216.53  5000.9  213.23 5019.91  216.27    5044  216.98    5047   216.1
    5127   215.7    5207   216.7    5377   215.3    5517   218.1    5677   217.9
    5777     219    5927   219.1    5967   218.9    6047     221    6067     220
#Mann= 5 ,-1 , 0
    2757    .045       0    4367     .08       0  4980.8    .065       0
 5019.91     .08       0    5927      .2       0
#XS Ineff= 2 , 0
       0    4400   218.3    5602       0   218.6
Permanent Ineff=
       F       F
Bank Sta=4980.8,5019.91
XS Rating Curve= 0 ,0
Exp/Cntr=0.3,0.1

Type RM Length L Ch R = 1 ,113168.1,250,294.2,300
BEGIN DESCRIPTION:
Cross Section XS115
END DESCRIPTION:
XS GIS Cut Line= 4
     2965768.573   13937024.5355    2967451.7863   13935280.6654
      2967723.88   13935016.4543    2967702.2174   13933976.6474
#Sta/Elev= 30
    2458     220    3658   218.5    3718     217    3768   217.8    3838   212.9
    4048   212.5    4118   212.6    4228   217.2    4288   217.9    4318   217.6
    4348   215.9    4428   216.9    4698   216.3    4718   217.2    4738   219.9
    4778     217  4881.7   215.8  4980.8  215.87  5000.9  212.57  5019.8  215.61
  5033.4  216.26  5081.7   214.8  5101.7   216.5  5121.7   216.7    5471   215.8
    5631   217.2    6131   217.5    6181   219.1    6241   217.6    6301   219.6
#Mann= 4 ,-1 , 0
    2458    .045       0    4288     .08       0  4980.8    .065       0
  5033.4     .08       0
#XS Ineff= 2 , 0
       0    4300     218    5265       0   216.5
Permanent Ineff=
       F       F
Bank Sta=4980.8,5033.4
XS Rating Curve= 0 ,0
Exp/Cntr=0.5,0.3

Type RM Length L Ch R = 1 ,112873.9,44,44,44
BEGIN DESCRIPTION:
Upstream Section of Bridge/Culvert/Weir
END DESCRIPTION:
XS GIS Cut Line= 6
      2965064.36   13937482.9443    2966370.4957   13936855.1334
    2967591.3624   13935493.3805    2967687.8821   13935445.1207
    2968029.1136   13934985.6161    2968026.7043   13933778.9008
#Sta/Elev= 30
  1648.6  221.68    2085  221.09  3555.9  218.98  3645.9  216.88  3705.9  219.28
  3725.9  218.88  3775.9  214.68  3795.9  213.98  4185.9  212.98  4215.9  214.78
  4245.9  218.58  4305.9  219.48  4375.9  216.78  4415.9  212.18  4615.9  211.98
  4715.9  215.98  4755.9  216.68  4984.1  215.46  4993.9   213.6  4994.9  212.54
  5004.4  213.25    5011  214.98  5055.2  215.44  5101.8  215.93  5159.6  214.86
  5536.9  217.08  6517.7  217.98  6547.7  218.08  6577.7  219.68  6813.6  219.68
#Mann= 4 ,-1 , 0
  1648.6      .2       0    2085     .05       0  4984.1    .065       0
  5055.2     .05       0
#XS Ineff= 2 , 0
       0    4765   219.9    5172       0   219.9
Permanent Ineff=
       F       F
Bank Sta=4984.1,5055.2
XS Rating Curve= 0 ,0
Exp/Cntr=0.5,0.3

Type RM Length L Ch R = 3 ,112851.9,,,
BEGIN DESCRIPTION:
GRIMES RD
Pond Area Just Left of Grimes X-ing of Little Cypress
Ineffective Area is Left of Hegar/Hwy. 290 Intersection
Structure ID: L100-00-00-S14
END DESCRIPTION:
Bridge Culvert--1,0,-1,-1, 0
Deck Dist Width WeirC Skew NumUp NumDn MinLoCord MaxHiCord MaxSubmerge Is_Ogee
10,24,2.6,0, 171, 171, , , 0.95, 0, 1,1,,
  1648.6  1663.7  1723.7  1763.7  1843.7  1928.6  1933.7  2083.7    2085  2148.6
  2203.7  2278.6  2348.6  2408.6  2423.7  2428.6  2503.7  2558.6  2773.7  2843.7
  2928.6  3033.7  3146.9  3195.9  3315.9  3386.9  3445.9  3546.9  3555.9  3566.9
  3576.9  3586.9  3595.9  3596.9  3606.9  3616.9  3625.9  3636.9  3645.9  3656.9
  3665.9  3685.9  3705.9  3716.9  3725.9  3726.9  3746.9  3755.9  3766.9  3775.9
  3776.9  3786.9  3795.9  3825.9  3836.9  3865.9  3915.9  3925.9  3955.9  4106.9
  4165.9  4185.9  4195.9  4196.9  4205.9  4206.9  4215.9  4225.9  4226.9  4245.9
  4246.9  4256.9  4265.9  4305.9  4306.9  4315.9  4335.9  4355.9  4356.9  4375.9
  4376.9  4385.9  4395.9  4396.9  4405.9  4406.9  4415.9  4435.9  4466.9  4476.9
  4496.9  4516.9  4526.9  4546.9  4606.9  4615.9  4625.9  4626.9  4636.9  4645.9
  4665.9  4666.9  4695.9  4706.9  4715.9  4726.9  4746.9  4766.9  4842.9  4894.9
    4896  4951.9  4952.2  4984.1 4992.09  4992.2 4992.31  4992.7  4992.8 4992.91
  4993.1  4993.2  4993.3  4993.9  4994.9  4998.7  5001.9  5011.6 5011.65  5185.9
  5205.9  5375.9  5536.9  5687.7  5703.6  5797.7  5807.7  5853.6  5857.7  5913.6
  5917.7  5937.7  5977.7  5997.7  6087.7  6197.7  6213.6  6337.7  6367.7  6403.6
  6433.6  6447.7  6497.7  6527.7  6547.7  6567.7  6577.7  6607.7  6613.6  6643.6
  6653.6  6663.6  6673.6  6683.6  6703.6  6723.6  6743.6  6753.6  6763.6  6783.6
  6813.6
   221.1   221.3   221.2  221.16  221.08   220.8   220.8  220.53  220.52  220.31
  220.35  220.21   220.1   220.1   220.1  220.09     220  220.01   219.6  219.47
  219.31     219   218.9  218.81  218.71   218.6  218.51  218.42  218.41  218.33
  218.25  218.18  218.11  218.08  217.82  217.55  217.38   218.2  218.43   218.7
  218.69  218.65  218.71   218.6  218.33   218.3   216.9  216.31   215.1  214.45
   214.4   214.1  213.99  213.71  213.57  213.48  213.43  213.43   213.4  212.92
  212.83  212.88   212.9   212.9  213.35   213.4  214.75  216.25   216.4   218.3
   218.4     219  219.02   219.1   219.1  218.81  218.17  217.53   217.5  216.26
   216.2  215.11  213.45   213.3  212.67   212.6   212.2  211.81  211.74  211.72
  211.67  211.63  211.61  211.56  211.43  211.41  211.51  211.57  212.11  212.61
  213.11  213.09  213.91  214.74  215.41   215.6  215.95  216.11  216.93  217.17
  217.17  217.35  217.35  217.33  217.33  217.33  217.33  217.33  217.33  217.34
  217.34  217.34  217.34  217.34  217.34  217.35  217.35  217.35  217.35   215.8
   215.6   216.3  216.51  216.71  216.67  216.47  216.46  216.59  216.61   216.7
   216.7  216.69  216.67  216.66  216.71  217.11  217.12  217.21  217.21   217.2
  217.55  217.71  217.71  217.61  217.55  218.61  219.11  219.11  219.11  219.11
  219.11  219.11  219.11  219.11   219.1  219.11  219.11  219.11  219.11  219.11
   219.1
                                                                                
                                                                                
                                                                                
                                                                                
                                                                                
                                                                                
                                                                                
                                                                                
                                                                                
                                                                                
                                                                                
                                          213.29  213.27  213.19  213.17  213.16
  213.13  216.09  216.09  216.09  216.09   216.1   216.1   216.1
                                                                                
                                                                                
                                                                                
                                                                                
        
  1648.6  1663.7  1723.7  1763.7  1843.7  1928.6  1933.7  2083.7    2085  2148.6
  2203.7  2278.6  2348.6  2408.6  2423.7  2428.6  2503.7  2558.6  2773.7  2843.7
  2928.6  3033.7  3146.9  3195.9  3315.9  3386.9  3445.9  3546.9  3555.9  3566.9
  3576.9  3586.9  3595.9  3596.9  3606.9  3616.9  3625.9  3636.9  3645.9  3656.9
  3665.9  3685.9  3705.9  3716.9  3725.9  3726.9  3746.9  3755.9  3766.9  3775.9
  3776.9  3786.9  3795.9  3825.9  3836.9  3865.9  3915.9  3925.9  3955.9  4106.9
  4165.9  4185.9  4195.9  4196.9  4205.9  4206.9  4215.9  4225.9  4226.9  4245.9
  4246.9  4256.9  4265.9  4305.9  4306.9  4315.9  4335.9  4355.9  4356.9  4375.9
  4376.9  4385.9  4395.9  4396.9  4405.9  4406.9  4415.9  4435.9  4466.9  4476.9
  4496.9  4516.9  4526.9  4546.9  4606.9  4615.9  4625.9  4626.9  4636.9  4645.9
  4665.9  4666.9  4695.9  4706.9  4715.9  4726.9  4746.9  4766.9  4842.9  4894.9
    4896  4951.9  4952.2  4984.1 4992.09  4992.2 4992.31  4992.7  4992.8 4992.91
  4993.1  4993.2  4993.3  4993.9  4994.9  4998.7  5001.9  5011.6 5011.65  5185.9
  5205.9  5375.9  5536.9  5687.7  5703.6  5797.7  5807.7  5853.6  5857.7  5913.6
  5917.7  5937.7  5977.7  5997.7  6087.7  6197.7  6213.6  6337.7  6367.7  6403.6
  6433.6  6447.7  6497.7  6527.7  6547.7  6567.7  6577.7  6607.7  6613.6  6643.6
  6653.6  6663.6  6673.6  6683.6  6703.6  6723.6  6743.6  6753.6  6763.6  6783.6
  6813.6
   221.1   221.3   221.2  221.16  221.08   220.8   220.8  220.53  220.52  220.31
  220.35  220.21   220.1   220.1   220.1  220.09     220  220.01   219.6  219.47
  219.31     219   218.9  218.81  218.71   218.6  218.51  218.42  218.41  218.33
  218.25  218.18  218.11  218.08  217.82  217.55  217.38   218.2  218.43   218.7
  218.69  218.65  218.71   218.6  218.33   218.3   216.9  216.31   215.1  214.45
   214.4   214.1  213.99  213.71  213.57  213.48  213.43  213.43   213.4  212.92
  212.83  212.88   212.9   212.9  213.35   213.4  214.75  216.25   216.4   218.3
   218.4     219  219.02   219.1   219.1  218.81  218.17  217.53   217.5  216.26
   216.2  215.11  213.45   213.3  212.67   212.6   212.2  211.81  211.74  211.72
  211.67  211.63  211.61  211.56  211.43  211.41  211.51  211.57  212.11  212.61
  213.11  213.09  213.91  214.74  215.41   215.6  215.95  216.11  216.93  217.17
  217.17  217.35  217.35  217.33  217.33  217.33  217.33  217.33  217.33  217.34
  217.34  217.34  217.34  217.34  217.34  217.35  217.35  217.35  217.35   215.8
   215.6   216.3  216.51  216.71  216.67  216.47  216.46  216.59  216.61   216.7
   216.7  216.69  216.67  216.66  216.71  217.11  217.12  217.21  217.21   217.2
  217.55  217.71  217.71  217.61  217.55  218.61  219.11  219.11  219.11  219.11
  219.11  219.11  219.11  219.11   219.1  219.11  219.11  219.11  219.11  219.11
   219.1
                                                                                
                                                                                
                                                                                
                                                                                
                                                                                
                                                                                
                                                                                
                                                                                
                                                                                
                                                                                
                                                                                
                                          212.95  212.93  212.85  212.83  212.82
  212.79  215.75  215.75  215.75  215.75  215.76  215.76  215.76
                                                                                
                                                                                
                                                                                
                                                                                
        
BR Coef= 1 , 1 , 0 ,1.25, 0 ,,,0.8,0,2,0,
WSPro=,,,, 1 ,,,, 0 ,,,, 0 ,,,,-1 ,-1 ,-1 , 0 , 0 , 0 , 0 , 0
BR U #Sta/Elev= 119
  1648.6  221.68  1763.7  221.73  1843.7  221.65  1868.6  221.68  1928.6  221.28
  2048.6  221.78  2068.6  221.28  2083.7   221.1    2085  221.09  2148.6  220.88
  2203.7  220.92  2278.6  220.78  2298.6  220.58  2423.7  220.35  2558.6  220.58
  2928.6  219.88  3103.7  219.39  3105.9  219.38  3315.9  219.28  3375.9  219.08
  3555.9  218.98  3595.9  218.68  3596.9  218.65  3625.9  217.88  3645.9  216.88
  3665.9  218.28  3685.9  219.08  3705.9  219.28  3725.9  218.88  3726.9  218.81
  3755.9  216.88  3775.9  214.68  3776.9  214.65  3795.9  213.98  3865.9  213.78
  3915.9  213.88  3955.9  213.88  4065.9  213.68  4085.9  213.38  4125.9  213.58
  4165.9  213.28  4185.9  212.98  4195.9  213.28  4205.9  213.88  4215.9  214.78
  4225.9  216.38  4245.9  218.58  4246.9  218.63  4265.9  219.48  4305.9  219.48
  4315.9  219.28  4335.9  218.48  4355.9  218.08  4356.9  218.02  4375.9  216.78
  4385.9  215.68  4395.9  213.88  4405.9  212.78  4415.9  212.18  4435.9  212.38
  4615.9  211.98  4625.9  212.08  4626.9  212.14  4645.9  213.18  4665.9  213.68
  4675.9  213.48  4685.9  213.78  4695.9  214.48  4715.9  215.98  4755.9  216.68
  4775.9  216.68  4786.9  216.58  4787.2  216.58  4842.5  216.38  4842.9  216.38
  4894.9  216.17  4952.2  216.14  4984.1  215.46 4992.09  213.89 4992.31  213.85
  4992.7  213.77  4992.8  213.75 4992.91  213.74  4993.1  213.71  4993.2   213.7
  4993.3  213.68  4993.9   213.6  4994.9  212.54  4998.7  212.57  5004.4  213.25
    5006  213.66 5009.89  214.69 5010.11  214.75    5011  214.98  5011.4  214.98
 5011.49  214.99  5011.7  214.99  5055.2  215.44  5055.9  215.45  5101.8  215.93
  5159.6  214.86  5536.9  217.08  5607.7  216.88  5637.7  216.88  5687.7  217.28
  5797.7  216.98  6127.7  217.28  6183.6   217.4  6187.7  217.38  6197.7  217.68
  6367.7  217.78  6433.6  218.12  6447.7  218.28  6497.7  218.28  6517.7  217.98
  6547.7  218.08  6567.7  219.18  6577.7  219.68  6813.6  219.68
BR U #Mann= 4
  1648.6      .2    2085     .05  4984.1     .06  5055.2     .05
BR D #Sta/Elev= 128
  1648.6   221.1  1758.6   221.2  1778.6     221  1868.6   221.1  1928.6   220.7
  2048.6   221.2  2068.6   220.7  2083.7  220.52    2085  220.51  2148.6   220.3
  2203.7  220.34  2218.6   220.4  2278.6   220.2  2298.6     220  2348.6   219.9
  2408.6     220  2428.6   219.7  2558.6     220  2928.6   219.3  3103.7  218.81
  3105.9   218.8  3315.9   218.7  3375.9   218.5  3555.9   218.4  3595.9   218.1
  3596.9  218.07  3625.9   217.3  3645.9   216.3  3665.9   217.7  3685.9   218.5
  3705.9   218.7  3725.9   218.3  3726.9  218.23  3755.9   216.3  3775.9   214.1
  3776.9  214.07  3795.9   213.4  3865.9   213.2  3915.9   213.3  3955.9   213.3
  4065.9   213.1  4085.9   212.8  4125.9     213  4165.9   212.7  4185.9   212.4
  4195.9   212.7  4205.9   213.3  4215.9   214.2  4225.9   215.8  4245.9     218
  4246.9  218.05  4265.9   218.9  4305.9   218.9  4315.9   218.7  4335.9   217.9
  4355.9   217.5  4356.9  217.44  4375.9   216.2  4385.9   215.1  4395.9   213.3
  4405.9   212.2  4415.9   211.6  4435.9   211.8  4615.9   211.4  4625.9   211.5
  4626.9  211.56  4645.9   212.6  4665.9   213.1  4666.9  213.08  4685.9   213.2
  4695.9   213.9  4715.9   215.4  4755.9   216.1  4775.9   216.1  4786.9     216
  4787.2     216  4842.5   215.8  4842.9   215.8  4894.9  215.59  4952.2  215.56
  4984.1  214.88 4992.09  213.31 4992.31  213.27  4992.7  213.19  4992.8  213.17
 4992.91  213.16  4993.1  213.13  4993.2  213.12  4993.3   213.1  4993.9  213.02
  4994.9  211.96  4998.7  211.99  5004.4  212.67    5006  213.08 5009.89  214.11
 5010.11  214.17    5011   214.4  5011.4   214.4 5011.49  214.41  5011.7  214.41
  5055.2  214.86  5055.9  214.87  5101.8  215.35  5159.6  214.28  5375.9  215.55
  5607.7   216.3  5637.7   216.3  5687.7   216.7  5797.7   216.4  5807.7   216.3
  5853.6  216.58  5857.7   216.6  5913.6  216.41  5977.7   216.4  6087.7   216.7
  6147.7     217  6153.6  216.97  6197.7   217.1  6367.7   217.2  6433.6  217.54
  6447.7   217.7  6497.7   217.7  6517.7   217.4  6527.7   217.6  6547.7   217.5
  6567.7   218.6  6577.7   219.1  6813.6   219.1
BR D #Mann= 4
  1648.6      .2    2085     .05  4984.1     .06  5055.9     .05
BC Design=,, 0 ,, 0 ,,,,,,
BC HTab HWMax=221.78
BC Use User HTab Curves=0
BC User HTab FreeFlow(D)= 0

Type RM Length L Ch R = 1 ,112829.9,47.2,38.5,9.4
BEGIN DESCRIPTION:
Downstream Section of Bridge/Culvert/Weir
END DESCRIPTION:
XS GIS Cut Line= 6
     2965057.365   13937503.2787    2966401.5723   13936853.0913
    2967620.3183   13935531.9884      2967702.36   13935493.3805
    2968087.0704   13934937.1761    2968111.9275   13933829.9249
#Sta/Elev= 30
  1648.6   221.1    2085  220.51  3555.9   218.4  3645.9   216.3  3705.9   218.7
  3725.9   218.3  3775.9   214.1  3795.9   213.4  4185.9   212.4  4215.9   214.2
  4245.9     218  4305.9   218.9  4375.9   216.2  4415.9   211.6  4615.9   211.4
  4715.9   215.4  4755.9   216.1  4984.1  214.88  4993.9  213.02  4994.9  211.96
  5004.4  212.67    5011   214.4  5055.9  214.87  5101.8  215.35  5159.6  214.28
  5687.7   216.7  6517.7   217.4  6547.7   217.5  6577.7   219.1  6813.6   219.1
#Mann= 4 ,-1 , 0
  1648.6      .2       0    2085     .05       0  4984.1    .065       0
  5055.9     .05       0
#XS Ineff= 2 , 0
       0    4860   219.8    5182       0   219.8
Permanent Ineff=
       F       F
Bank Sta=4984.1,5055.9
XS Rating Curve= 0 ,0
Exp/Cntr=0.5,0.3

Type RM Length L Ch R = 1 ,112791.4,520,520,520
BEGIN DESCRIPTION:
Upstream Section of Bridge/Culvert/Weir
END DESCRIPTION:
XS GIS Cut Line= 6
     2965067.865   13937537.5332    2966420.6284   13936880.4766
    2967315.3095   13935917.5571    2967605.6772   13935610.9221
     2967724.302   13935480.4349    2969323.2164   13933228.9666
#Sta/Elev= 30
  1668.9  227.62  1697.7  221.32  2157.7  220.62  3582.8  218.32  3642.8  215.82
  3742.8  218.72  3792.8  214.92  4152.8  212.92  4232.8  213.82  4272.8  218.82
  4322.8  219.52  4392.8  218.02  4452.8  212.02  4687.2  211.42  4837.2  214.92
  4867.2  214.42  4885.1  211.16  4927.3   217.9  4948.2  217.91  4961.9   214.3
  4999.2  210.57  5073.7  213.71  5375.9  216.22  6605.1  216.92    7394  213.82
    7474  217.42    7574  214.02    7634  216.72    7694  214.82  7847.3  220.72
#Mann= 4 ,-1 , 0
  1668.9      .2       0  2157.7     .05       0  4961.9    .045       0
  5073.7     .05       0
#XS Ineff= 2 , 0
       0    4936   219.7    5200       0   219.7
Permanent Ineff=
       F       F
Bank Sta=4961.9,5073.7
XS Rating Curve= 0 ,0
Exp/Cntr=0.5,0.3