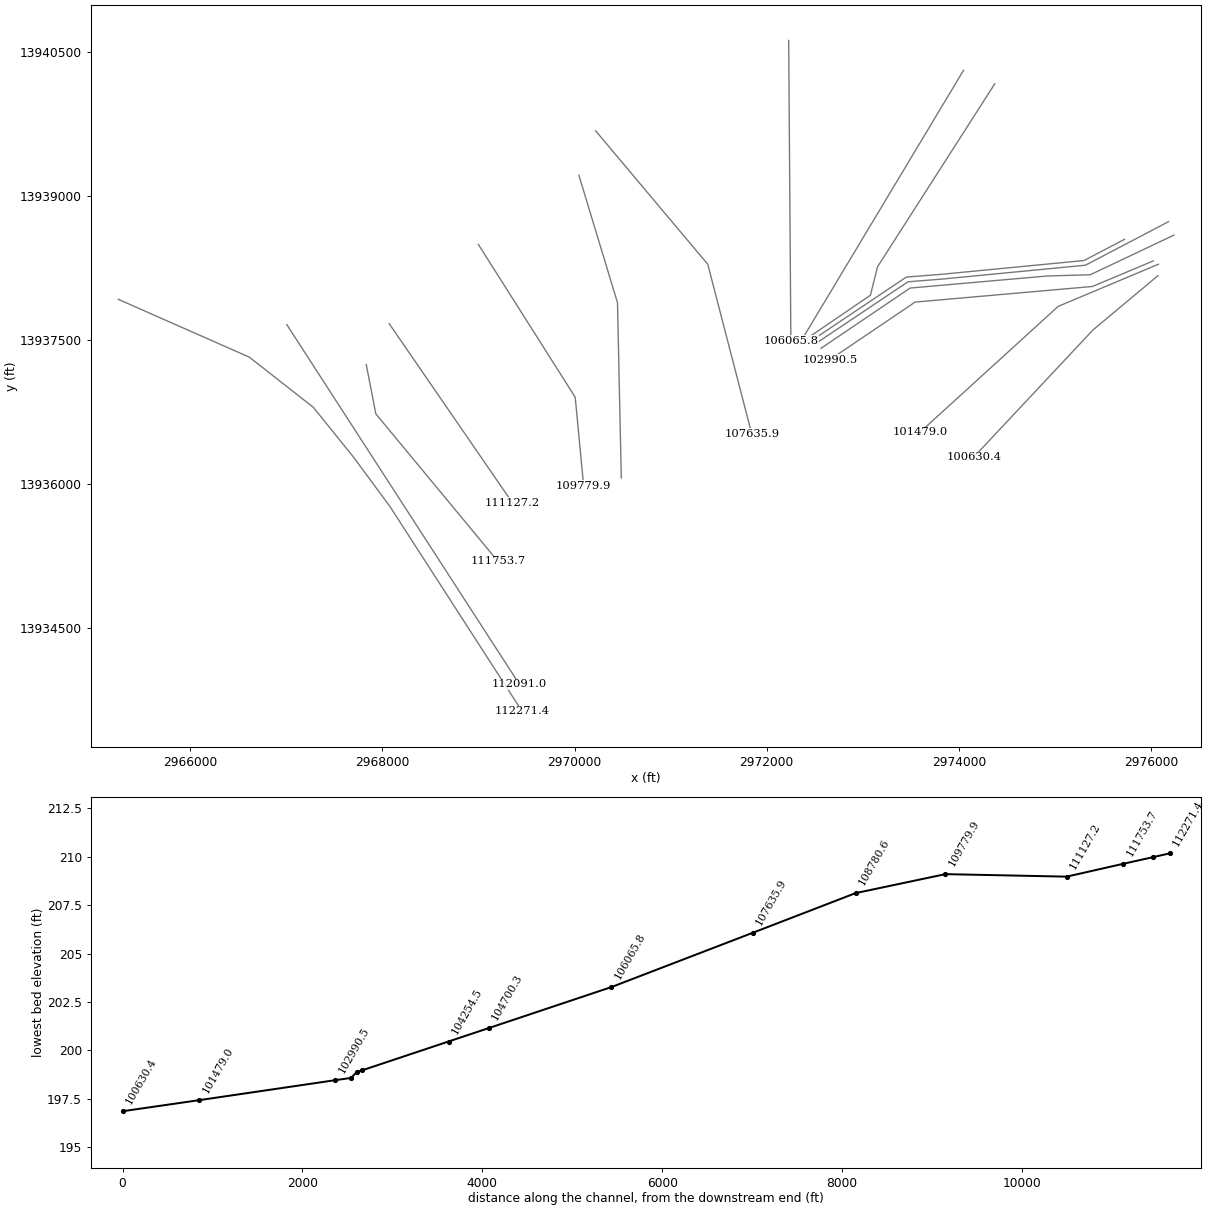
HEC-RAS study L100-00-00.prj: L100-00-00

--- L100-00-00.g01 (geometry) --- (continued)

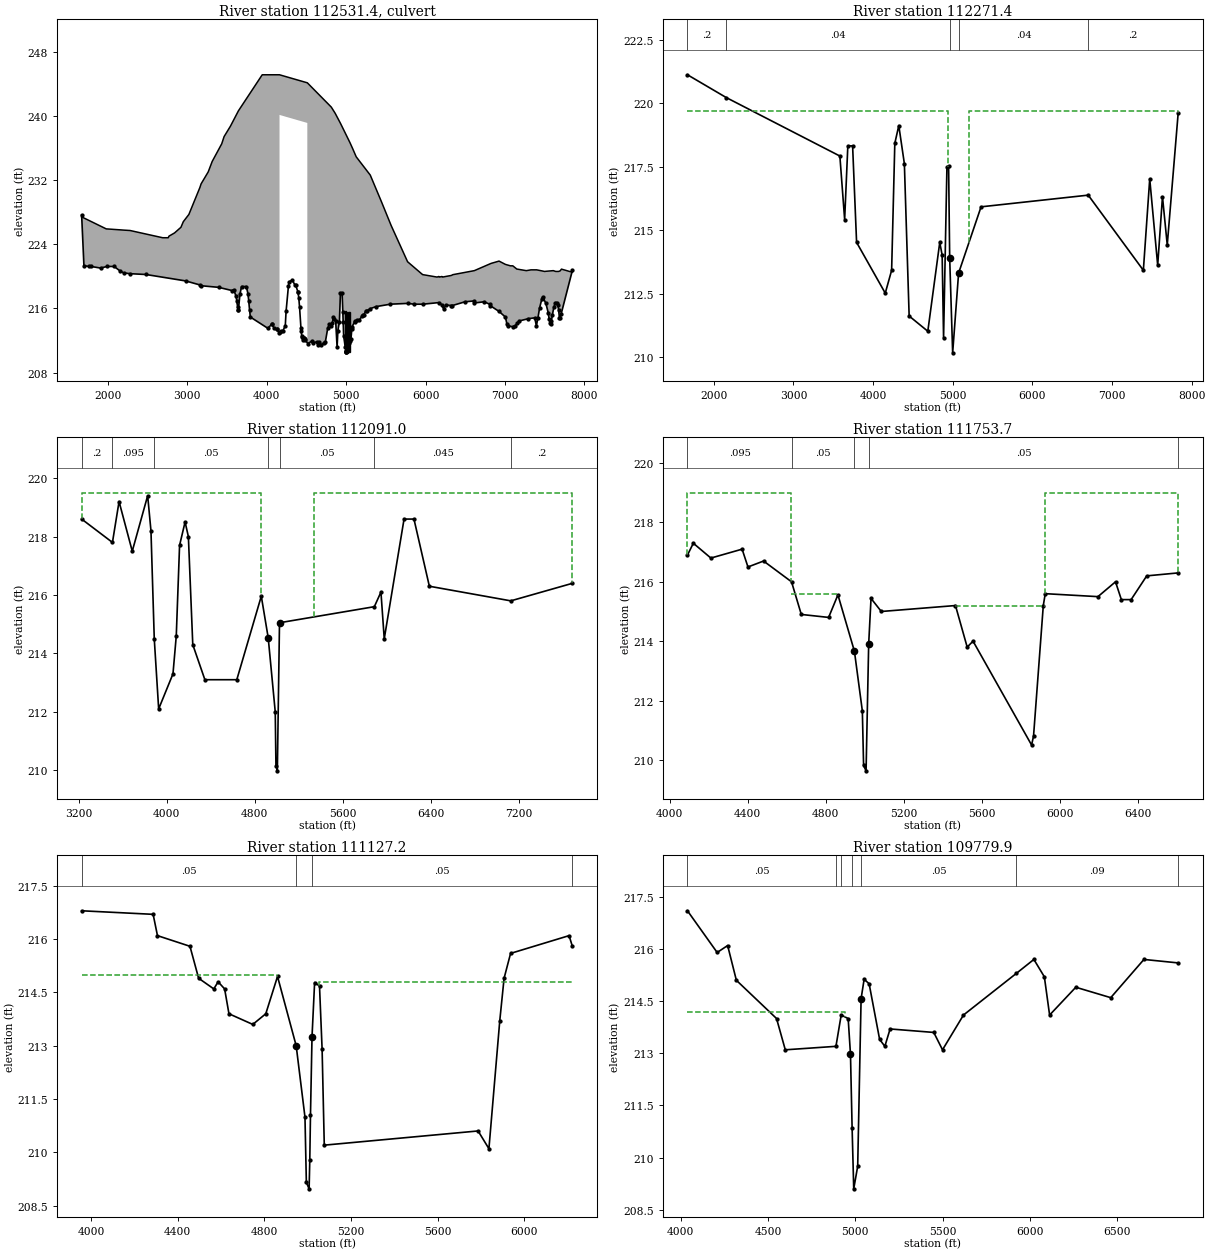
Type RM Length L Ch R = 2 ,112531.4,,,
BEGIN DESCRIPTION:
HWY 290
-- SEE COMMENTS
LOB Includes Hwy 290 Overpass at Hegar Rd.
Structure ID: L100-00-00-S290
END DESCRIPTION:
Bridge Culvert--1,0,-1,-1, 0
Deck Dist Width WeirC Skew NumUp NumDn MinLoCord MaxHiCord MaxSubmerge Is_Ogee
10,500,3,0, 196, 196, , , 0.95, 0, 1,1,,
  1668.9  1697.7  1757.7  1767.7  1787.7  1807.7  1847.7  1887.7  1907.7  1927.7
  1947.7  1967.7  1978.9  1987.7  1997.7  2077.7  2080.7  2157.7  2177.7  2197.7
  2257.7  2277.7  2278.9  2477.7  2688.9  2758.9  2768.9  2838.9  2918.9  2948.9
  2977.7  2997.7  3018.9  3152.4  3157.7  3172.4  3172.8  3262.4  3312.4  3392.8
  3432.4  3462.4  3542.4  3562.8  3582.8  3612.8  3622.8  3632.8  3642.4  3642.8
  3662.8  3682.8  3742.8  3762.8  3772.8  3782.8  3792.8  3942.4  4000.3  4012.8
  4160.2  4160.3  4510.3  4510.4  4517.2  4567.2  4587.2  4627.2  4647.2  4657.2
  4687.2  4717.2  4737.2  4767.2  4787.2  4807.2  4812.4  4827.2  4837.2  4847.2
  4861.2  4867.2  4885.1  4895.1  4908.9  4914.2  4927.3  4948.2    4958  4961.9
  4967.5    4987  4997.1    4998  4998.2  4999.2  5000.6  5001.9  5003.8  5015.7
  5019.8  5039.4    5047  5059.4  5071.2  5073.7  5079.5  5085.9  5105.9  5115.9
  5123.3  5125.9  5135.9  5165.9  5175.9  5195.9  5205.9  5225.9  5245.9  5265.9
    5303  5355.9  5375.9    5443    5553  5555.9  5565.9  5695.9    5773  5775.9
  5795.8  5855.8  5945.8    5963  5965.8    6143  6165.8    6173  6205.8    6213
  6225.8  6255.8  6315.8    6323    6343  6495.8  6605.1    6613  6701.6  6735.8
  6805.8  6815.8    6823    6924  6997.4    7004    7024    7034  7067.4    7094
  7097.4    7124  7147.4    7154    7174  7207.4  7267.4    7294  7327.4  7357.4
    7374    7394  7397.4    7414    7434    7464    7474  7497.4    7514    7544
    7554    7564    7574    7584    7594  7607.4    7614    7634  7637.4    7654
    7664    7674    7694  7706.6    7710  7847.3
   227.4  227.26  226.97  226.92  226.83  226.73  226.53  226.34  226.24  226.15
  226.05  225.95   225.9  225.89  225.89  225.83  225.83  225.78  225.77  225.75
  225.71   225.7   225.7  225.26   224.8   224.8     225   225.4   226.1   226.8
  227.17  227.43   227.7   230.9  231.06   231.5  231.51     233   234.3  235.77
   236.5   237.4   238.7  239.09  239.47  240.04  240.23  240.42   240.6  240.61
  240.91  241.21  242.11  242.41  242.56  242.71  242.86   245.1   245.1   245.1
   245.1   245.1   244.1   244.1  244.03  243.53  243.33  242.93  242.73  242.63
  242.33  242.02  241.82  241.52  241.32  241.12  241.07  240.84  240.68  240.52
   240.3  240.19  239.87  239.69  239.44  239.33  239.06  238.63  238.43  238.35
  238.24  237.86  237.66  237.65  237.64  237.62  237.59  237.57  237.53   237.3
  237.21   236.8  236.65  236.39  236.14  236.08  235.94  235.79  235.32  235.08
  234.91  234.88  234.75  234.36  234.23  233.98  233.85  233.59  233.33  233.08
   232.6  231.35  230.88   229.3   226.6  226.54  226.32  223.48   221.8  221.78
  221.61   221.1  220.34   220.2   220.2   219.9  219.97   219.9  219.97   219.9
  219.92  219.98  220.09   220.1   220.2  220.48  220.69   220.7  221.08  221.23
  221.53  221.57   221.6  221.89   221.5  221.48  221.42   221.4   221.3   221.3
   221.3  221.09   220.9  220.89  220.86   220.8   220.7  220.74   220.8   220.8
   220.8   220.8   220.8  220.77  220.73  220.67  220.65   220.6  220.62  220.64
  220.65  220.66  220.67  220.68  220.69   220.7  220.68  220.61   220.6   220.6
   220.6   220.6  220.68  220.85  220.89   220.5
                                                                                
                                                                                
                                                                                
                                                                                
                                                                                
                                                                                
     213   240.1   239.1     210
                                                                                
                                                                                
                     211  210.51  210.39  210.35  210.38  210.52  211.15  211.15
  211.15  211.44   211.7
                                                                                
                                                                                
                                                                                
                                                                                
                                                                                
                                                                                
                                                                                
                                                                                
                                                
  1668.9  1697.7  1757.7  1767.7  1787.7  1807.7  1847.7  1887.7  1907.7  1927.7
  1947.7  1967.7  1978.9  1987.7  1997.7  2077.7  2080.7  2157.7  2177.7  2197.7
  2257.7  2277.7  2278.9  2477.7  2688.9  2758.9  2768.9  2838.9  2918.9  2948.9
  2977.7  2997.7  3018.9  3152.4  3157.7  3172.4  3172.8  3262.4  3312.4  3392.8
  3432.4  3462.4  3542.4  3562.8  3582.8  3612.8  3622.8  3632.8  3642.4  3642.8
  3662.8  3682.8  3742.8  3762.8  3772.8  3782.8  3792.8  3942.4  4000.3  4012.8
  4160.2  4160.3  4510.3  4510.4  4517.2  4567.2  4587.2  4627.2  4647.2  4657.2
  4687.2  4717.2  4737.2  4767.2  4787.2  4807.2  4812.4  4827.2  4837.2  4847.2
  4861.2  4867.2  4885.1  4895.1  4908.9  4914.2  4927.3  4948.2    4958  4961.9
  4967.5    4987  4997.1    4998  4998.2  4999.2  5000.6  5001.9  5003.8  5015.7
  5019.8  5039.4    5047  5059.4  5071.2  5073.7  5079.5  5085.9  5105.9  5115.9
  5123.3  5125.9  5135.9  5165.9  5175.9  5195.9  5205.9  5225.9  5245.9  5265.9
    5303  5355.9  5375.9    5443    5553  5555.9  5565.9  5695.9    5773  5775.9
  5795.8  5855.8  5945.8    5963  5965.8    6143  6165.8    6173  6205.8    6213
  6225.8  6255.8  6315.8    6323    6343  6495.8  6605.1    6613  6701.6  6735.8
  6805.8  6815.8    6823    6924  6997.4    7004    7024    7034  7067.4    7094
  7097.4    7124  7147.4    7154    7174  7207.4  7267.4    7294  7327.4  7357.4
    7374    7394  7397.4    7414    7434    7464    7474  7497.4    7514    7544
    7554    7564    7574    7584    7594  7607.4    7614    7634  7637.4    7654
    7664    7674    7694  7706.6    7710  7847.3
   227.4  227.26  226.97  226.92  226.83  226.73  226.53  226.34  226.24  226.15
  226.05  225.95   225.9  225.89  225.89  225.83  225.83  225.78  225.77  225.75
  225.71   225.7   225.7  225.26   224.8   224.8     225   225.4   226.1   226.8
  227.17  227.43   227.7   230.9  231.06   231.5  231.51     233   234.3  235.77
   236.5   237.4   238.7  239.09  239.47  240.04  240.23  240.42   240.6  240.61
  240.91  241.21  242.11  242.41  242.56  242.71  242.86   245.1   245.1   245.1
   245.1   245.1   244.1   244.1  244.03  243.53  243.33  242.93  242.73  242.63
  242.33  242.02  241.82  241.52  241.32  241.12  241.07  240.84  240.68  240.52
   240.3  240.19  239.87  239.69  239.44  239.33  239.06  238.63  238.43  238.35
  238.24  237.86  237.66  237.65  237.64  237.62  237.59  237.57  237.53   237.3
  237.21   236.8  236.65  236.39  236.14  236.08  235.94  235.79  235.32  235.08
  234.91  234.88  234.75  234.36  234.23  233.98  233.85  233.59  233.33  233.08
   232.6  231.35  230.88   229.3   226.6  226.54  226.32  223.48   221.8  221.78
  221.61   221.1  220.34   220.2   220.2   219.9  219.97   219.9  219.97   219.9
  219.92  219.98  220.09   220.1   220.2  220.48  220.69   220.7  221.08  221.23
  221.53  221.57   221.6  221.89   221.5  221.48  221.42   221.4   221.3   221.3
   221.3  221.09   220.9  220.89  220.86   220.8   220.7  220.74   220.8   220.8
   220.8   220.8   220.8  220.77  220.73  220.67  220.65   220.6  220.62  220.64
  220.65  220.66  220.67  220.68  220.69   220.7  220.68  220.61   220.6   220.6
   220.6   220.6  220.68  220.85  220.89   220.5
                                                                                
                                                                                
                                                                                
                                                                                
                                                                                
                                                                                
     213   240.1   239.1     210
                                                                                
                                                                                
                  210.83  210.34  210.22  210.18  210.21  210.35  210.98  210.98
  210.98  211.27  211.53
                                                                                
                                                                                
                                                                                
                                                                                
                                                                                
                                                                                
                                                                                
                                                                                
                                                
Abutment Skew #Up #Dn= , 2 , 2
  4160.3  4220.5
   240.1     210
  4160.3  4220.5
   240.1     210
Abutment Skew #Up #Dn= , 2 , 2
  4450.1  4510.3
     210   239.1
  4450.1  4510.3
     210   239.1
BR Coef= 1 , 1 , 1 ,1.25, 0 ,,3,0.8,-1,2,0,
WSPro=,,,, 1 ,,,, 0 ,,,, 0 ,,,,-1 ,-1 ,-1 , 0 , 0 , 0 , 0 , 0
Culvert=2,5,10,500,0.015,0.5,1,8,1,210.72,4992.9,210,4992.9,Culvert #1  , 1 ,10
Culvert Bottom n=0.015
Culvert=2,5,10,500,0.015,0.4,1,8,1,210.49,5005.6,210,5005.6,Culvert #2  , 0 ,10
Culvert Bottom n=0.015
Culvert=2,5,10,500,0.015,0.4,1,8,1,210.46,5018.3,210,5018.3,Culvert #3  , 0 ,10
Culvert Bottom n=0.015
Culvert=2,5,10,500,0.015,0.4,1,8,1,210.57,5030.2,210,5030.2,Culvert #4  , 0 ,10
Culvert Bottom n=0.015
Culvert=2,5,10,500,0.015,0.4,1,8,1,210.51,5042.7,210,5042.7,Culvert #5  , 0 ,10
Culvert Bottom n=0.015
BR U #Sta/Elev= 155
  1668.9  227.62  1697.7  221.32  1757.7  221.22  1787.7  221.22  1907.7  221.02
  1987.7  221.22  2077.7  221.22  2157.7  220.62  2197.7  220.42  2277.7  220.32
  2477.7  220.22  2977.7  219.42  3157.7  218.92  3172.4  218.82  3392.8  218.62
  3562.8  218.22  3582.8  218.32  3612.8  217.52  3622.8  216.92  3632.8  216.12
  3642.4  215.83  3642.8  215.82  3662.8  217.82  3682.8  218.72  3742.8  218.72
  3762.8  217.82  3772.8  216.92  3782.8  215.82  3792.8  214.92  4012.8  213.52
  4060.3     214  4062.8  214.02  4092.8  213.52  4130.3  213.43  4132.8  213.42
  4152.8  212.92  4160.3  213.03  4180.3  213.15  4200.3  213.17  4232.8  213.82
  4242.8  215.62  4272.8  218.82  4282.8  219.32  4322.8  219.52  4352.8  218.92
  4362.8  218.92  4390.3   218.1  4392.8  218.02  4402.8  217.32  4412.8  216.12
  4430.3   213.5  4432.8  213.12  4440.3  212.59  4442.8  212.42  4452.8  212.02
  4470.3  212.28  4472.8  212.32  4482.8  212.22  4487.2  212.02  4517.2  211.62
  4567.2  211.92  4587.2  211.72  4627.2  211.82  4647.2  211.42  4657.2  211.82
  4687.2  211.42  4717.2  211.72  4737.2  211.82  4767.2  213.52  4787.2  214.02
  4807.2  213.82  4827.2  214.22  4837.2  214.92  4847.2  214.62  4867.2  214.42
  4885.1  211.16  4895.1  213.22  4914.2  214.33  4927.3   217.9  4948.2  217.91
    4958  215.49  4961.9   214.3  4967.5  212.59    4987  211.22  4997.1  211.22
    4998  210.73  4998.2  210.61  4999.2  210.57  5000.6   210.6  5001.9  210.74
  5003.8  211.37  5019.8  211.37  5039.4  211.66    5047  211.92  5059.4  212.19
  5071.2  213.44  5073.7  213.71  5105.9  214.32  5115.9  214.42  5135.9  214.52
  5165.9  214.52  5195.9  215.02  5205.9  215.22  5225.9  215.22  5245.9  215.72
  5265.9  215.72    5303  215.97  5375.9  216.22  5555.9  216.52  5775.9  216.62
  5855.8  216.52  5965.8  216.52  6165.8  216.72  6205.8  216.42  6225.8  215.92
  6255.8  216.42    6323  216.35  6325.8  216.32  6495.8  216.82  6605.1  216.92
    6613  216.67  6735.8  216.82  6805.8  216.52  6815.8  216.32    6924  215.62
    7004  214.92    7024  214.02    7034  213.82    7094  213.72    7124  213.82
    7154  214.12    7174  214.42    7294  214.72    7374  214.82    7394  213.82
    7414  214.82    7434  216.02    7464  217.22    7474  217.42    7514  216.62
    7544  215.42    7554  214.72    7564  214.22    7574  214.02    7584  214.42
    7594  215.12    7614  216.12    7634  216.72    7654  216.72    7664  216.42
    7674  215.82    7684  214.82    7694  214.82  7706.6  215.32  7847.3  220.72
BR U #Mann= 4
  1668.9      .2  2157.7     .05  4961.9     .04  5073.7     .05
BR D #Sta/Elev= 183
  1668.9  221.12  1697.7  220.92  1757.7  220.82  1767.7  221.02  1768.9  221.01
  1787.7  220.82  1807.7  220.92  1808.9  220.91  1847.7  220.62  1887.7  220.92
  1888.9   220.9  1907.7  220.62  1927.7  220.92  1947.7  220.72  1967.7  221.02
  1968.9  221.01  1987.7  220.82  1997.7  220.92  2077.7  220.82  2157.7  220.22
  2177.7  220.42  2178.9   220.4  2197.7  220.02  2198.9  220.02  2257.7  220.12
  2277.7  219.92  2508.9  219.77  2977.7  219.02  2997.7  218.82  3157.7  218.52
  3172.8  218.42  3392.8  218.22  3562.8  217.82  3582.8  217.92  3612.8  217.12
  3622.8  216.52  3630.5   215.9  3632.8  215.72  3642.8  215.42  3662.8  217.42
  3680.5  218.22  3682.8  218.32  3742.8  218.32  3762.8  217.42  3772.8  216.52
  3782.8  215.42  3792.8  214.52  4012.8  213.12  4062.8  213.62  4092.8  213.12
  4132.8  213.02  4152.8  212.52  4172.8  212.82  4192.8  212.62  4232.8  213.42
  4242.8  215.22  4272.8  218.42  4282.8  218.92  4322.8  219.12  4352.8  218.52
  4362.8  218.52  4392.8  217.62  4402.8  216.92  4412.8  215.72  4432.8  212.72
  4442.8  212.02  4452.8  211.62  4472.8  211.92  4482.8  211.82  4487.2  211.62
  4517.2  211.22  4518.4  211.23  4567.2  211.52  4568.4  211.51  4587.2  211.32
  4627.2  211.42  4628.4   211.4  4647.2  211.02  4657.2  211.42  4687.2  211.02
  4717.2  211.32  4737.2  211.42  4767.2  213.12  4787.2  213.62  4805.6  213.44
  4807.2  213.42  4827.2  213.82  4837.2  214.52  4847.2  214.22  4867.2  214.02
  4885.1  210.76  4895.1  212.82  4914.2  213.93  4927.3   217.5  4948.2  217.51
    4958  215.09  4961.9   213.9  4967.5  212.19    4987  210.82  4997.1  210.82
    4998  210.33  4998.2  210.21  4999.2  210.17  5000.6   210.2  5001.9  210.34
  5003.8  210.97  5019.8  210.97  5039.4  211.26    5047  211.52  5059.4  211.79
  5071.2  213.04  5073.7  213.31  5079.5  214.42  5085.9  214.32  5105.9  213.92
  5115.9  214.02  5125.6   214.7  5125.9  214.72  5135.6  214.14  5135.9  214.12
  5165.9  214.12  5175.9  214.72  5195.6  214.62  5195.9  214.62  5205.9  214.82
  5225.6  214.92  5225.9  214.92  5245.9  215.32  5265.9  215.32  5355.9  215.92
  5375.9  215.82  5555.9  216.12  5565.9  216.02  5695.9  216.22  5775.9  216.22
  5795.8  216.42  5855.8  216.12  5945.8  216.32  5965.8  216.12  6165.8  216.32
  6205.8  216.02  6225.8  215.62  6255.8  216.02  6315.8  216.02  6325.8  215.92
  6701.4  216.38  6701.6  216.38  6735.8  216.42  6805.8  216.12  6815.8  215.92
    6924  215.22    7004  214.52    7024  213.62    7034  213.42    7094  213.32
    7124  213.42    7154  213.72    7174  214.02    7294  214.32    7374  214.42
    7394  213.42    7414  214.42  7431.4  215.46    7434  215.62    7464  216.82
    7474  217.02    7514  216.22    7544  215.02    7554  214.32    7564  213.82
    7574  213.62  7581.4  213.92    7584  214.02    7594  214.72    7614  215.72
    7634  216.32    7654  216.32    7664  216.02    7674  215.42    7684  214.42
    7694  214.42  7706.6  214.92  7831.4  219.62
BR D #Mann= 5
  1668.9      .2  2157.7     .04  4961.9     .04  5073.7     .04  6701.6      .2
BC Design=,, 0 ,, 0 ,,,,,,
BC HTab HWMax=227.62
BC Use User HTab Curves=0
BC User HTab FreeFlow(D)= 0

Type RM Length L Ch R = 1 ,112271.4,177.1,180.4,157.9
BEGIN DESCRIPTION:
Downstream Section of Bridge/Culvert/Weir
END DESCRIPTION:
XS GIS Cut Line= 6
     2965250.339   13937924.4171    2966614.9355   13937322.1651
    2967282.1553   13936799.0041    2967700.6295   13936279.2606
    2968078.2699   13935767.8462    2969453.0894    13933636.876
#Sta/Elev= 30
  1668.9  221.12  2157.7  220.22  3582.8  217.92  3642.8  215.42  3682.8  218.32
  3742.8  218.32  3792.8  214.52  4152.8  212.52  4232.8  213.42  4272.8  218.42
  4322.8  219.12  4392.8  217.62  4452.8  211.62  4687.2  211.02  4837.2  214.52
  4867.2  214.02  4885.1  210.76  4927.3   217.5  4948.2  217.51  4961.9   213.9
  4999.2  210.17  5073.7  213.31  5355.9  215.92  6701.6  216.38    7394  213.42
    7474  217.02    7574  213.62    7634  216.32    7694  214.42  7831.4  219.62
#Mann= 5 ,-1 , 0
  1668.9      .2       0  2157.7     .04       0  4961.9    .045       0
  5073.7     .04       0  6701.6      .2       0
#XS Ineff= 2 , 0
       0    4936   219.7    5200       0   219.7
Permanent Ineff=
       F       F
Bank Sta=4961.9,5073.7
XS Rating Curve= 0 ,0
Exp/Cntr=0.5,0.3

Type RM Length L Ch R = 1 ,112091.0,300,337.3,400
BEGIN DESCRIPTION:
Cross Section XS114
END DESCRIPTION:
XS GIS Cut Line= 2
     2967004.446   13937661.4271    2969426.0735   13933916.5528
#Sta/Elev= 30
  3227.9   218.6  3507.9   217.8  3567.9   219.2  3687.9   217.5  3827.9   219.4
  3857.9   218.2  3887.9   214.5  3927.9   212.1  4057.9   213.3  4087.9   214.6
  4117.9   217.7  4167.9   218.5  4197.9     218  4237.9   214.3  4347.9   213.1
  4637.9   213.1  4860.6  215.96  4923.6  214.53  4987.3     212  4993.7  210.16
  5006.4  209.98    5026  215.05  5887.9   215.6  5947.9   216.1  5977.9   214.5
  6157.9   218.6  6247.9   218.6  6387.9   216.3  7127.9   215.8  7687.5   216.4
#Mann= 7 ,-1 , 0
  3227.9      .2       0  3507.9    .095       0  3887.9     .05       0
  4923.6    .045       0    5026     .05       0  5887.9    .045       0
  7127.9      .2       0
#XS Ineff= 2 ,-1
  3227.9    4860   219.5    5336  7687.5   219.5
Permanent Ineff=
       F       F
Bank Sta=4923.6,5026
XS Rating Curve= 0 ,0
Exp/Cntr=0.3,0.1

Type RM Length L Ch R = 1 ,111753.7,651.4,626.5,613.4
BEGIN DESCRIPTION:
Cross Section XS113.5 **Note**
A blocked obstruction was used in lieu of a permanent ineffective flow area due to the flow area cacluation error in RAS version 3.01.
END DESCRIPTION:
XS GIS Cut Line= 3
       2967831.5    13937245.878     2967931.377    13936732.226
     2969201.238    13935198.406
#Sta/Elev= 30
  4091.2   216.9  4121.2   217.3  4211.2   216.8  4371.2   217.1  4401.2   216.5
  4481.2   216.7  4624.5     216  4674.5   214.9  4814.5   214.8  4862.2  215.56
  4946.7  213.66  4987.3  211.65  4993.7  209.81  5006.4  209.63  5019.8  213.91
  5031.8  215.44  5084.5     215  5464.5   215.2  5524.5   213.8  5554.5     214
  5854.5   210.5  5864.5   210.8  5914.5   215.2  5924.5   215.6  6194.5   215.5
  6284.5     216  6314.5   215.4  6364.5   215.4  6444.5   216.2  6605.7   216.3
#Mann= 5 ,-1 , 0
  4091.2    .095       0  4624.5     .05       0  4946.7    .045       0
  5019.8     .05       0  6605.7      .2       0
#XS Ineff= 4 ,-1
  4091.2    4624     219    4624    4860   215.6    5464    5925   215.2
    5925  6605.7     219
Permanent Ineff=
       F       F       T       F
#Block Obstruct= 2 , 0
       0                    5464       0   215.2
Bank Sta=4946.7,5019.8
XS Rating Curve= 0 ,0
Exp/Cntr=0.3,0.1

Type RM Length L Ch R = 1 ,111127.2,1227.8,1347.3,1234.9
BEGIN DESCRIPTION:
Cross Section XS113 **Note**
A blocked obstruction was used in lieu of a permanent ineffective flow area due to the flow area cacluation error in RAS version 3.01.
END DESCRIPTION:
XS GIS Cut Line= 2
     2968070.999   13937670.0851    2969354.8793   13935803.8264
#Sta/Elev= 30
  3956.4   216.8  4286.4   216.7  4306.4   216.1  4456.4   215.8  4496.4   214.9
  4566.4   214.6  4586.4   214.8  4616.4   214.6  4636.4   213.9  4746.4   213.6
  4806.4   213.9  4860.6  214.95  4946.7     213  4987.3  210.99  4993.7  209.15
  5006.4  208.97  5009.5  209.77  5012.7  211.04  5019.8  213.25  5031.8  214.78
  5054.4  214.68  5066.4   212.9  5076.4   210.2  5786.4   210.6  5836.4   210.1
  5886.4   213.7  5906.4   214.9  5936.4   215.6  6206.4   216.1  6221.6   215.8
#Mann= 4 ,-1 , 0
  3956.4     .05       0  4946.7    .045       0  5019.8     .05       0
  6221.6      .2       0
#XS Ineff= 2 , 0
       0    4860     215    5054       0   214.8
Permanent Ineff=
       F       T
#Block Obstruct= 2 , 0
       0                    5054       0   214.8
Bank Sta=4946.7,5019.8
XS Rating Curve= 0 ,0
Exp/Cntr=0.3,0.1

Type RM Length L Ch R = 1 ,109779.9,1041.7,999.3,823.1
BEGIN DESCRIPTION:
Cross Section XS112
END DESCRIPTION:
XS GIS Cut Line= 3
      2968998.52   13938495.4519      2970006.62      13936904.9
     2970094.237     13935982.95
#Sta/Elev= 30
  4039.6   217.1  4209.6   215.9  4269.6   216.1  4319.6   215.1  4549.6     214
  4599.6   213.1  4889.6   213.2  4919.6   214.1  4959.6     214  4972.8  212.97
  4982.2  210.84  4991.4   209.1  5014.1  209.75  5033.6  214.57  5050.9  215.13
  5079.6     215  5139.6   213.4  5169.6   213.2  5199.6   213.7  5449.6   213.6
  5499.6   213.1  5619.6   214.1  5922.7   215.3  6022.7   215.7  6082.7   215.2
  6112.7   214.1  6262.7   214.9  6462.7   214.6  6652.7   215.7  6848.8   215.6
#Mann= 7 ,-1 , 0
  4039.6     .05       0  4889.6      .1       0  4919.6    .045       0
  4982.2      .1       0  5033.6     .05       0  5922.7     .09       0
  6848.8      .2       0
#XS Ineff= 2 , 0
       0    4940   214.2               0
Permanent Ineff=
       F       F
Bank Sta=4972.8,5033.6
XS Rating Curve= 0 ,0
Exp/Cntr=0.3,0.1

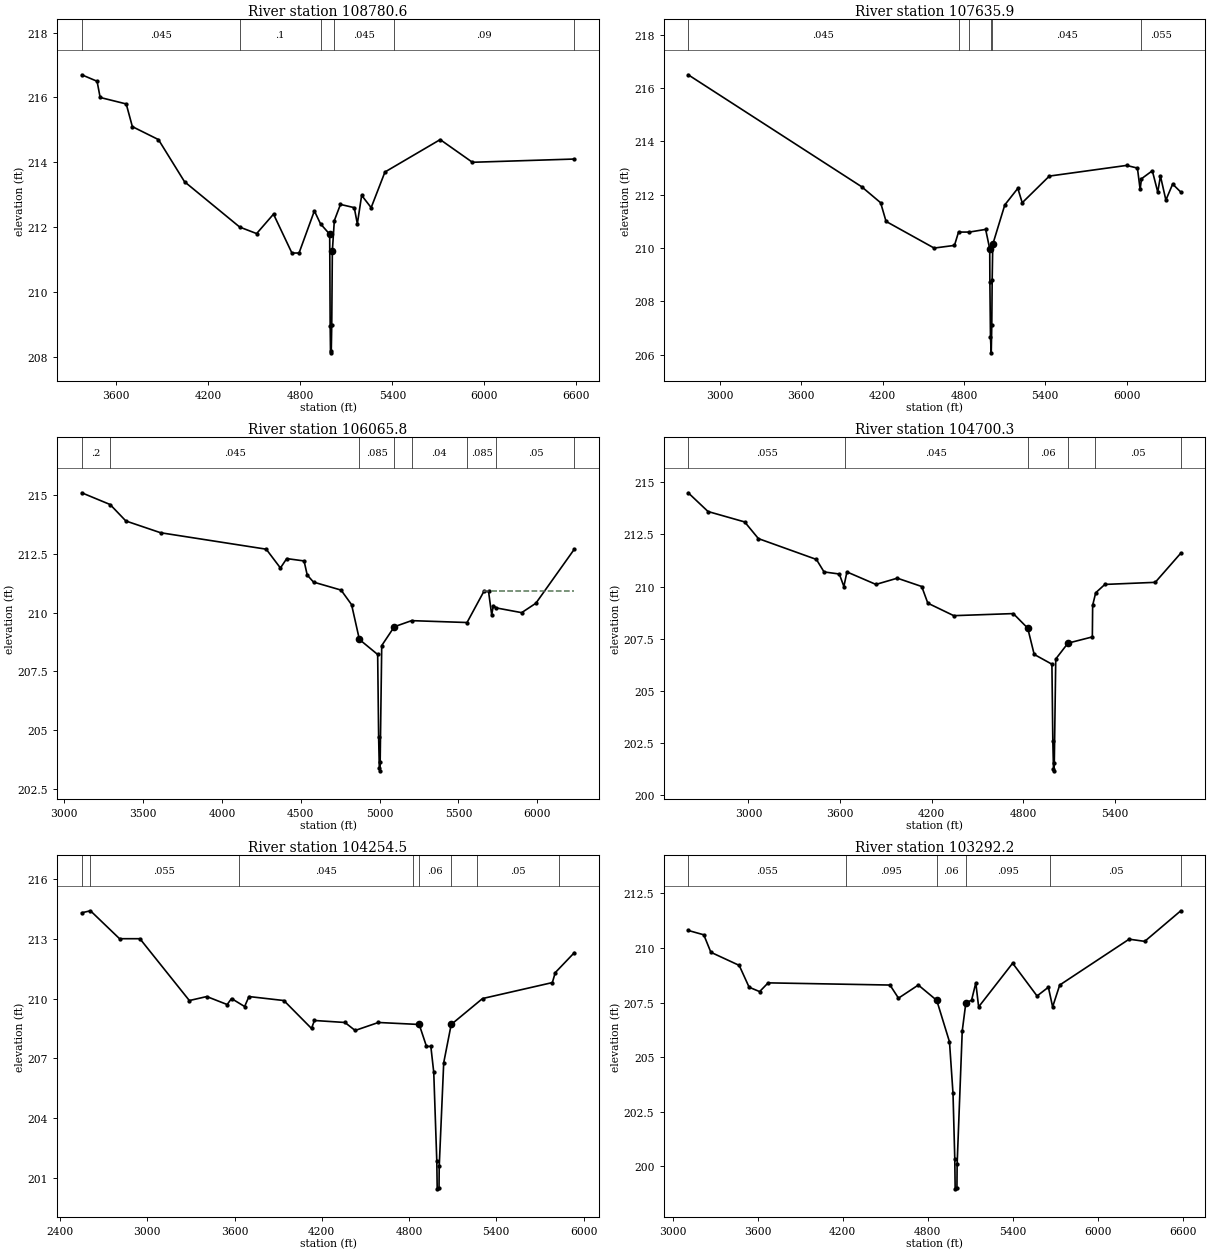
Type RM Length L Ch R = 1 ,108780.6,959.2,1144.7,1093
BEGIN DESCRIPTION:
Cross Section XS111
END DESCRIPTION:
XS GIS Cut Line= 4
     2970044.845   13939215.7461    2970446.6936   13937888.8884
    2970477.0217   13936493.7924     2970486.344    13936064.953
#Sta/Elev= 30
  3375.6   216.7  3475.6   216.5  3495.6     216  3665.6   215.8  3705.6   215.1
  3875.6   214.7  4045.6   213.4  4405.6     212  4515.6   211.8  4625.6   212.4
  4745.6   211.2    4792   211.2    4892   212.5    4932   212.1  4991.8  211.78
  4994.9  208.94  4997.2  208.12  5002.1  208.17  5005.2  208.99  5009.1  211.26
    5022   212.2    5062   212.7    5152   212.6    5172   212.1  5200.1  212.98
    5262   212.6    5352   213.7    5712   214.7    5922     214  6586.3   214.1
#Mann= 6 ,-1 , 0
  3375.6    .045       0  4405.6      .1       0    4932    .055       0
    5022    .045       0    5412     .09       0  6586.3      .2       0
Bank Sta=4991.8,5009.1
XS Rating Curve= 0 ,0
Exp/Cntr=0.3,0.1

Type RM Length L Ch R = 1 ,107635.9,1108.9,1570.1,1037.1
BEGIN DESCRIPTION:
Cross Section XS110
END DESCRIPTION:
XS GIS Cut Line= 4
     2970219.232   13939678.2507    2971386.4704   13938288.6815
    2971760.4656   13936846.3647    2971843.2923   13936526.9427
#Sta/Elev= 30
  2765.5   216.5  4045.5   212.3  4185.5   211.7  4225.5     211  4580.3     210
  4730.3   210.1  4760.3   210.6  4840.3   210.6  4960.3   210.7  4990.5  209.97
  4991.6  208.73  4995.9  206.66  5001.7  206.07  5005.7  207.12  5008.5  208.79
  5012.9  210.14  5101.8  211.62  5197.7  212.24  5230.3   211.7  5430.3   212.7
  6000.3   213.1  6080.3     213  6100.3   212.2  6110.3   212.6  6190.3   212.9
  6230.3   212.1  6250.3   212.7  6290.3   211.8  6340.3   212.4  6400.3   212.1
#Mann= 6 ,-1 , 0
  2765.5    .045       0  4760.3      .1       0  4840.3    .055       0
  5001.7      .1       0  5005.7    .045       0  6110.3    .055       0
Bank Sta=4990.5,5012.9
XS Rating Curve= 0 ,0
Exp/Cntr=0.3,0.1

Type RM Length L Ch R = 1 ,106065.8,1016.5,1365.5,588.9
BEGIN DESCRIPTION:
Cross Section XS109
END DESCRIPTION:
XS GIS Cut Line= 2
     2972228.474   13940618.4241    2972251.2199   13937494.6222
#Sta/Elev= 30
  3111.1   215.1  3291.1   214.6  3391.1   213.9  3611.1   213.4  4281.1   212.7
  4371.1   211.9  4411.1   212.3  4521.1   212.2  4541.1   211.6  4581.1   211.3
  4755.8  210.96  4822.4  210.34  4871.9  208.86 4987.87  208.22    4994  204.71
  4998.3  203.37  5001.8  203.27  5003.7  203.66 5013.64   208.6  5093.2   209.4
  5203.1  209.66  5554.6  209.58  5661.1   210.9  5691.1   210.9  5711.1   209.9
  5721.1   210.3  5741.1   210.2  5901.1     210  5991.1   210.4    6235   212.7
#Mann= 8 ,-1 , 0
  3111.1      .2       0  3291.1    .045       0  4871.9    .085       0
  5093.2     .06       0  5203.1     .04       0  5554.6    .085       0
  5741.1     .05       0    6235      .2       0
#XS Ineff= 2 , 0
       0                    5660       0   210.9
Permanent Ineff=
       F       F
Bank Sta=4871.9,5093.2
XS Rating Curve= 0 ,0
Exp/Cntr=0.3,0.1

Type RM Length L Ch R = 1 ,104700.3,313,445.8,362.2
BEGIN DESCRIPTION:
Cross Section XS108
END DESCRIPTION:
XS GIS Cut Line= 2
     2974048.164   13940307.5603    2972387.6967   13937540.1144
#Sta/Elev= 30
    2605   214.5    2735   213.6    2975   213.1    3065   212.3    3445   211.3
    3495   210.7    3595   210.6    3625     210    3645   210.7    3835   210.1
    3975   210.4    4135     210    4175   209.2    4345   208.6    4735   208.7
  4829.6     208  4871.9  206.74 4988.05  206.27    4994  202.59  4998.3  201.25
  5001.8  201.15  5003.7  201.54 5013.19  206.52  5093.2  207.28  5252.9  207.58
    5255   209.1    5275   209.7    5335   210.1    5665   210.2  5832.4   211.6
#Mann= 6 ,-1 , 0
    2605    .055       0  3631.9    .045       0  4829.6     .06       0
  5093.2    .085       0  5269.2     .05       0  5832.4      .2       0
Bank Sta=4829.6,5093.2
XS Rating Curve= 0 ,0
Exp/Cntr=0.3,0.1

Type RM Length L Ch R = 1 ,104254.5,1120,962.3,237.2
BEGIN DESCRIPTION:
Cross Section XS107
END DESCRIPTION:
XS GIS Cut Line= 4
     2974372.753   13940166.2421    2973153.1723   13938262.7841
    2973079.0856   13937966.4374    2972400.5356   13937504.2304
#Sta/Elev= 30
  2549.5   214.3  2609.5   214.4  2809.5     213  2949.5     213  3289.5   209.9
  3409.5   210.1  3549.5   209.7  3579.5     210  3669.5   209.6  3699.5   210.1
  3939.5   209.9  4129.5   208.5  4149.5   208.9  4359.5   208.8  4429.5   208.4
  4589.5   208.8  4870.1   208.7  4920.1   207.6  4950.1   207.6  4970.1   206.3
  4991.1  201.84  4993.8  200.46  5006.3  200.48  5007.7  201.58  5038.6  206.78
  5090.1   208.7  5305.6     210  5785.6   210.8  5805.6   211.3  5936.7   212.3
#Mann= 8 ,-1 , 0
  2549.5      .2       0    2605    .055       0  3631.9    .045       0
  4829.6    .085       0  4870.1     .06       0  5090.1    .085       0
  5269.2     .05       0  5832.4      .2       0
Bank Sta=4870.1,5090.1
XS Rating Curve= 0 ,0
Exp/Cntr=0.3,0.1

Type RM Length L Ch R = 1 ,103292.2,56.7,56.7,56.7
BEGIN DESCRIPTION:
Cross Section Bauer-Hockley-US_Con
END DESCRIPTION:
XS GIS Cut Line= 5
     2975722.834   13938548.2787    2975302.9693   13938328.0892
    2973824.1256   13938185.0821    2973453.1057   13938155.6285
    2972502.2704   13937518.5998
#Sta/Elev= 30
  3109.7   210.8  3219.7   210.6  3269.7   209.8  3469.7   209.2  3539.7   208.2
  3613.8     208  3673.8   208.4  4533.8   208.3  4593.8   207.7  4733.8   208.3
  4863.8   207.6  4953.8   205.7  4978.6  203.34  4991.1  200.35  4993.8  198.97
  5006.3  198.99  5007.7  200.09  5043.8   206.2  5069.5   207.5  5109.5   207.6
  5139.5   208.4  5159.5   207.3  5399.5   209.3  5571.7   207.8  5651.7   208.2
  5681.7   207.3  5731.7   208.3  6221.7   210.4  6331.7   210.3  6586.2   211.7
#Mann= 6 ,-1 , 0
  3109.7    .055       0  4221.8    .095       0  4863.8     .06       0
  5069.5    .095       0  5665.7     .05       0  6586.2      .2       0
Bank Sta=4863.8,5069.5
XS Rating Curve= 0 ,0
Exp/Cntr=0.5,0.3

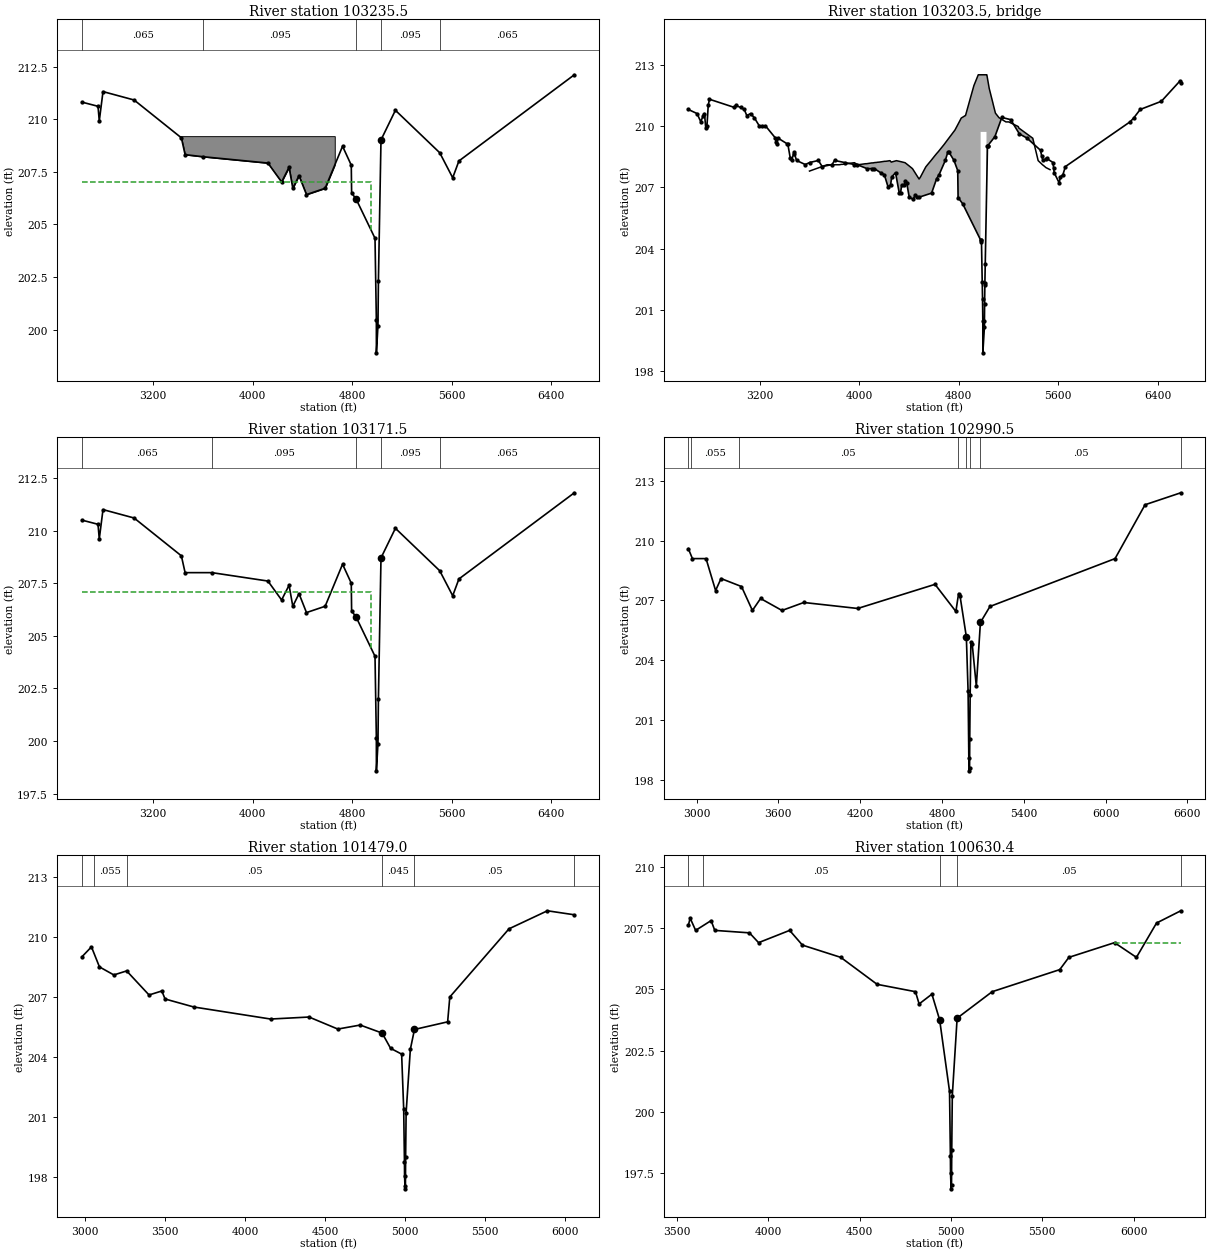
Type RM Length L Ch R = 1 ,103235.5,64,64,64
BEGIN DESCRIPTION:
Upstream Section of Bridge/Culvert/Weir
END DESCRIPTION:
XS GIS Cut Line= 6
     2976181.685   13938732.4554    2975317.5237   13938279.2634
    2973828.5107   13938135.2729    2973470.0837    13938106.819
    2973261.1058   13937966.8106     2972533.218    13937479.149
#Sta/Elev= 30
  2625.9  210.82  2755.9  210.62  2765.9  209.92  2795.9  211.32  3045.9  210.92
  3425.9  209.12  3455.9  208.32  3601.7  208.22  4121.7  207.92  4231.7  207.02
  4291.7  207.72  4321.7  206.72  4371.7  207.32  4431.7  206.42  4581.7  206.72
  4721.7  208.72  4791.7  207.82  4794.6   206.5  4831.2   206.2  4982.6  204.34
  4993.4  200.46  4993.7  198.89  5006.3  200.17    5010  202.32  5030.7  209.02
  5146.5  210.43  5502.9  208.41  5607.2  207.22  5657.2  208.02  6584.9  212.12
#Mann= 5 ,-1 , 0
  2625.9    .065       0  3601.7    .095       0  4831.2     .06       0
  5030.7    .095       0  5502.9    .065       0
#XS Ineff= 2 , 0
       0    4950     207    5050       0     207
Permanent Ineff=
       F       F
#Block Obstruct= 2 , 0
       0    4659   209.2    5371       0   209.2
Bank Sta=4831.2,5030.7
XS Rating Curve= 0 ,0
Skew Angle= 30
Exp/Cntr=0.5,0.3

Type RM Length L Ch R = 3 ,103203.5,,,
BEGIN DESCRIPTION:
BAUER-HOCKLEY
Structure ID: L100-00-00-S10
END DESCRIPTION:
Bridge Culvert--1,0,-1,-1, 0
Deck Dist Width WeirC Skew NumUp NumDn MinLoCord MaxHiCord MaxSubmerge Is_Ogee
10,44,2.6,30, 99, 99, , , 0.95, 0, 1,1,,
    3600 3741.43 3750.87 3759.53 3768.19 3772.35 3840.07 3858.95 3867.61 3884.93
 3893.59 3910.91 3961.31 3971.53 3987.29 3988.85 4014.83 4049.48 4058.14 4101.44
  4110.1 4127.42 4136.08 4143.87 4162.06 4205.36 4214.02  4247.1 4257.32 4299.06
 4335.26 4368.35 4387.22 4421.87 4428.97 4465.17 4480.93 4491.15 4534.45 4550.21
 4576.19 4602.17 4619.49 4636.81 4681.67 4714.76  4749.4 4766.72 4768.28 4784.04
  4792.7 4801.36 4810.02 4818.25 4820.24 4849.94 4854.19 4891.68 4921.65 4956.81
 4975.78 4975.86 4977.94 4981.06 4986.25 4988.42 4990.41 4990.67 5001.58 5001.76
  5002.8 5004.61 5004.79 5007.21 5022.71 5023.57 5023.67 5025.75 5044.88 5074.68
 5077.27 5094.77    5123 5146.56 5178.86 5201.55  5278.8 5282.78 5395.02 5397.01
 5431.65 5438.32 5440.31 5448.97 5457.63 5472.96 5483.61 5500.93 5533.58
   207.8  208.11  208.11  208.11  208.11  208.11  208.11  208.13  208.13  208.15
  208.15  208.17  208.21  208.17  208.11  208.11  208.13  208.16  208.16   208.2
   208.2  208.22  208.22  208.23  208.24  208.28  208.28  208.31  208.24  208.31
  208.26  208.21  208.12  207.95  207.91  207.56  207.41   207.5     208  208.12
  208.31  208.51  208.64  208.76   209.1  209.37  209.65  209.79   209.8  209.98
  210.08  210.18  210.28  210.38   210.4  210.51  210.52  211.34  211.99  212.52
  212.52  212.52  212.52  212.52  212.52  212.52  212.52  212.52  212.52  212.52
  212.52  212.52  212.52  212.52  212.52  212.52  212.52  212.52  211.85  211.13
  211.06  210.64  210.42  210.33  210.21  210.21  209.98  209.91  209.41  209.36
  208.48  208.31   208.3  208.25   208.2  208.11  208.06  207.97  207.87
                                                                                
                                                                                
                                                                                
                                                                                
                                                                                
                                                                                
     204  209.72  209.72  209.72  209.72  209.72  209.72  209.72  209.72  209.72
  209.72  209.72  209.72  209.72  209.72     204
                                                                                
                                                                        
    3600 3741.43 3750.87 3759.53 3768.19 3772.35 3840.07 3858.95 3867.61 3884.93
 3893.59 3910.91 3961.31 3971.53 3987.29 3988.85 4014.83 4049.48 4058.14 4101.44
  4110.1 4127.42 4136.08 4143.87 4162.06 4205.36 4214.02  4247.1 4257.32 4299.06
 4335.26 4368.35 4387.22 4421.87 4428.97 4465.17 4480.93 4491.15 4534.45 4550.21
 4576.19 4602.17 4619.49 4636.81 4681.67 4714.76  4749.4 4766.72 4768.28 4784.04
  4792.7 4801.36 4810.02 4818.25 4820.24 4849.94 4854.19 4891.68 4921.65 4956.81
 4975.78 4975.86 4977.94 4981.06 4986.25 4988.42 4990.41 4990.67 5001.58 5001.76
  5002.8 5004.61 5004.79 5007.21 5022.71 5023.57 5023.67 5025.75 5044.88 5074.68
 5077.27 5094.77    5123 5146.56 5178.86 5201.55  5278.8 5282.78 5395.02 5397.01
 5431.65 5438.32 5440.31 5448.97 5457.63 5472.96 5483.61 5500.93 5533.58
   207.8  208.11  208.11  208.11  208.11  208.11  208.11  208.13  208.13  208.15
  208.15  208.17  208.21  208.17  208.11  208.11  208.13  208.16  208.16   208.2
   208.2  208.22  208.22  208.23  208.24  208.28  208.28  208.31  208.24  208.31
  208.26  208.21  208.12  207.95  207.91  207.56  207.41   207.5     208  208.12
  208.31  208.51  208.64  208.76   209.1  209.37  209.65  209.79   209.8  209.98
  210.08  210.18  210.28  210.38   210.4  210.51  210.52  211.34  211.99  212.52
  212.52  212.52  212.52  212.52  212.52  212.52  212.52  212.52  212.52  212.52
  212.52  212.52  212.52  212.52  212.52  212.52  212.52  212.52  211.85  211.13
  211.06  210.64  210.42  210.33  210.21  210.21  209.98  209.91  209.41  209.36
  208.48  208.31   208.3  208.25   208.2  208.11  208.06  207.97  207.87
                                                                                
                                                                                
                                                                                
                                                                                
                                                                                
                                                                                
     204  209.44  209.44  209.44  209.44  209.44  209.44  209.44  209.44  209.44
  209.44  209.44  209.44  209.44  209.44     204
                                                                                
                                                                        
Abutment Skew #Up #Dn= , 2 , 2
 4975.69 4993.27
  209.72     198
 4975.69 4992.85
  209.44     198
Abutment Skew #Up #Dn= , 2 , 2
 5005.99 5023.57
     198  209.72
 5006.41 5023.57
     198  209.44
BR Coef= 1 , 1 , 0 ,1.25, 0 ,,,0.8,-1,2,0,
WSPro=,,,, 1 ,,,, 0 ,,,, 0 ,,,,-1 ,-1 ,-1 , 0 , 0 , 0 , 0 , 0
BR U #Sta/Elev= 108
  2625.9  210.82  2695.9  210.62  2725.9  210.22  2745.9  210.52  2755.9  210.62
  2765.9  209.92  2775.9  210.02  2785.9  211.02  2795.9  211.32  2995.9  210.92
  3005.9  211.02  3045.9  210.92  3075.9  210.82  3095.9  210.52  3125.9  210.62
  3155.9  210.42  3195.9  210.02  3215.9  210.02  3245.9  210.02  3325.9  209.42
  3332.1  209.23  3335.9  209.12  3345.9  209.42  3422.1  209.13  3425.9  209.12
  3445.9  208.42  3455.9  208.32  3472.1  208.64  3475.9  208.72  3495.9  208.32
  3565.9  208.12  3601.7  208.22  3671.7  208.32  3701.7  208.02  3781.7  208.12
  3801.7  208.32  3881.7  208.22  3961.7  208.12  3981.7  208.12  4061.7  207.92
  4101.7  207.92  4121.7  207.92  4171.7  207.72  4201.7  207.62  4231.7  207.02
  4251.7  207.12  4261.7  207.52  4291.7  207.72  4321.7  206.72  4331.7  206.72
  4341.7  207.12  4361.7  207.12  4371.7  207.32  4381.7  207.22  4401.7  206.52
  4431.7  206.42  4451.7  206.62  4461.7  206.52  4481.7  206.52  4581.7  206.72
  4621.7  207.42  4641.7  207.62  4691.7  208.32  4711.7  208.72  4721.7  208.72
  4761.7  208.32  4791.7  207.82  4794.6   206.5  4831.2   206.2 4976.51  204.41
  4976.6  204.41  4982.6  204.34  4988.6  202.36  4991.1  201.53  4993.4  200.46
  4993.7  198.89  5006.3  200.17  5006.5  200.44  5007.7  201.27  5009.8  202.23
    5010  202.32  5012.8  203.23  5030.7  209.02 5031.69  209.03  5031.8  209.03
  5090.7  209.49  5146.5  210.43  5217.6  210.32  5287.6  209.62  5347.6  209.42
  5457.2  208.82  5467.2  208.52  5477.2  208.32  5502.9  208.41  5507.2  208.42
  5557.2  208.22  5562.9  207.94  5567.2  207.72  5607.2  207.22  5617.2  207.52
  5637.2  207.62  5657.2  208.02  6178.7  210.22  6208.7  210.42  6258.7  210.82
  6428.7  211.22  6578.7  212.22  6584.9  212.12
BR U #Mann= 5
  2625.9    .065  3601.7    .095  4831.2    .055  5030.7    .095  5502.9    .065
BR D #Sta/Elev= 109
  2625.9  210.51  2695.9  210.31  2725.9  209.91  2745.9  210.21  2755.9  210.31
  2765.9  209.61  2775.9  209.71  2785.9  210.71  2795.9  211.01  2995.9  210.61
  3025.9  210.31  3045.9  210.61  3075.9  210.51  3125.9  210.31  3145.9  210.01
  3195.9  209.71  3215.9  209.71  3245.9  209.71  3325.9  209.11  3332.1  208.92
  3335.9  208.81  3345.9  209.11  3422.1  208.82  3425.9  208.81  3445.9  208.11
  3455.9  208.01  3472.1  208.33  3475.9  208.41  3515.9  208.11  3565.9  207.81
  3601.7  207.91  3671.7  208.01  3701.7  207.71  3781.7  207.81  3801.7  208.01
  3881.7  207.91  3961.7  207.81  3981.7  207.81  4061.7  207.61  4101.7  207.61
  4121.7  207.61  4171.7  207.41  4201.7  207.31  4231.7  206.71  4251.7  206.81
  4261.7  207.21  4291.7  207.41  4321.7  206.41  4331.7  206.41  4341.7  206.81
  4361.7  206.81  4371.7  207.01  4381.7  206.91  4401.7  206.21  4431.7  206.11
  4451.7  206.31  4461.7  206.21  4481.7  206.21  4581.7  206.41  4621.7  207.11
  4641.7  207.31  4691.7  208.01  4711.7  208.41  4721.7  208.41  4731.7  207.91
  4761.7  208.01  4791.7  207.51  4794.6  206.19  4831.2  205.89 4976.51   204.1
  4976.6   204.1  4982.6  204.03  4988.6  202.05  4991.1  201.22  4993.4  200.15
  4993.7  198.58  5006.3  199.86  5006.5  200.13  5007.7  200.96  5009.8  201.92
    5010  202.01  5012.8  202.92  5030.7  208.71 5031.69  208.72  5031.8  208.72
  5090.7  209.18  5146.5  210.12  5217.6  210.01  5307.6  209.41  5347.6  209.11
  5377.6  209.31  5457.2  208.51  5467.2  208.21  5477.2  208.01  5502.9   208.1
  5507.2  208.11  5557.2  207.91  5562.9  207.63  5567.2  207.41  5607.2  206.91
  5617.2  207.21  5637.2  207.31  5657.2  207.71  6178.7  209.91  6208.7  210.11
  6258.7  210.51  6428.7  210.91  6578.7  211.91  6584.9  211.81
BR D #Mann= 5
  2625.9    .065  3671.7    .095  4831.2    .055  5030.7    .095  5502.9    .065
BC Design=,, 0 ,, 0 ,,,,,,
BC HTab HWMax=212.02
BC Use User HTab Curves=0
BC User HTab FreeFlow(D)= 0

Type RM Length L Ch R = 1 ,103171.5,150.7,181,215.9
BEGIN DESCRIPTION:
Downstream Section of Bridge/Culvert/Weir
END DESCRIPTION:
XS GIS Cut Line= 6
     2976237.547   13938592.1209    2975367.4195   13938179.9551
    2974917.6506   13938166.9561    2973492.5201   13938041.4488
    2973294.0563   13937907.3284     2972564.391    13937414.226
#Sta/Elev= 30
  2625.9  210.51  2755.9  210.31  2765.9  209.61  2795.9  211.01  3045.9  210.61
  3425.9  208.81  3455.9  208.01  3671.7  208.01  4121.7  207.61  4231.7  206.71
  4291.7  207.41  4321.7  206.41  4371.7  207.01  4431.7  206.11  4581.7  206.41
  4721.7  208.41  4791.7  207.51  4794.6  206.19  4831.2  205.89  4982.6  204.03
  4993.4  200.15  4993.7  198.58  5006.3  199.86    5010  202.01  5030.7  208.71
  5146.5  210.12  5502.9   208.1  5607.2  206.91  5657.2  207.71  6584.9  211.81
#Mann= 5 ,-1 , 0
  2625.9    .065       0  3671.7    .095       0  4831.2     .06       0
  5030.7    .095       0  5502.9    .065       0
#XS Ineff= 2 , 0
       0    4950   207.1    5050       0   207.1
Permanent Ineff=
       F       F
Bank Sta=4831.2,5030.7
XS Rating Curve= 0 ,0
Skew Angle= 30
Exp/Cntr=0.5,0.3

Type RM Length L Ch R = 1 ,102990.5,491.1,1511.5,1097.7
BEGIN DESCRIPTION:
Cross Section Bauer-Hockley-DS_Exp
END DESCRIPTION:
XS GIS Cut Line= 5
     2976023.233   13938323.8587    2975389.8496   13938057.9608
    2974926.4045   13938017.1465    2973544.3468   13937895.4325
    2972656.0518   13937295.1289
#Sta/Elev= 30
  2939.9   209.6  2969.9   209.1  3069.9   209.1  3139.9   207.5  3179.9   208.1
  3329.9   207.7  3409.9   206.5  3469.9   207.1  3626.8   206.5  3786.8   206.9
  4182.1   206.6  4749.1  207.81  4902.1  206.45  4922.1  207.35  4932.1  207.25
  4978.9  205.18  4991.7  202.44  4997.1  199.12  5000.4  198.46  5002.6   198.6
  5003.8  200.04  5006.9  202.26  5012.1   204.9  5022.1   204.8  5052.1   202.7
  5082.1   205.9  5152.1   206.7  6069.5   209.1  6289.5   211.8  6551.6   212.4
#Mann= 8 ,-1 , 0
  2939.9      .2       0  2957.7    .055       0  3309.2     .05       0
  4916.6     .09       0  4978.9     .06       0  5003.8     .09       0
  5082.1     .05       0  6551.6      .2       0
Bank Sta=4978.9,5082.1
XS Rating Curve= 0 ,0
Exp/Cntr=0.3,0.1

Type RM Length L Ch R = 1 ,101479.0,472.4,848.6,656
BEGIN DESCRIPTION:
Cross Section XS105
END DESCRIPTION:
XS GIS Cut Line= 3
     2976075.573   13938288.8434      2975033.83   13937850.9782
    2973593.2417   13936539.2847
#Sta/Elev= 30
    2980     209    3040   209.5    3090   208.5    3180   208.1    3260   208.3
    3400   207.1    3480   207.3    3500   206.9    3680   206.5    4160   205.9
    4400     206    4580   205.4    4720   205.6  4856.9   205.2  4909.8  204.44
  4978.9  204.15  4991.7  201.41  4996.5  198.75  4997.1  198.09  5000.4  197.43
  5002.6  197.57  5003.8  199.01  5006.9  201.23  5033.3  204.39  5059.1  205.38
  5266.4  205.76    5280     207    5650   210.4    5890   211.3  6058.3   211.1
#Mann= 6 ,-1 , 0
    2980      .2       0  3052.9    .055       0    3260     .05       0
  4856.9    .045       0  5059.1     .05       0  6058.3      .2       0
Bank Sta=4856.9,5059.1
XS Rating Curve= 0 ,0
Exp/Cntr=0.3,0.1

Type RM Length L Ch R = 1 ,100630.4,646.5,911.1,737.2
BEGIN DESCRIPTION:
Cross Section XS104
END DESCRIPTION:
XS GIS Cut Line= 4
     2976072.366    13938171.023     2975976.612   13938090.9212
    2975394.3758   13937603.8631    2974154.3129   13936281.4952
#Sta/Elev= 30
  3561.3   207.6  3571.3   207.9  3601.3   207.4  3686.1   207.8  3706.1   207.4
  3896.1   207.3  3946.1   206.9  4116.1   207.4  4186.1   206.8  4396.1   206.3
  4595.2   205.2  4805.2   204.9  4825.2   204.4  4895.2   204.8  4937.6  203.75
  4991.7  200.84  4996.5  198.18  4997.1  197.52  5000.4  196.86  5002.6     197
  5003.8  198.44  5006.9  200.66  5033.3  203.82  5225.2   204.9  5595.2   205.8
  5645.2   206.3  5895.2   206.9  6015.2   206.3  6125.2   207.7  6258.1   208.2
#Mann= 5 ,-1 , 0
  3561.3    .065       0  3639.8     .05       0  4937.6    .045       0
  5033.3     .05       0  6258.1      .2       0
#XS Ineff= 2 , 0
       0                    5894       0   206.9
Permanent Ineff=
       F       F
Bank Sta=4937.6,5033.3
XS Rating Curve= 0 ,0
Exp/Cntr=0.3,0.1