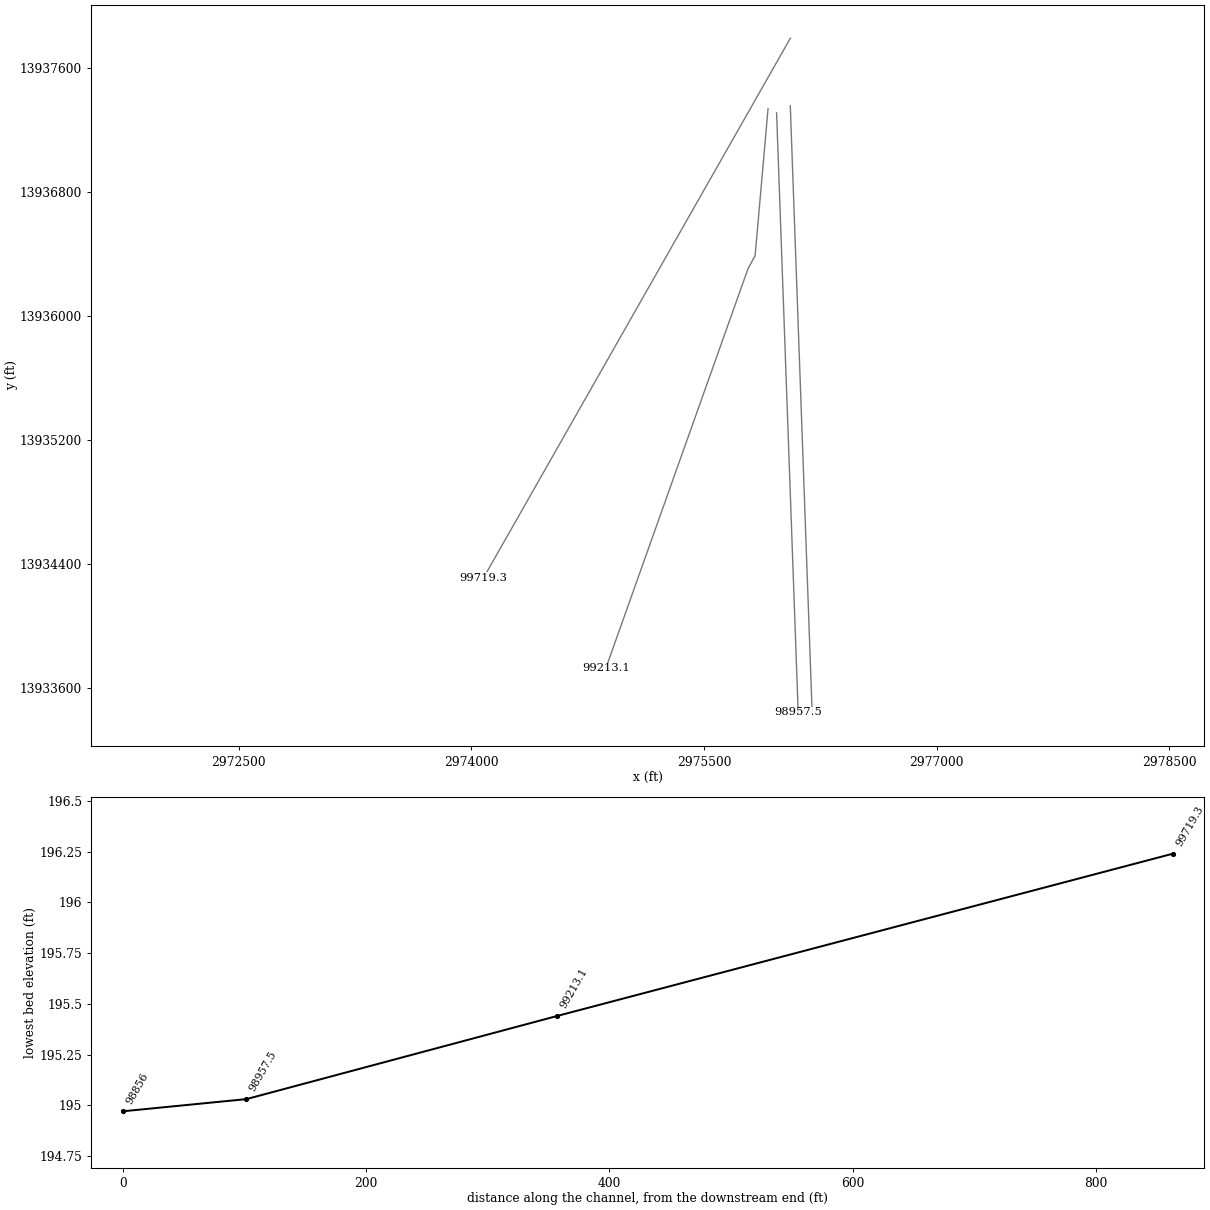
HEC-RAS study L100-00-00.prj: L100-00-00

--- L100-00-00.g01 (geometry) --- (continued)

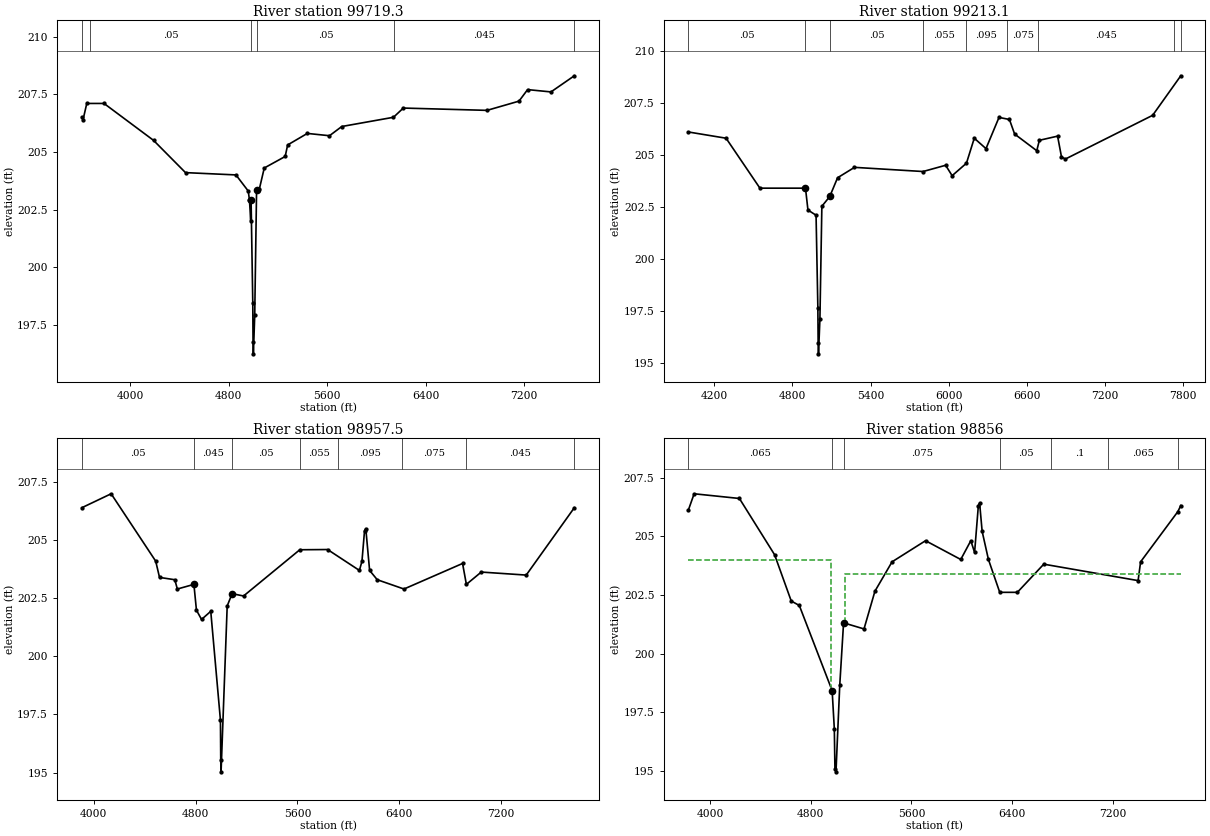
Type RM Length L Ch R = 1 ,99719.3 ,426,506.2,604
BEGIN DESCRIPTION:
Cross Section XS103
END DESCRIPTION:
XS GIS Cut Line= 3
     2976056.838    13937789.034     2975867.855   13937456.7119
    2974078.4925   13934310.1638
#Sta/Elev= 30
  3606.3   206.5  3616.3   206.4  3646.3   207.1  3786.3   207.1  4188.6   205.5
  4448.6   204.1  4858.6     204  4958.6   203.3  4968.6   202.9  4978.6     202
  4981.5   202.9  4995.3  198.46  4997.5  196.74  5000.2  196.24  5011.1  197.91
  5026.1  203.33  5048.3  203.38  5088.6   204.3  5258.6   204.8  5278.6   205.3
  5438.6   205.8  5618.6   205.7  5718.6   206.1  6138.6   206.5  6218.6   206.9
  6898.6   206.8  7158.6   207.2  7228.6   207.7  7418.6   207.6  7608.3   208.3
#Mann= 6 ,-1 , 0
  3606.3    .065       0  3674.4     .05       0  4981.5    .045       0
  5026.1     .05       0    6145    .045       0  7608.3      .2       0
Bank Sta=4981.5,5026.1
XS Rating Curve= 0 ,0
Exp/Cntr=0.3,0.1

Type RM Length L Ch R = 1 ,99213.1 ,192.4,255.6,492.6
BEGIN DESCRIPTION:
Cross Section XS102
END DESCRIPTION:
XS GIS Cut Line= 4
     2975913.347   13937335.3992    2975829.9445   13936387.6438
    2975784.4523   13936304.2413     2974867.025   13933726.3465
#Sta/Elev= 30
  4000.3   206.1  4290.3   205.8  4550.3   203.4  4900.3   203.4  4919.2  202.35
  4981.5   202.1  4995.3  197.66  4997.5  195.94  5000.2  195.44  5011.1  197.11
  5026.1  202.53  5086.7     203  5146.7   203.9  5276.7   204.4  5803.2   204.2
  5976.7   204.5  6026.7     204  6136.7   204.6  6196.7   205.8  6286.7   205.3
  6386.7   206.8  6466.7   206.7  6506.7     206  6676.7   205.2  6696.7   205.7
  6836.7   205.9  6866.7   204.9  6896.7   204.8  7566.7   206.9    7783   208.8
#Mann= 9 ,-1 , 0
  4000.3     .05       0  4900.3    .045       0  5086.7     .05       0
  5803.2    .055       0  6132.3    .095       0  6447.2    .075       0
  6688.4    .045       0  7729.7    .045       0    7783      .2       0
Bank Sta=4900.3,5086.7
XS Rating Curve= 0 ,0
Exp/Cntr=0.3,0.1

Type RM Length L Ch R = 1 ,98957.5 ,101.5,101.5,101.5
BEGIN DESCRIPTION:
Cross Section Roberts-US_Con
END DESCRIPTION:
XS GIS Cut Line= 2
     2975968.437   13937308.3784    2976107.6752   13933443.0496
#Sta/Elev= 30
  3906.8   206.4  4136.8     207  4486.8   204.1  4516.8   203.4  4636.8   203.3
  4656.8   202.9  4786.8   203.1  4806.8  201.99  4846.8  201.59  4919.2  201.94
  4995.3  197.25  4997.5  195.53  5000.2  195.03  5048.3  202.17  5086.8   202.7
  5176.8   202.6  5618.4  204.59  5836.8   204.6  6086.8   203.7  6106.8   204.1
  6126.8   205.4  6136.8   205.5  6166.8   203.7  6226.8   203.3  6436.8   202.9
  6896.8     204  6926.8   203.1  7043.8  203.63  7396.8   203.5  7774.6   206.4
#Mann= 8 ,-1 , 0
  3906.8     .05       0  4786.8    .045       0  5086.8     .05       0
  5618.4    .055       0  5919.9    .095       0  6423.1    .075       0
  6923.5    .045       0  7774.6      .2       0
Bank Sta=4786.8,5086.8
XS Rating Curve= 0 ,0
Exp/Cntr=0.5,0.3

Type RM Length L Ch R = 1 ,98856   ,63,63,63
BEGIN DESCRIPTION:
Upstream Section of Bridge/Culvert/Weir
END DESCRIPTION:
XS GIS Cut Line= 2
     2976056.853   13937353.9909    2976197.8149   13933440.7931
#Sta/Elev= 30
  3825.6  206.12  3871.8  206.82  4231.8  206.62  4511.8  204.22  4643.9  202.25
  4708.1  202.06  4969.2  198.43  4986.4  196.81  4991.4  195.09  4999.7  194.97
  5029.6  198.66    5060  201.32  5222.5  201.06  5309.5  202.67  5445.6  203.92
  5711.8  204.82  5991.8  204.02  6071.8  204.82  6101.8  204.32  6131.8  206.32
  6141.8  206.42  6161.8  205.22  6211.8  204.02  6301.8  202.62  6441.8  202.62
  6651.8  203.82  7401.8  203.12  7421.8  203.92  7717.9  206.06  7741.3  206.32
#Mann= 7 ,-1 , 0
  3825.6    .065       0  4969.9     .05       0    5060    .075       0
  6301.8     .05       0  6711.8      .1       0  7162.2    .065       0
  7717.9      .2       0
#XS Ineff= 2 , 0
       0    4960     204    5070       0   203.4
Permanent Ineff=
       F       F
Bank Sta=4969.2,5060
XS Rating Curve= 0 ,0
Exp/Cntr=0.5,0.3