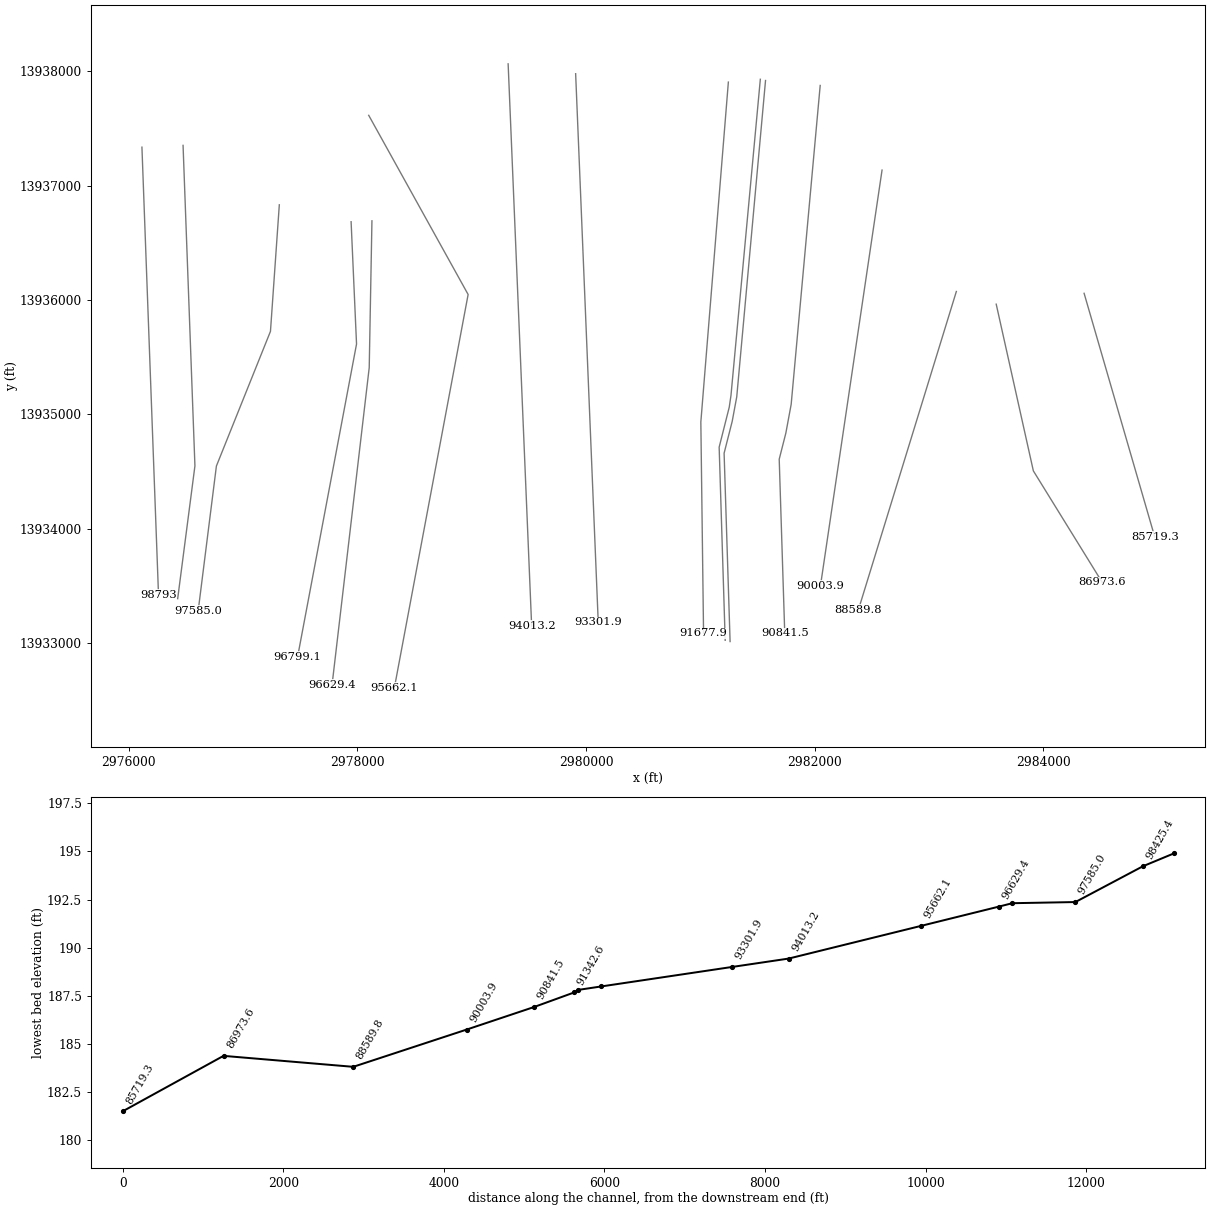
HEC-RAS study L100-00-00.prj: L100-00-00

--- L100-00-00.g01 (geometry) --- (continued)

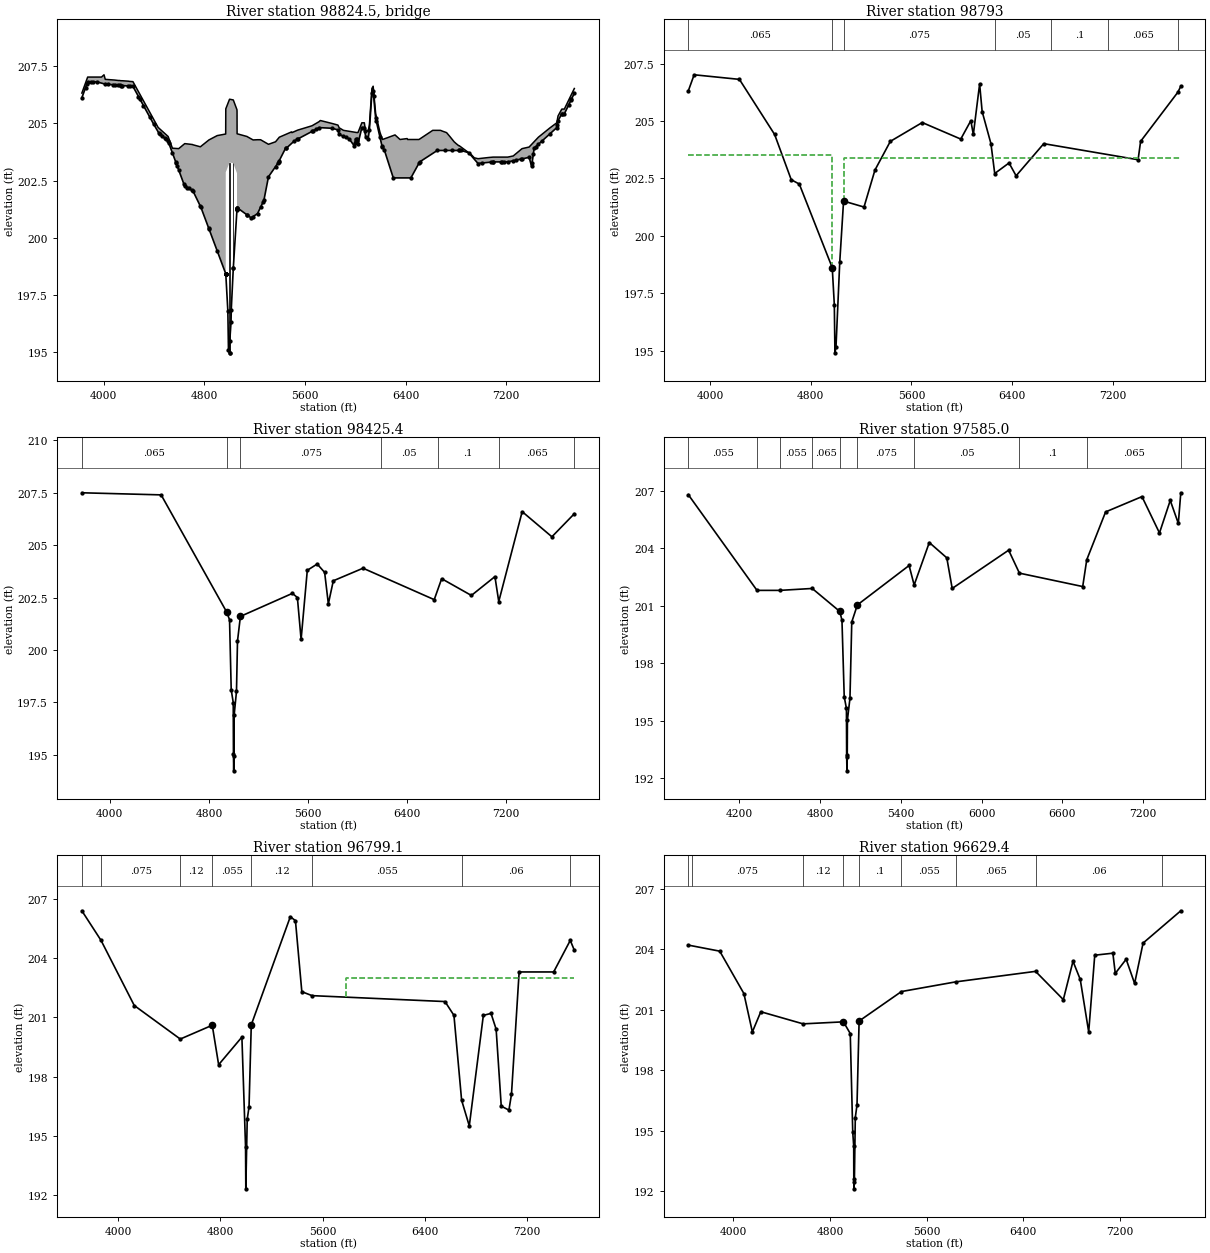
Type RM Length L Ch R = 3 ,98824.5 ,,,
BEGIN DESCRIPTION:
ROBERTS ROAD
Structure ID: L100-00-00S12
END DESCRIPTION:
Bridge Culvert--1,0,-1,-1, 0
Deck Dist Width WeirC Skew NumUp NumDn MinLoCord MaxHiCord MaxSubmerge Is_Ogee
10,42,2.6,0, 164, 164, , , 0.95, 0, 1,1,,
  3825.6  3855.6  3865.6  3871.8  3895.6  3915.6  3945.6  3981.8  3985.6  4001.8
  4011.8  4035.6  4075.6  4085.6  4115.6  4125.6  4135.6  4145.6  4195.6  4205.6
  4231.8  4275.6  4285.6  4315.6  4365.6  4395.6  4431.8  4435.6  4445.6  4465.6
  4485.6  4495.6  4511.8  4515.6  4545.6  4595.6  4643.9  4675.6  4704.9  4708.1
  4768.5  4772.4  4835.1  4835.8  4901.6  4969.2 4969.38  4969.7  4969.8  4969.9
    4970  4986.4  4991.4  4999.7  4999.8  5001.6  5011.7  5013.6  5029.6  5029.7
    5059  5059.1 5059.19  5059.5  5059.6 5059.71    5060  5139.5  5141.6    5172
  5187.4  5222.5  5246.4  5309.5  5365.6  5395.6  5491.8  5495.6  5511.8  5535.6
  5541.8  5655.6  5711.8  5721.8  5815.6  5861.8  5871.8  5905.6  6015.6  6021.8
  6051.8  6071.8  6075.6  6081.8  6091.8  6101.8  6111.8  6131.8  6141.8  6145.6
  6161.8  6165.6  6195.6  6211.8  6215.6  6231.8  6261.8  6265.9  6301.8  6315.6
  6321.8  6351.8  6355.6  6411.8  6415.6  6421.8  6431.8  6441.8  6505.6  6511.8
  6551.8  6571.8  6601.8  6615.6  6675.6  6681.8  6690.2  6711.8  6725.6  6751.8
  6771.8  6785.6  6801.8  6821.8  6825.6  6921.8  6931.8  6945.6  6975.6  7005.6
  7055.6  7075.6  7091.8  7095.6  7162.2  7165.6  7185.6  7211.8  7255.6  7325.6
  7381.8  7421.8  7455.6  7545.6  7601.8  7605.6  7611.8  7641.8  7645.6  7661.8
  7695.6  7715.6  7717.9  7741.3
  206.33  206.78  206.94  207.03  207.03  207.03  207.03  207.03  207.05  207.13
  206.93  206.92   206.9   206.9  206.88  206.88  206.87  206.87  206.85  206.84
  206.83  206.39  206.29  205.99  205.49  205.19  204.83  204.81  204.76  204.66
  204.56  204.51  204.43  204.37  203.92   203.9  204.12   204.1  204.08  204.07
  203.98     204  204.28  204.28  204.47  204.54  205.64  205.64  205.64  205.64
  205.64  205.87  205.94  206.06  206.06  206.06  206.05  206.05  206.03  206.03
   205.6  205.56  205.52  205.52  204.55  204.55  204.55  204.43  204.42  204.33
  204.28  204.29  204.29  204.09   204.2   204.4  204.63   204.6  204.64   204.7
  204.71   204.9  205.08  205.13     205  204.93  204.81   204.7   204.6  204.61
  205.03  205.03  204.88  204.69  204.68  204.66  204.93  206.53  206.63   206.4
  205.43  205.34  204.62  204.36   204.3  204.33  204.39   204.4  204.47   204.5
  204.47  204.32   204.3  204.34   204.3   204.3   204.3   204.3   204.3  204.32
  204.47  204.54  204.65   204.7   204.7  204.69  204.67  204.63   204.6  204.43
  204.29   204.2  204.12  204.03  204.03  203.64  203.58   203.5  203.46  203.48
  203.51  203.52  203.53  203.53  203.53  203.53  203.53  203.53  203.58   203.9
  203.97   204.2   204.4   204.8  205.03  205.14  205.33  205.63  205.63  205.63
  206.01  206.24  206.27  206.53
                                                                                
                                                                                
                                                                                
                                                                                
                                                                  202.87  202.87
  202.87   203.1  203.17  203.29  203.29  203.29  203.28  203.28  203.26  203.26
  202.83  202.79  202.79
                                                                                
                                                                                
                                                                                
                                                                                
                                                                                
                                                                                
                                                                                
                                                                                
                                                                                
                                
  3825.6  3855.6  3865.6  3871.8  3895.6  3915.6  3945.6  3981.8  3985.6  4001.8
  4011.8  4035.6  4075.6  4085.6  4115.6  4125.6  4135.6  4145.6  4195.6  4205.6
  4231.8  4275.6  4285.6  4315.6  4365.6  4395.6  4431.8  4435.6  4445.6  4465.6
  4485.6  4495.6  4511.8  4515.6  4545.6  4595.6  4643.9  4675.6  4704.9  4708.1
  4768.5  4772.4  4835.1  4835.8  4901.6  4969.2 4969.38  4969.7  4969.8  4969.9
    4970  4986.4  4991.4  4999.7  4999.8  5001.6  5011.7  5013.6  5029.6  5029.7
    5059  5059.1 5059.19  5059.5  5059.6 5059.71    5060  5139.5  5141.6    5172
  5187.4  5222.5  5246.4  5309.5  5365.6  5395.6  5491.8  5495.6  5511.8  5535.6
  5541.8  5655.6  5711.8  5721.8  5815.6  5861.8  5871.8  5905.6  6015.6  6021.8
  6051.8  6071.8  6075.6  6081.8  6091.8  6101.8  6111.8  6131.8  6141.8  6145.6
  6161.8  6165.6  6195.6  6211.8  6215.6  6231.8  6261.8  6265.9  6301.8  6315.6
  6321.8  6351.8  6355.6  6411.8  6415.6  6421.8  6431.8  6441.8  6505.6  6511.8
  6551.8  6571.8  6601.8  6615.6  6675.6  6681.8  6690.2  6711.8  6725.6  6751.8
  6771.8  6785.6  6801.8  6821.8  6825.6  6921.8  6931.8  6945.6  6975.6  7005.6
  7055.6  7075.6  7091.8  7095.6  7162.2  7165.6  7185.6  7211.8  7255.6  7325.6
  7381.8  7421.8  7455.6  7545.6  7601.8  7605.6  7611.8  7641.8  7645.6  7661.8
  7695.6  7715.6  7717.9  7741.3
   206.1  206.56  206.72  206.81  206.81  206.81  206.81  206.81  206.83  206.91
  206.71   206.7  206.68  206.68  206.66  206.66  206.65  206.65  206.63  206.62
  206.61  206.17  206.07  205.77  205.27  204.97  204.63   204.6  204.54  204.44
  204.34  204.29  204.21  204.15   203.7   203.9  204.12   204.1  204.08  204.07
  203.98     204  204.28  204.28  204.47  204.54  205.64  205.64  205.64  205.64
  205.64  205.87  205.94  206.06  206.06  206.06  206.05  206.05  206.03  206.03
   205.6  205.56  205.52  205.52  204.55  204.55  204.55  204.43  204.42  204.33
  204.28  204.29  204.29  204.09   204.2   204.4  204.61   204.6  204.64   204.7
  204.71   204.9  205.08  205.07     205  204.85  204.81   204.7   204.6  204.61
  204.81  204.81   204.7  204.69  204.68  204.66  204.71  206.31  206.41  206.18
  205.21  205.12   204.6  204.36   204.3  204.33  204.39   204.4  204.47   204.5
  204.47  204.32   204.3  204.34   204.3   204.3   204.3   204.3   204.3  204.32
  204.47  204.54  204.65   204.7   204.7  204.69  204.67  204.63   204.6  204.43
  204.29   204.2  204.12  204.02     204  203.64  203.58   203.5  203.24  203.26
  203.29   203.3  203.31  203.31  203.31  203.31  203.31  203.31   203.5   203.9
  203.97   204.2   204.4   204.8  204.81  204.92  205.11  205.41  205.41  205.41
  205.79  206.02  206.05   206.3
                                                                                
                                                                                
                                                                                
                                                                                
                                                                  202.64  202.64
  202.64  202.87  202.94  203.06  203.06  203.06  203.05  203.05  203.03  203.03
   202.6  202.56  202.56
                                                                                
                                                                                
                                                                                
                                                                                
                                                                                
                                                                                
                                                                                
                                                                                
                                                                                
                                
Pier Skew, UpSta & Num, DnSta & Num=  ,4999.8, 2 ,4999.8, 2 , 0 , 0 , 0 ,,
     1.5     1.5
  193.94  204.06
     1.5     1.5
  194.17  204.29
Pier Skew, UpSta & Num, DnSta & Num=  ,5029.7, 2 ,5029.7, 2 , 0 , 0 , 0 ,,
     1.5     1.5
  197.57  204.03
     1.5     1.5
   197.8  204.26
BR Coef= 1 , 1 , 1 ,1.25, 0 ,,,0.8,0,2,0,
WSPro=,,,, 1 ,,,, 0 ,,,, 0 ,,,,-1 ,-1 ,-1 , 0 , 0 , 0 , 0 , 0
BR U #Sta/Elev= 164
  3825.6  206.12  3855.6  206.57  3865.6  206.73  3871.8  206.82  3895.6  206.82
  3915.6  206.82  3945.6  206.82  4011.8  206.72  4035.6  206.71  4075.6  206.69
  4085.6  206.69  4115.6  206.67  4125.6  206.67  4135.6  206.66  4145.6  206.66
  4195.6  206.64  4205.6  206.63  4231.8  206.62  4275.6  206.18  4285.6  206.08
  4315.6  205.78  4365.6  205.28  4395.6  204.98  4435.6   204.6  4445.6  204.55
  4465.6  204.45  4485.6  204.35  4495.6   204.3  4511.8  204.22  4515.6  204.16
  4545.6  203.71  4571.8  203.32  4575.6  203.26  4585.6  203.12  4595.6  202.97
  4635.6  202.37  4643.9  202.25  4665.6  202.19  4675.6  202.16  4704.9  202.07
  4708.1  202.06  4768.5  201.37  4772.4  201.33  4835.1  200.41  4835.8   200.4
  4901.6  199.43  4969.2  198.43 4969.27  198.43 4969.38  198.43 4969.49  198.43
 4969.61  198.43  4969.7  198.42  4969.8  198.42  4969.9  198.42    4970  198.42
  4986.4  196.81  4991.4  195.09  4999.7  194.97  4999.8  194.97  5001.6  195.49
  5011.7   196.3  5013.6  196.86  5029.6  198.66  5029.7  198.67    5059  201.23
  5059.1  201.24  5059.3  201.26 5059.39  201.27  5059.5  201.28  5059.6  201.29
 5059.71  201.29    5060  201.32  5139.5     201  5141.6  200.99    5172  200.87
  5187.4  200.93  5222.5  201.06  5246.4  201.33  5265.6  201.55  5273.1  201.64
  5309.5  202.67  5365.6  203.11  5385.6  203.27  5391.8  203.32  5395.6  203.38
  5445.6  203.92  5451.8  203.92  5511.8  204.22  5535.6   204.3  5541.8  204.32
  5655.6  204.65  5665.6  204.68  5685.6  204.74  5711.8  204.82  5815.6  204.79
  5861.8  204.72  5871.8  204.52  5905.6  204.44  5925.6  204.39  5951.8  204.32
  5991.8  204.02  5995.6  204.13  6001.8  204.32  6011.8  204.32  6015.6  204.24
  6021.8  204.12  6051.8  204.82  6071.8  204.82  6075.6  204.67  6081.8  204.42
  6101.8  204.32  6111.8  204.72  6131.8  206.32  6141.8  206.42  6145.6  206.19
  6161.8  205.22  6165.6  205.13  6195.6  204.41  6211.8  204.02  6215.6  203.98
  6231.8  203.82  6301.8  202.62  6441.8  202.62  6505.6  203.26  6511.8  203.32
  6651.8  203.82  6711.8  203.82  6771.8  203.82  6821.8  203.82  6825.6  203.82
  6841.8  203.82  6901.8  203.72  6975.6  203.25  7005.6  203.27  7075.6  203.31
  7091.8  203.32  7095.6  203.32  7162.2  203.32  7165.6  203.32  7185.6  203.32
  7211.8  203.32  7255.6  203.37  7275.6   203.4  7315.6  203.44  7325.6  203.45
  7381.8  203.52  7401.8  203.12  7405.6  203.27  7415.6  203.67  7421.8  203.92
  7435.6  203.99  7455.6  204.09  7485.6  204.24  7545.6  204.54  7601.8  204.82
  7605.6  204.93  7611.8  205.12  7641.8  205.42  7645.6  205.42  7661.8  205.42
  7695.6   205.8  7715.6  206.03  7717.9  206.06  7741.3  206.32
BR U #Mann= 7
  3825.6    .065  4969.9    .045    5060    .075  6301.8     .05  6711.8      .1
  7162.2    .065  7717.9      .2
BR D #Sta/Elev= 173
  3825.6  206.31  3855.6  206.76  3865.6  206.92  3871.8  207.01  3895.6  207.01
  3915.6  207.01  3945.6  207.01  3981.8  207.01  3985.6  207.03  4011.8  206.91
  4035.6   206.9  4075.6  206.88  4085.6  206.88  4115.6  206.86  4125.6  206.86
  4135.6  206.85  4145.6  206.85  4195.6  206.83  4205.6  206.82  4231.8  206.81
  4275.6  206.37  4285.6  206.27  4315.6  205.97  4365.6  205.47  4395.6  205.17
  4431.8  204.81  4435.6  204.79  4445.6  204.74  4465.6  204.64  4485.6  204.54
  4495.6  204.49  4511.8  204.41  4515.6  204.35  4545.6   203.9  4571.8  203.51
  4575.6  203.45  4585.6  203.31  4595.6  203.16  4635.6  202.56  4643.9  202.44
  4665.6  202.38  4675.6  202.35  4704.9  202.26  4708.1  202.25  4768.5  201.56
  4772.4  201.52  4835.1   200.6  4835.8  200.59  4901.6  199.62  4969.2  198.62
 4969.27  198.62 4969.38  198.62 4969.49  198.62 4969.61  198.62  4969.7  198.61
  4969.8  198.61  4969.9  198.61    4970  198.61  4986.4     197  4991.4   194.9
  4999.7  195.16  4999.8  195.16  5001.6  195.68  5011.7  196.49  5013.6  197.05
  5029.6  198.85  5029.7  198.86    5059  201.42  5059.1  201.43  5059.3  201.45
 5059.39  201.46  5059.5  201.47  5059.6  201.48 5059.71  201.48    5060  201.51
  5139.5  201.19  5141.6  201.18    5172  201.06  5187.4  201.12  5222.5  201.25
  5246.4  201.52  5265.6  201.74  5273.1  201.83  5309.5  202.86  5365.6   203.3
  5385.6  203.46  5391.8  203.51  5395.6  203.57  5431.8  204.11  5445.6  204.11
  5451.8  204.11  5511.8  204.41  5535.6  204.49  5541.8  204.51  5655.6  204.84
  5665.6  204.87  5685.6  204.93  5815.6  204.98  5861.8  204.91  5871.8  204.71
  5905.6  204.63  5925.6  204.58  5951.8  204.51  5991.8  204.21  6021.8  204.31
  6051.8  205.01  6071.8  205.01  6075.6  204.86  6081.8  204.61  6091.8  204.41
  6101.8  204.51  6111.8  204.91  6131.8  206.51  6141.8  206.61  6145.6  206.38
  6161.8  205.41  6165.6  205.32  6195.6   204.6  6211.8  204.21  6215.6  204.17
  6231.8  204.01  6261.8  202.71  6265.9  202.72  6301.8  202.81  6321.8  203.11
  6355.6  203.13  6375.6  203.17  6421.8  202.71  6431.8  202.61  6441.8  202.81
  6505.6  203.45  6511.8  203.51  6571.8  203.61  6625.6   203.7  6651.8  204.01
  6711.8  204.01  6771.8  204.01  6821.8  204.01  6825.6  204.01  6901.8  203.91
  6945.6  203.42  6975.6  203.44  7005.6  203.46  7055.6  203.49  7075.6   203.5
  7091.8  203.51  7095.6  203.51  7162.2  203.51  7165.6  203.51  7185.6  203.51
  7211.8  203.51  7255.6  203.56  7275.6  203.59  7315.6  203.63  7325.6  203.64
  7381.8  203.71  7401.8  203.31  7405.6  203.46  7415.6  203.86  7421.8  204.11
  7435.6  204.18  7455.6  204.28  7485.6  204.43  7545.6  204.73  7605.6  205.12
  7611.8  205.31  7641.8  205.61  7645.6  205.61  7661.8  205.61  7695.6  205.99
  7715.6  206.22  7717.9  206.25  7741.3  206.51
BR D #Mann= 7
  3825.6    .065  4969.9    .045    5060    .075  6265.9     .05  6711.8      .1
  7162.2    .065  7717.9      .2
BC Design=,, 0 ,, 0 ,,,,,,
BC HTab HWMax=206.82
BC Use User HTab Curves=0
BC User HTab FreeFlow(D)= 0

Type RM Length L Ch R = 1 ,98793   ,382.2,386.6,428.7
BEGIN DESCRIPTION:
Downstream Section of Bridge/Culvert/Weir
END DESCRIPTION:
XS GIS Cut Line= 2
     2976116.989   13937336.3591    2976261.9143   13933423.3867
#Sta/Elev= 30
  3825.6  206.31  3871.8  207.01  4231.8  206.81  4511.8  204.41  4643.9  202.44
  4708.1  202.25    4970  198.61  4986.4     197  4991.4   194.9  4999.8  195.16
  5029.6  198.85    5060  201.51  5222.5  201.25  5309.5  202.86  5431.8  204.11
  5685.6  204.93  5991.8  204.21  6071.8  205.01  6091.8  204.41  6141.8  206.61
  6161.8  205.41  6231.8  204.01  6261.8  202.71  6375.6  203.17  6431.8  202.61
  6651.8  204.01  7401.8  203.31  7421.8  204.11  7717.9  206.25  7741.3  206.51
#Mann= 7 ,-1 , 0
  3825.6    .065       0    4970    .035       0    5060    .075       0
  6265.9     .05       0  6711.8      .1       0  7162.2    .065       0
  7717.9      .2       0
#XS Ineff= 2 , 0
       0    4968   203.5    5062       0   203.4
Permanent Ineff=
       F       F
Bank Sta=4970,5060
XS Rating Curve= 0 ,0
Exp/Cntr=0.5,0.3

Type RM Length L Ch R = 1 ,98425.4 ,828.4,840.4,476.4
BEGIN DESCRIPTION:
Cross Section Roberts-DS_Exp
END DESCRIPTION:
XS GIS Cut Line= 3
     2976476.658   13937351.9817    2976580.4694    13934549.063
    2976429.6116   13933387.8761
#Sta/Elev= 30
    3774   207.5    4414   207.4    4944   201.8  4966.3  201.44  4979.8   198.1
  4996.2  197.49  4997.8  195.05    5000  194.23  5002.2  194.93  5003.5  196.89
  5022.4  198.02  5030.5  200.42    5054   201.6    5474   202.7    5514   202.5
    5544   200.5    5594   203.8    5674   204.1    5734   203.7    5764   202.2
    5804   203.3    6044   203.9  6618.8   202.4  6678.8   203.4  6918.8   202.6
  7108.8   203.5  7139.7  202.31  7328.8   206.6  7568.8   205.4  7749.8   206.5
#Mann= 7 ,-1 , 0
    3774    .065       0    4944    .035       0    5054    .075       0
  6187.3     .05       0  6645.4      .1       0  7139.7    .065       0
  7749.8      .2       0
Bank Sta=4944,5054
XS Rating Curve= 0 ,0
Exp/Cntr=0.3,0.1

Type RM Length L Ch R = 1 ,97585.0 ,764.5,785.9,927.6
BEGIN DESCRIPTION:
Cross Section XS100
END DESCRIPTION:
XS GIS Cut Line= 4
     2977318.442   13936832.2222    2977241.0211   13935725.5318
    2976768.2477   13934547.7453     2976608.643   13933279.4335
#Sta/Elev= 30
  3822.1   206.8  4332.1   201.8  4502.1   201.8  4742.1   201.9  4946.7   200.7
    4963  200.24  4979.8  196.24  4996.2  195.63  4997.8  193.19    5000  192.37
  5002.2  193.07  5003.5  195.03  5022.4  196.16  5035.8  200.15  5077.5  201.04
  5461.5   203.1    5499  202.08  5611.5   204.3  5741.5   203.5  5781.5   201.9
  6200.7   203.9  6280.7   202.7  6750.7     202  6780.7   203.4  6920.7   205.9
  7190.7   206.7  7320.7   204.8  7400.7   206.5  7460.7   205.3    7479   206.9
#Mann= 10 ,-1 , 0
  3822.1    .055       0  4332.1    .075       0  4502.1    .055       0
  4742.1    .065       0  4946.7    .035       0  5077.5    .075       0
    5499     .05       0  6280.7      .1       0  6780.7    .065       0
    7479      .2       0
Bank Sta=4946.7,5077.5
XS Rating Curve= 0 ,0
Exp/Cntr=0.3,0.1

Type RM Length L Ch R = 1 ,96799.1 ,122.8,169.7,203.1
BEGIN DESCRIPTION:
Cross Section XS99
END DESCRIPTION:
XS GIS Cut Line= 3
     2977946.232   13936684.3018    2977993.7744   13935614.5997
    2977478.7327   13932880.9166
#Sta/Elev= 30
  3715.7   206.4  3865.7   204.9  4125.7   201.6  4485.7   199.9  4735.7   200.6
  4785.7   198.6  4967.7     200  4996.3  194.43  4998.3  192.31  5009.4  195.84
  5023.5  196.46    5041  200.62  5346.5   206.1  5386.5   205.9  5436.5   202.3
  5516.5   202.1  6556.5   201.8  6626.5   201.1  6686.5   196.8  6746.5   195.5
  6856.5   201.1  6916.5   201.2  6956.5   200.4  6996.5   196.5  7056.5   196.3
  7076.5   197.1  7136.5   203.3  7406.5   203.3  7536.5   204.9  7568.2   204.4
#Mann= 8 ,-1 , 0
  3715.7    .055       0  3865.7    .075       0  4485.7     .12       0
  4735.7    .055       0    5041     .12       0  5516.5    .055       0
  6686.5     .06       0  7536.5      .2       0
#XS Ineff= 2 , 0
       0                    5783       0     203
Permanent Ineff=
       F       F
Bank Sta=4735.7,5041
XS Rating Curve= 0 ,0
Exp/Cntr=0.3,0.1

Type RM Length L Ch R = 1 ,96629.4 ,836.5,967.3,695.3
BEGIN DESCRIPTION:
Cross Section XS98
END DESCRIPTION:
XS GIS Cut Line= 3
     2978128.478   13936692.2255    2978104.7065    13935408.583
     2977779.834   13932635.2813
#Sta/Elev= 30
  3627.4   204.2  3887.4   203.9  4087.4   201.8  4157.4   199.9  4227.4   200.9
  4577.4   200.3  4911.3   200.4  4967.7  199.82  4988.3  194.93  4996.3  194.25
  4997.1  192.64  4998.3  192.13  5001.8  192.46  5009.4  195.66  5023.5  196.28
    5041  200.44  5391.3   201.9  5841.1  202.38  6501.3   202.9  6731.3   201.5
  6811.3   203.4  6871.3   202.5  6941.3   199.9  6991.3   203.7  7141.3   203.8
  7161.3   202.8  7251.3   203.5  7321.3   202.3  7391.3   204.3  7703.5   205.9
#Mann= 9 ,-1 , 0
  3627.4     .06       0  3657.1    .075       0  4577.4     .12       0
  4911.3    .065       0    5041      .1       0  5391.3    .055       0
  5841.1    .065       0  6501.3     .06       0  7546.5      .2       0
Bank Sta=4911.3,5041
XS Rating Curve= 0 ,0
Exp/Cntr=0.3,0.1

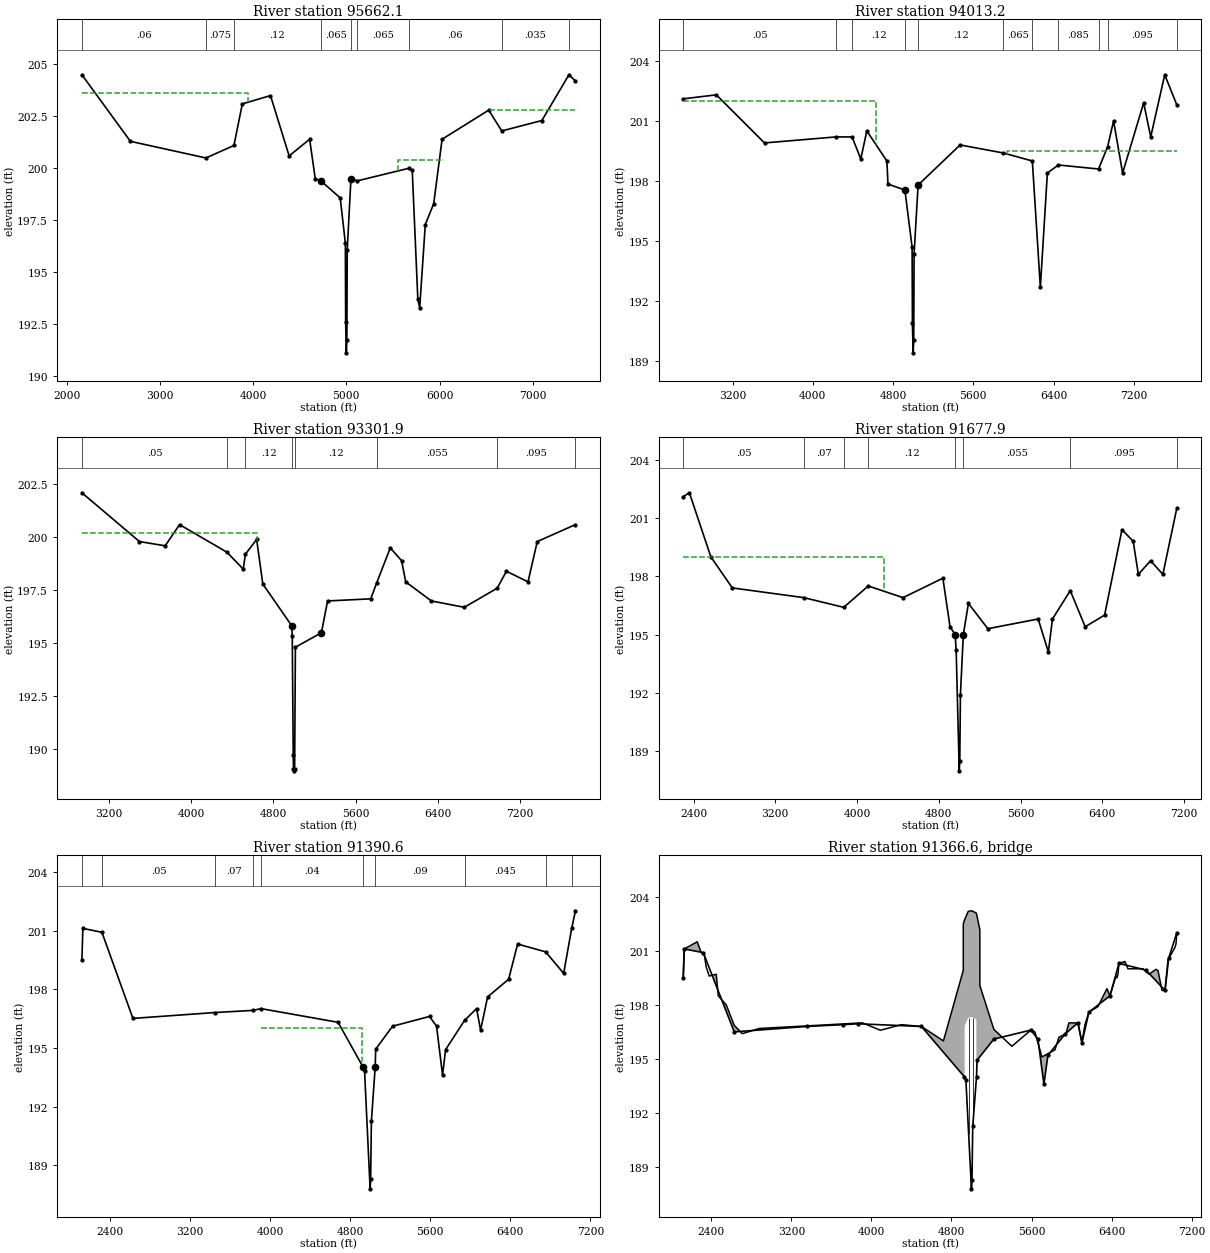
Type RM Length L Ch R = 1 ,95662.1 ,522.5,1648.9,849.6
BEGIN DESCRIPTION:
Cross Section XS97.5
END DESCRIPTION:
XS GIS Cut Line= 3
     2978100.303   13937614.7463    2978969.6485   13936047.9025
    2978324.5201   13932607.8496
#Sta/Elev= 30
  2164.8   204.5  2684.8   201.3  3494.8   200.5  3794.8   201.1  3884.8   203.1
  4186.7   203.5  4386.7   200.6  4606.7   201.4  4666.7   199.5  4726.7   199.4
 4934.48  198.58  4989.6   196.4  4992.7   192.6  4999.9  191.13  5005.7  191.75
  5009.5  196.07  5049.5   199.5  5118.1   199.4    5667     200  5706.7   199.9
  5766.7   193.7  5786.7   193.3  5846.7   197.3  5936.7   198.3  6026.7   201.4
  6526.7   202.8  6666.7   201.8  7096.7   202.3  7386.7   204.5  7456.7   204.2
#Mann= 9 ,-1 , 0
  2164.8     .06       0  3494.8    .075       0  3794.8     .12       0
  4726.7    .065       0  5049.5     .12       0  5118.1    .065       0
    5667     .06       0  6666.7    .035       0  7386.7      .2       0
#XS Ineff= 4 ,-1
    2150    3950   203.6    3950  4606.7     201    5550    6050   200.4
    6529    7500   202.8
Permanent Ineff=
       F       F       F       F
Bank Sta=4726.7,5049.5
XS Rating Curve= 0 ,0
Exp/Cntr=0.3,0.1

Type RM Length L Ch R = 1 ,94013.2 ,596.3,711.3,594.3
BEGIN DESCRIPTION:
Cross Section XS97
END DESCRIPTION:
XS GIS Cut Line= 2
     2979319.554   13938064.9276    2979525.2146   13933149.0627
#Sta/Elev= 30
  2708.1   202.1  3038.1   202.3  3518.1   199.9  4228.1   200.2  4391.3   200.2
  4478.1   199.1  4538.1   200.5  4738.1     199  4748.9  197.85  4917.7  197.55
  4989.6   194.7  4992.7   190.9  4999.9  189.43  5005.7  190.05  5009.5  194.37
  5049.5   197.8  5468.1   199.8  5898.1   199.4  6188.1     199  6268.1   192.7
  6338.1   198.4  6448.1   198.8  6848.1   198.6  6938.1   199.7  6998.1     201
  7088.1   198.4  7298.1   201.9  7368.1   200.2  7508.1   203.3  7628.3   201.8
#Mann= 11 ,-1 , 0
  2708.1     .05       0  4228.1    .075       0  4391.3     .12       0
  4917.7    .065       0  5049.5     .12       0  5898.1    .065       0
  6188.1    .055       0  6448.1    .085       0  6848.1    .055       0
  6938.1    .095       0  7628.3      .2       0
#XS Ineff= 2 , 0
       0    4630     202    5940       0   199.5
Permanent Ineff=
       F       F
Bank Sta=4917.7,5049.5
XS Rating Curve= 0 ,0
Exp/Cntr=0.3,0.1

Type RM Length L Ch R = 1 ,93301.9 ,1251.9,1624,1055.1
BEGIN DESCRIPTION:
Cross Section XS96
END DESCRIPTION:
XS GIS Cut Line= 2
     2979909.874    13937978.678    2980107.5465   13933181.1177
#Sta/Elev= 30
  2937.4   202.1  3497.4   199.8  3747.4   199.6  3887.4   200.6  4347.8   199.3
  4507.4   198.5  4527.4   199.2  4637.4   199.9  4697.4   197.8  4978.8  195.83
  4983.9  195.34  4993.2  189.76  4995.7  189.07  5005.1  188.99  5006.9  189.08
  5014.4  194.82  5267.4   195.5  5327.4     197  5747.4   197.1    5805  197.85
  5937.4   199.5  6047.4   198.9  6087.4   197.9  6337.4     197  6657.4   196.7
  6977.4   197.6  7067.4   198.4  7277.4   197.9  7367.4   199.8    7739   200.6
#Mann= 8 ,-1 , 0
  2937.4     .05       0  4347.8    .075       0  4527.4     .12       0
  4978.8    .065       0  5014.4     .12       0    5805    .055       0
  6977.4    .095       0    7739      .2       0
#XS Ineff= 2 , 0
       0    4640   200.2               0
Permanent Ineff=
       F       F
Bank Sta=4978.8,5267.4
XS Rating Curve= 0 ,0
Exp/Cntr=0.3,0.1

Type RM Length L Ch R = 1 ,91677.9 ,356.1,287.3,158.6
BEGIN DESCRIPTION:
Cross Section XS95
END DESCRIPTION:
XS GIS Cut Line= 3
     2981245.511    13937905.526    2981004.7877   13934933.1599
    2981028.5589   13933086.9333
#Sta/Elev= 30
  2299.4   202.1  2359.4   202.3  2569.4     199  2779.4   197.4  3479.4   196.9
  3869.4   196.4  4109.4   197.5  4449.4   196.9  4839.4   197.9  4909.4   195.4
  4959.4     195  4969.4   194.2  4999.5  187.98  5004.8  188.47  5011.1  191.91
  5039.4     195  5089.4   196.6  5279.4   195.3  5771.5   195.8  5871.5   194.1
  5911.5   195.8  6085.6  197.26  6231.5   195.4  6421.5     196  6591.5   200.4
  6701.5   199.8  6751.5   198.1  6871.5   198.8  6991.5   198.1  7127.9   201.5
#Mann= 8 ,-1 , 0
  2299.4     .05       0  3479.4     .07       0  3869.4    .075       0
  4109.4     .12       0  4959.4    .065       0  5039.4    .055       0
  6085.6    .095       0  7127.9      .2       0
#XS Ineff= 2 , 0
       0    4259     199               0
Permanent Ineff=
       F       F
Bank Sta=4959.4,5039.4
XS Rating Curve= 0 ,0
Exp/Cntr=0.5,0.3

Type RM Length L Ch R = 1 ,91390.6 ,48,48,48
BEGIN DESCRIPTION:
Upstream Section of Bridge/Culvert/Weir
END DESCRIPTION:
XS GIS Cut Line= 5
     2981525.051   13937930.2224    2981268.3646   13935165.5561
    2981253.2614   13935062.5466    2981164.9989   13934712.8305
    2981217.7838   13933023.7166
#Sta/Elev= 30
  2119.9  199.51  2129.5  201.11  2319.8  200.91  2629.5  196.51  3449.5  196.81
  3829.9  196.92  3909.5  197.01  4679.5  196.31    4930  194.01  4944.1  193.82
  4999.5   187.8  5004.8  188.29  5012.3  191.26    5050  194.01  5055.6  194.94
  5223.4  196.11  5593.4  196.61  5663.4  196.11  5723.4  193.61  5753.4  194.91
  5943.4  196.41  6063.4  197.01  6103.4  195.91  6173.4  197.61  6383.4  198.51
  6473.4  200.31  6753.4  199.91  6933.4  198.81  7013.4  201.11  7051.2  202.01
#Mann= 10 ,-1 , 0
  2119.9     .05       0  2319.8     .05       0  3449.5     .07       0
  3829.9    .075       0  3909.5     .04       0    4930     .06       0
    5050     .09       0  5943.4    .045       0  6753.4     .04       0
  7013.4      .2       0
#XS Ineff= 3 ,-1
    2500    3909     197    3909    4914     196    5068    6250     195
Permanent Ineff=
       F       F       F
Bank Sta=4930,5050
XS Rating Curve= 0 ,0
Exp/Cntr=0.5,0.3

Type RM Length L Ch R = 3 ,91366.6 ,,,
BEGIN DESCRIPTION:
BECKER ROAD
Structure ID: L100-00-00-S11
END DESCRIPTION:
Bridge Culvert--1,0,-1,-1, 0
Deck Dist Width WeirC Skew NumUp NumDn MinLoCord MaxHiCord MaxSubmerge Is_Ogee
10,28,2.6,0, 60, 60, , , 0.95, 0, 1,1,,
  2119.9  2129.5  2259.5  2299.5  2329.5  2349.9  2379.5  2449.5  2469.5  2549.5
  2629.5  2709.9  2879.9  3909.9  4089.5  4299.5  4499.5  4719.5 4917.69  4917.8
 4931.51  4931.6  4967.7  5003.1 5048.59  5048.7  5083.4 5083.51  5223.4  5403.4
  5593.4  5633.4  5703.4  5833.4  5873.4  5943.4  5973.4  6063.4  6103.4  6133.4
  6173.4  6263.4  6353.3  6383.4  6443.4  6453.4  6463.4  6473.4  6533.4  6563.4
  6713.4  6773.3  6843.4  6863.4  6903.3  6933.4  6963.4  7033.4  7043.4  7051.2
   199.5  201.11  201.51  200.91  200.81   200.1  199.61  199.71  198.51  198.01
  196.87  196.41   196.7  197.01   196.6  196.91  196.81  196.01  199.92   202.5
  202.74  202.74   203.2  203.23   203.1   203.1  202.18  199.08  196.65  195.71
  196.61  196.51  195.12  195.51  196.21  196.41  197.01  197.01  195.91  196.91
  197.61  197.91  198.91  198.51  199.61  199.51  199.71  200.31  200.41  200.01
  200.01  199.71  199.98  199.91  198.81  198.81  200.51   201.2   201.4     202
                                                                                
                                                                                
          196.84   197.3  197.33   197.2
                                                                                
                                                                                
                                                                                
  2119.9  2129.5  2259.5  2299.5  2329.5  2349.9  2379.5  2449.5  2469.5  2549.5
  2629.5  2709.9  2879.9  3909.9  4089.5  4299.5  4499.5  4719.5 4917.69  4917.8
 4931.51  4931.6  4967.7  5003.1 5048.59  5048.7  5083.4 5083.51  5223.4  5403.4
  5593.4  5633.4  5703.4  5833.4  5873.4  5943.4  5973.4  6063.4  6103.4  6133.4
  6173.4  6263.4  6353.3  6383.4  6443.4  6453.4  6463.4  6473.4  6533.4  6563.4
  6713.4  6773.3  6843.4  6863.4  6903.3  6933.4  6963.4  7033.4  7043.4  7051.2
   199.5  201.11  201.51  200.91  200.81   200.1  199.61  199.71  198.51  198.01
  196.87  196.41   196.7  197.01   196.6  196.91  196.81  196.01  199.92   202.5
  202.74  202.74   203.2  203.23   203.1   203.1  202.18  199.08  196.65  195.71
  196.61  196.51  195.12  195.51  196.21  196.41  197.01  197.01  195.91  196.91
  197.61  197.91  198.91  198.51  199.61  199.51  199.71  200.31  200.41  200.01
  200.01  199.71  199.98  199.91  198.81  198.81  200.51   201.2   201.4     202
                                                                                
                                                                                
          196.74   197.2  197.23   197.1
                                                                                
                                                                                
                                                                                
Pier Skew, UpSta & Num, DnSta & Num=  ,4971.6, 2 ,4971.6, 2 , 0 , 0 , 0 ,,
     1.3     1.3
  190.26   198.3
     1.3     1.3
  190.16   198.2
Pier Skew, UpSta & Num, DnSta & Num=  ,5012.2, 2 ,5012.2, 2 , 0 , 0 , 0 ,,
     1.3     1.3
  189.95  198.32
     1.3     1.3
  189.85  198.22
BR Coef= 1 , 1 , 1 ,1.25, 0 ,,,0.8,-1,2,0,
WSPro=,,,, 1 ,,,, 0 ,,,, 0 ,,,,-1 ,-1 ,-1 , 0 , 0 , 0 , 0 , 0
BR U #Sta/Elev= 30
  2119.9  199.51  2129.5  201.11  2319.8  200.91  2629.5  196.51  3353.7  196.81
  3716.9  196.91  3864.2  196.96  4499.5  196.81    4930  194.01  4944.1  193.82
  4999.5   187.8  5004.8  188.29  5012.3  191.26    5050  194.01  5055.6  194.94
  5223.4  196.11  5593.4  196.61  5663.4  196.11  5723.4  193.61  5763.4  195.21
  5935.1  196.39  6063.4  197.01  6103.4  195.91  6173.4  197.61  6383.4  198.51
  6473.4  200.31  6742.5  199.94  6933.4  198.81  6969.8  200.59  7051.2  202.01
BR U #Mann= 10
  2119.9     .05  2319.8     .05  3353.7     .07  3716.9    .075  3864.2     .04
    4930    .055    5050     .09  5935.1    .045  6742.5     .04  6969.8      .2
BR D #Sta/Elev= 30
  2119.9  199.38  2129.5  200.98  2319.8  200.78  2629.5  196.38  3353.7  196.68
  3716.9  196.78  3864.2  196.83  4499.5  196.68    4930  193.88  4944.1  193.69
  4999.5  187.67  5004.8  188.16  5012.3  191.13    5050  193.88  5055.6  194.81
  5223.4  195.98  5593.4  196.48  5663.4  195.98  5723.4  193.48  5763.4  195.08
  5935.1  196.26  6063.4  196.88  6103.4  195.78  6173.4  197.48  6383.4  198.38
  6473.4  200.18  6742.5  199.81  6933.4  198.68  6969.8  200.46  7051.2  201.88
BR D #Mann= 10
  2119.9     .05  2319.8     .05  3353.7     .07  3716.9    .075  3864.2     .04
    4930    .055    5050     .09  5935.1    .045  6742.5     .04  6969.8      .2
BC Design=,, 0 ,, 0 ,,,,,,
BC HTab HWMax=202.01
BC Use User HTab Curves=0
BC User HTab FreeFlow(D)= 0

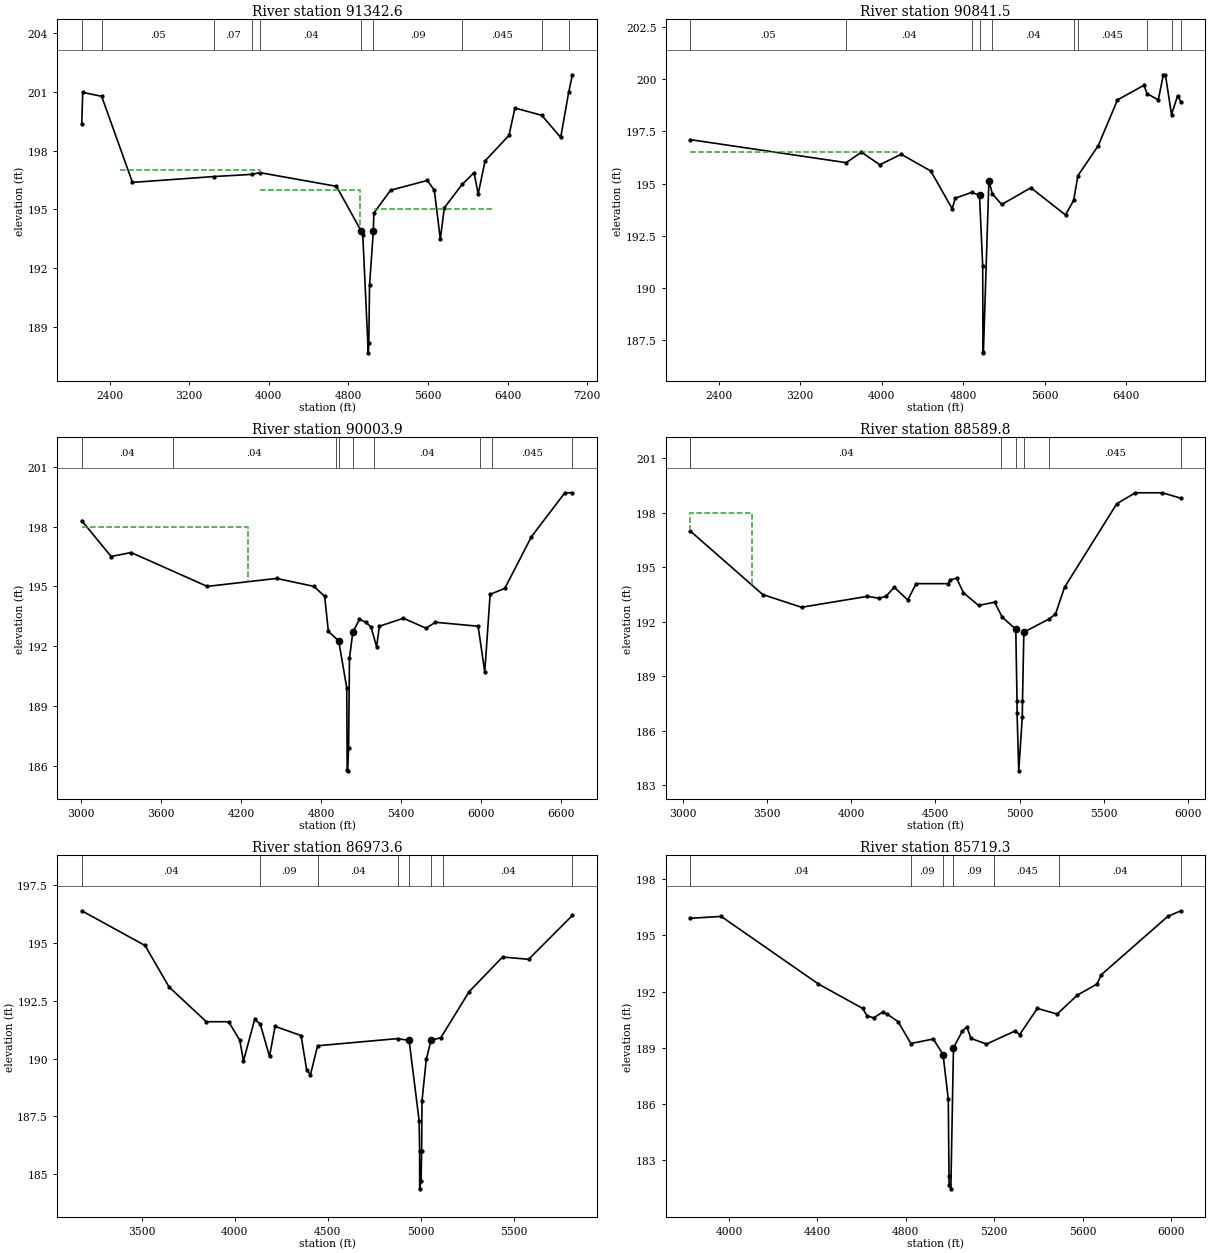
Type RM Length L Ch R = 1 ,91342.6 ,498.8,501.1,558.7
BEGIN DESCRIPTION:
Downstream Section of Bridge/Culvert/Weir
END DESCRIPTION:
XS GIS Cut Line= 5
     2981570.531    13937919.259    2981318.7679   13935152.9438
    2981279.1493   13934939.0033    2981208.2683   13934659.9457
    2981260.6005   13933012.7285
#Sta/Elev= 30
  2119.9  199.38  2129.5  200.98  2319.8  200.78  2629.5  196.38  3449.5  196.68
  3829.9  196.79  3909.5  196.88  4679.5  196.18    4930  193.88  4944.1  193.69
  4999.5  187.67  5004.8  188.16  5012.3  191.13    5050  193.88  5055.6  194.81
  5223.4  195.98  5593.4  196.48  5663.4  195.98  5723.4  193.48  5763.4  195.08
  5943.4  196.28  6063.4  196.88  6103.4  195.78  6173.4  197.48  6413.4  198.78
  6473.4  200.18  6742.5  199.81  6933.4  198.68  7013.4  200.98  7051.2  201.88
#Mann= 10 ,-1 , 0
  2119.9     .05       0  2319.8     .05       0  3449.5     .07       0
  3829.9    .075       0  3909.5     .04       0    4930     .06       0
    5050     .09       0  5943.4    .045       0  6742.5     .04       0
  7013.4      .2       0
#XS Ineff= 3 ,-1
    2500    3909     197    3909    4914     196    5068    6250     195
Permanent Ineff=
       F       F       F
Bank Sta=4930,5050
XS Rating Curve= 0 ,0
Exp/Cntr=0.5,0.3

Type RM Length L Ch R = 1 ,90841.5 ,528.9,837.6,551
BEGIN DESCRIPTION:
Cross Section Becker-DS_Exp
END DESCRIPTION:
XS GIS Cut Line= 5
     2982048.573    13937875.953     2981794.782     13935087.35
    2981748.2555    13934836.107     2981690.178   13934607.4568
    2981738.5071    13933086.241
#Sta/Elev= 30
  2122.5   197.1  3652.5     196  3802.5   196.5  3982.5   195.9  4192.5   196.4
  4482.5   195.6  4692.5   193.8  4722.5   194.3  4883.6  194.58  4960.4  194.44
  4991.6  191.08  4994.9  186.94  4998.5  186.91  5052.6  195.14  5086.4  194.51
  5178.1     194  5464.1   194.8  5804.1   193.5  5884.1   194.2  5926.1  195.38
  6124.1   196.8  6314.1     199  6574.1   199.7  6604.1   199.3  6714.1     199
  6764.1   200.2  6784.1   200.2  6844.1   198.3  6904.1   199.2    6936   198.9
#Mann= 10 ,-1 , 0
  2122.5     .05       0  3652.5     .04       0  4883.6     .09       0
  4960.4     .06       0  5086.4     .04       0  5884.1     .09       0
  5926.1    .045       0  6604.1     .09       0  6844.1     .04       0
    6936      .2       0
#XS Ineff= 2 , 0
       0    4150   196.5               0
Permanent Ineff=
       F       F
Bank Sta=4960.4,5052.6
XS Rating Curve= 0 ,0
Exp/Cntr=0.3,0.1

Type RM Length L Ch R = 1 ,90003.9 ,899,1414.1,881.9
BEGIN DESCRIPTION:
Cross Section XS93
END DESCRIPTION:
XS GIS Cut Line= 2
     2982589.532   13937135.9538    2982050.7186   13933498.9667
#Sta/Elev= 30
    3006   198.3    3226   196.5    3376   196.7    3946     195    4466   195.4
    4746     195    4826   194.5  4853.9  192.74  4931.4  192.26  4991.6  189.91
  4994.9  185.77  4998.5  185.74  5005.6   186.9    5012  191.39  5037.3  192.71
  5086.4  193.34    5133  193.21  5173.2  192.96  5215.6  191.97    5236     193
    5416   193.4    5586   192.9    5656   193.2    5976     193    6026   190.7
    6066   194.6    6176   194.9    6376   197.5    6626   199.7  6682.7   199.7
#Mann= 9 ,-1 , 0
    3006     .04       0  3689.4     .04       0  4907.9     .09       0
  4931.4     .06       0  5037.3     .09       0  5193.3     .04       0
  5991.4     .09       0  6080.2    .045       0  6682.7      .2       0
#XS Ineff= 2 , 0
       0    4255     198               0
Permanent Ineff=
       F       F
Bank Sta=4931.4,5037.3
XS Rating Curve= 0 ,0
Exp/Cntr=0.3,0.1

Type RM Length L Ch R = 1 ,88589.8 ,1074.8,1616.2,1630.2
BEGIN DESCRIPTION:
Cross Section XS92
END DESCRIPTION:
XS GIS Cut Line= 2
     2983239.277   13936074.1754    2982383.5148     13933292.95
#Sta/Elev= 30
  3045.7     197  3475.7   193.5  3705.7   192.8  4095.7   193.4  4165.7   193.3
  4205.7   193.4  4255.7   193.9  4335.7   193.2  4385.7   194.1  4575.7   194.1
  4585.7   194.3  4625.7   194.4  4665.7   193.6  4755.7   192.9  4850.9  193.08
  4895.8  192.26  4976.5  191.59  4983.8  187.63  4984.2  186.96    4994   183.8
  5015.1  186.77  5016.2  187.62 5024.43  191.43  5170.8  192.14  5211.8  192.42
  5265.7   193.9  5575.7   198.5  5685.7   199.1  5845.7   199.1  5955.6   198.8
#Mann= 7 , 1 , 0
  3045.7      .2       0  3045.7     .04       0  4888.9     .09       0
  4975.5     .06       0  5026.1     .09       0  5170.8    .045       0
  5955.6      .2       0
#XS Ineff= 2 , 0
       0    3410     198               0
Permanent Ineff=
       F       F
Bank Sta=4976.5,5024.43
XS Rating Curve= 0 ,0
Exp/Cntr=0.3,0.1

Type RM Length L Ch R = 1 ,86973.6 ,916.5,1254.3,849.7
BEGIN DESCRIPTION:
Cross Section XS91
END DESCRIPTION:
XS GIS Cut Line= 3
      2983587.92   13935963.2434    2983912.7926    13934505.279
    2984514.9953   13933530.6616
#Sta/Elev= 30
  3177.1   196.4  3517.1   194.9  3647.1   193.1  3847.1   191.6  3967.1   191.6
  4027.1   190.8  4047.1   189.9  4107.1   191.7  4137.1   191.5  4187.1   190.1
  4217.1   191.4  4357.1     191  4387.1   189.5  4407.1   189.3  4445.7  190.56
  4876.1  190.87  4938.1  190.79    4992  187.31  4994.5  186.01  4994.9  184.37
  5002.3  184.72  5005.4  186.01 5007.19  188.16  5030.3  189.97    5056   190.8
  5108.8  190.91  5260.8   192.9  5440.8   194.4  5580.8   194.3  5816.5   196.2
#Mann= 8 ,-1 , 0
  3177.1     .04       0  4137.1     .09       0  4445.7     .04       0
  4876.1     .09       0  4938.1     .06       0    5056    .045       0
  5119.1     .04       0  5816.5      .2       0
Bank Sta=4938.1,5056
XS Rating Curve= 0 ,0
Exp/Cntr=0.3,0.1

Type RM Length L Ch R = 1 ,85719.3 ,730.2,1163.6,1032.3
BEGIN DESCRIPTION:
Cross Section XS90
END DESCRIPTION:
XS GIS Cut Line= 2
     2984356.521    13936058.328     2984974.571   13933926.8475
#Sta/Elev= 30
  3824.8   195.9  3964.8     196  4404.8   192.4  4604.8   191.1  4624.8   190.7
  4654.8   190.6  4694.8   190.9  4714.8   190.8  4764.8   190.4  4822.7  189.23
  4924.3  189.47  4968.5  188.64    4992  186.26  4995.3  182.15  4995.9  181.72
  5003.6  181.49  5015.5     189  5056.3  189.91    5076  190.11  5094.8   189.5
  5164.8   189.2  5294.8   189.9  5314.8   189.7  5394.8   191.1  5484.8   190.8
  5574.8   191.8  5664.8   192.4  5684.8   192.9  5984.8     196  6044.1   196.3
#Mann= 7 ,-1 , 0
  3824.8     .04       0  4822.7     .09       0  4968.5     .06       0
  5015.5     .09       0  5198.5    .045       0  5494.8     .04       0
  6044.1      .2       0
Bank Sta=4968.5,5015.5
XS Rating Curve= 0 ,0
Exp/Cntr=0.3,0.1