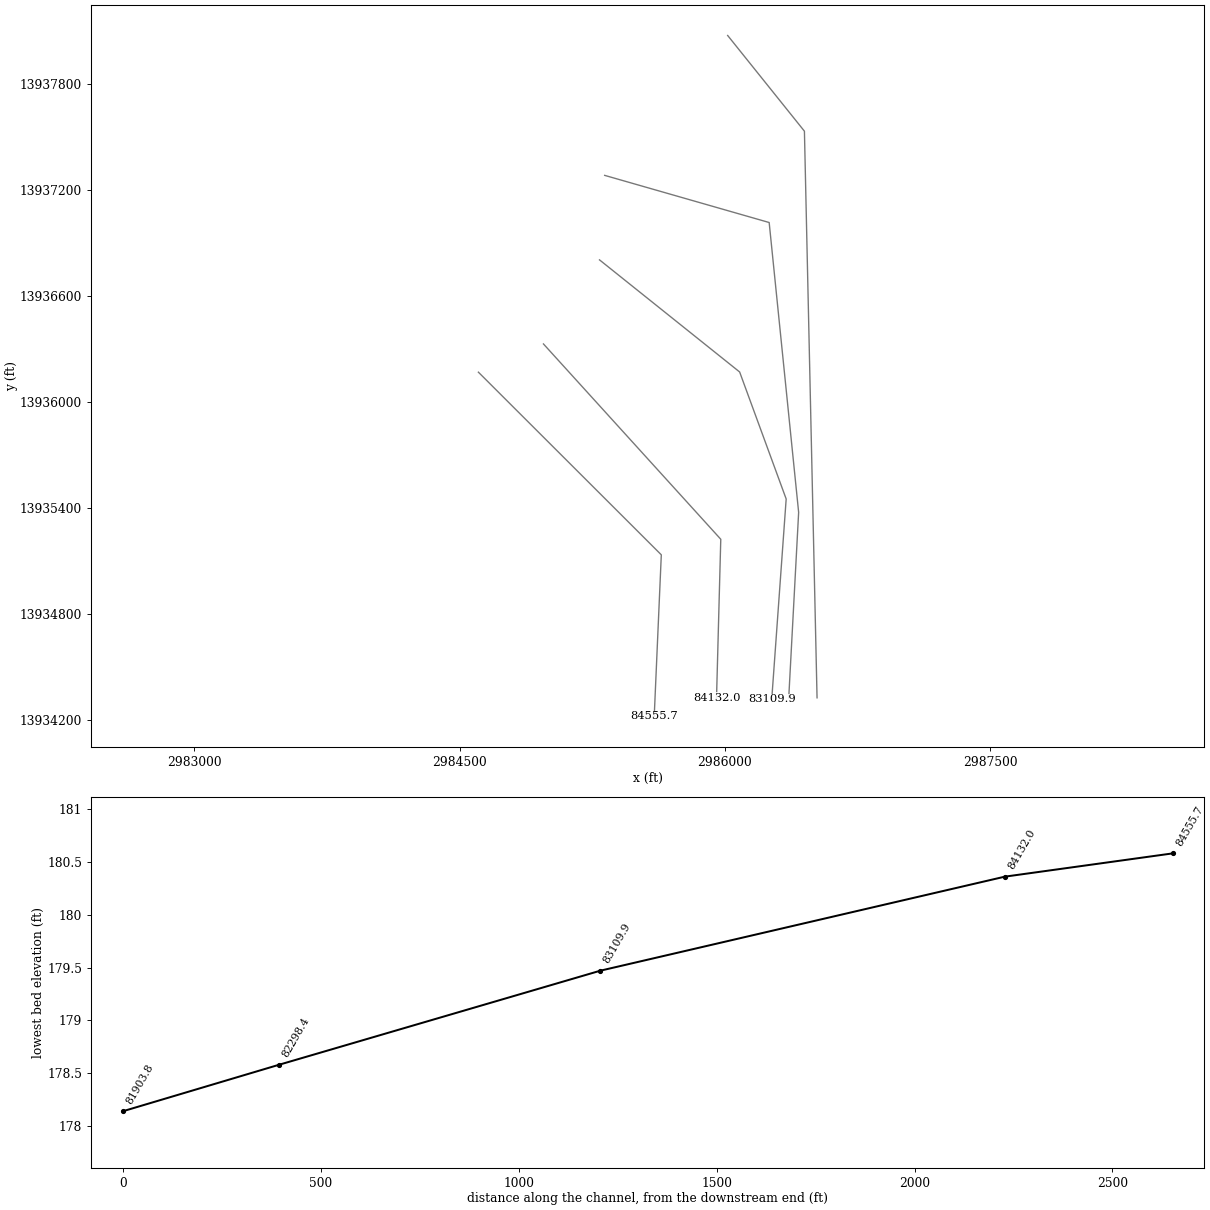
HEC-RAS study L100-00-00.prj: L100-00-00

--- L100-00-00.g01 (geometry) --- (continued)

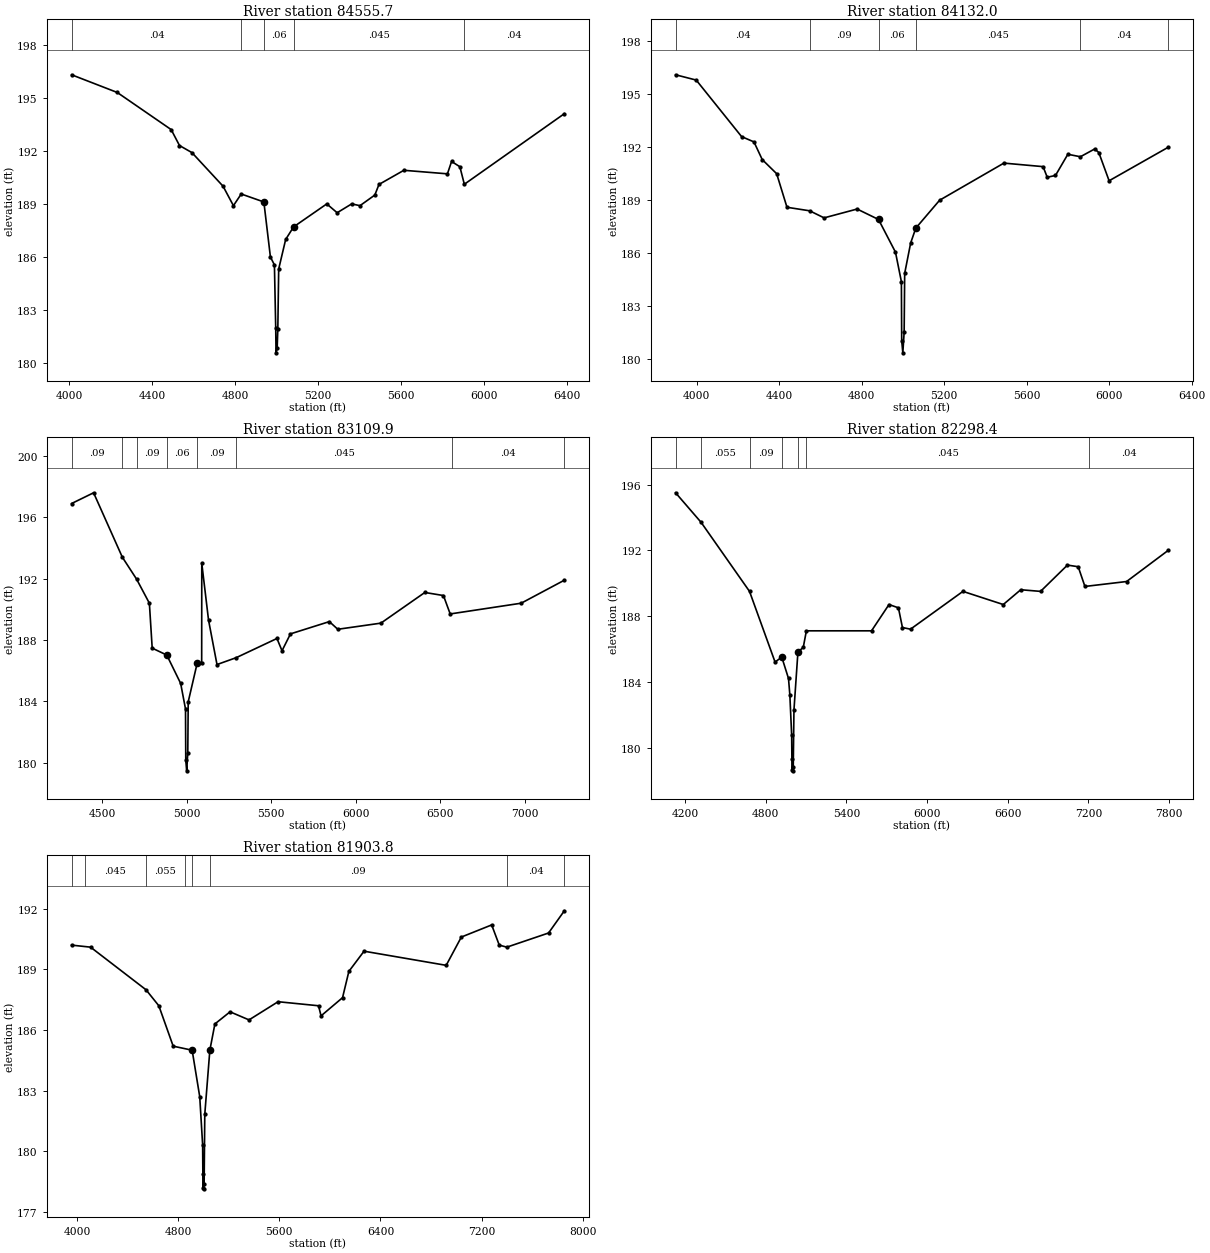
Type RM Length L Ch R = 1 ,84555.7 ,340.7,423.7,311.6
BEGIN DESCRIPTION:
Cross Section XS89
END DESCRIPTION:
XS GIS Cut Line= 3
     2984606.643   13936168.1827    2985640.9172    13935135.379
    2985600.8862   13934222.6716
#Sta/Elev= 30
  4011.1   196.3  4231.1   195.3  4491.1   193.2  4531.1   192.3  4591.1   191.9
  4741.1     190  4791.1   188.9  4828.7  189.56  4937.8  189.11  4969.4     186
  4988.7  185.55    4995  181.97  4996.5  180.58  5001.9  180.83  5005.1  181.92
  5009.3  185.32  5042.9  186.99  5081.1   187.7  5241.1     189  5291.1   188.5
  5361.1     189  5401.1   188.9  5472.7   189.5  5492.7   190.1  5612.7   190.9
  5822.7   190.7  5842.7   191.4  5882.7   191.1  5904.2  190.11  6386.3   194.1
#Mann= 5 ,-1 , 0
  4011.1     .04       0  4828.7     .09       0  4937.8     .06       0
  5081.1    .045       0  5904.2     .04       0
Bank Sta=4937.8,5081.1
XS Rating Curve= 0 ,0
Exp/Cntr=0.3,0.1

Type RM Length L Ch R = 1 ,84132.0 ,707.4,1022.1,714.4
BEGIN DESCRIPTION:
Cross Section XS88
END DESCRIPTION:
XS GIS Cut Line= 3
     2984974.571   13936327.7345    2985977.1778   13935223.4473
    2985953.1592   13934326.7523
#Sta/Elev= 30
    3898   196.1    3998   195.8    4218   192.6    4278   192.3    4318   191.3
    4388   190.5    4438   188.6    4548   188.4    4618     188    4778   188.5
  4881.7  187.91  4963.9  186.06  4992.6  184.39  4994.1  181.05  4999.6  180.36
    5006  181.54  5008.6  184.86  5037.6  186.58  5062.5  187.42    5178     189
  5489.5   191.1  5679.5   190.9  5699.5   190.3  5739.5   190.4  5799.5   191.6
  5860.3  191.46  5929.5   191.9  5949.5   191.7  5999.5   190.1  6286.5     192
#Mann= 6 ,-1 , 0
    3898     .04       0    4548     .09       0  4881.7     .06       0
  5062.5    .045       0  5860.3     .04       0  6286.5      .2       0
Bank Sta=4881.7,5062.5
XS Rating Curve= 0 ,0
Exp/Cntr=0.3,0.1

Type RM Length L Ch R = 1 ,83109.9 ,710.1,811.5,533.5
BEGIN DESCRIPTION:
Cross Section XS87.5
END DESCRIPTION:
XS GIS Cut Line= 4
      2985291.52   13936803.1576    2986083.8917   13936169.2601
    2986347.0245   13935451.1266    2986265.4012   13934318.7461
#Sta/Elev= 30
  4318.8   196.9  4448.8   197.6  4618.8   193.4  4703.1  191.97  4778.8   190.4
  4795.5  187.47  4881.7  187.02  4963.9  185.17  4992.6   183.5  4994.1  180.16
  4999.6  179.47    5006  180.65  5008.6  183.97  5062.5  186.53  5088.2   186.5
  5088.8     193  5128.8   189.3  5178.8   186.4  5292.8  186.85  5533.5   188.1
  5563.5   187.3  5613.5   188.4  5843.5   189.2  5893.5   188.7  6148.4   189.1
  6408.4   191.1  6518.4   190.9  6558.4   189.7  6978.4   190.4  7233.7   191.9
#Mann= 8 ,-1 , 0
  4318.8     .09       0  4618.8    .055       0  4703.1     .09       0
  4881.7     .06       0  5062.5     .09       0  5292.8    .045       0
  6567.5     .04       0  7233.7      .2       0
Bank Sta=4881.7,5062.5
XS Rating Curve= 0 ,0
Exp/Cntr=0.3,0.1

Type RM Length L Ch R = 1 ,82298.4 ,584.2,394.6,353.6
BEGIN DESCRIPTION:
Cross Section XS87.25
END DESCRIPTION:
XS GIS Cut Line= 4
     2985320.669    13937281.042    2986250.8512   13937014.4271
    2986417.5191   13935375.5652    2986361.4757   13934326.7523
#Sta/Elev= 30
  4129.4   195.5  4319.4   193.7  4679.4   189.5  4869.4   185.2  4919.4   185.5
  4969.4   184.2  4979.4   183.2  4992.9  180.75  4994.7  179.32  4994.8  178.64
  5000.1  178.58  5004.7   178.8  5009.9  182.27  5039.4   185.8  5079.4   186.1
  5102.4   187.1    5587   187.1    5717   188.7    5787   188.5    5817   187.3
    5877   187.2    6267   189.5    6567   188.7    6697   189.6  6844.4   189.5
  7044.4   191.1  7124.4     191  7174.4   189.8  7484.4   190.1  7794.7     192
#Mann= 7 ,-1 , 0
  4129.4     .09       0  4319.4    .055       0  4679.4     .09       0
  4919.4     .06       0  5039.4     .09       0  5102.4    .045       0
    7206     .04       0
Bank Sta=4919.4,5039.4
XS Rating Curve= 0 ,0
Exp/Cntr=0.3,0.1

Type RM Length L Ch R = 1 ,81903.8 ,255.9,277.4,261.3
BEGIN DESCRIPTION:
Cross Section XS87
END DESCRIPTION:
XS GIS Cut Line= 3
     2986016.146   13938072.0515    2986450.1982   13937530.9012
    2986521.5998   13934326.7523
#Sta/Elev= 30
  3956.2   190.2  4106.2   190.1    4545  187.99  4646.2   187.2  4759.9   185.2
  4909.9     185  4969.9   182.7  4992.9  180.31  4994.7  178.88  4994.8   178.2
  5000.1  178.14  5004.7  178.36  5009.9  181.83  5049.9     185  5089.9   186.3
  5209.9   186.9  5359.9   186.5  5589.9   187.4  5909.9   187.2  5929.9   186.7
  6099.9   187.6  6149.9   188.9  6269.9   189.9  6919.9   189.2  7039.9   190.6
  7279.9   191.2  7339.9   190.2  7399.9   190.1  7729.9   190.8  7854.9   191.9
#Mann= 8 ,-1 , 0
  3956.2    .055       0  4059.3    .045       0    4545    .055       0
    4853     .09       0  4909.9     .06       0  5049.9     .09       0
  7399.9     .04       0  7854.9      .2       0
Bank Sta=4909.9,5049.9
XS Rating Curve= 0 ,0
Exp/Cntr=0.3,0.1