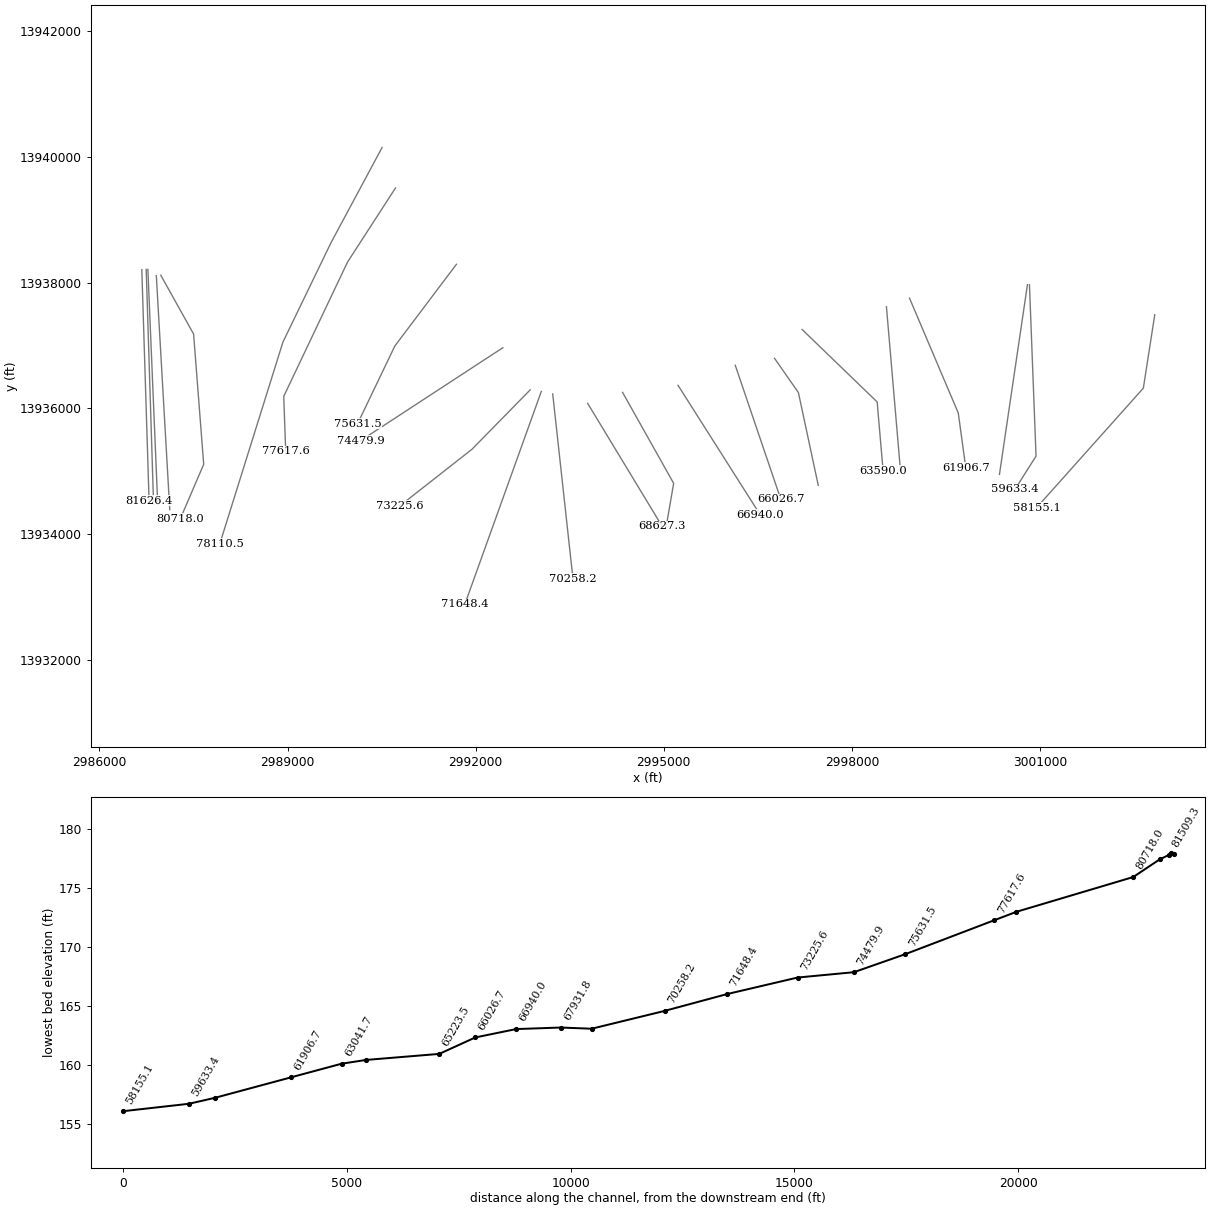
HEC-RAS study L100-00-00.prj: L100-00-00

--- L100-00-00.g01 (geometry) --- (continued)

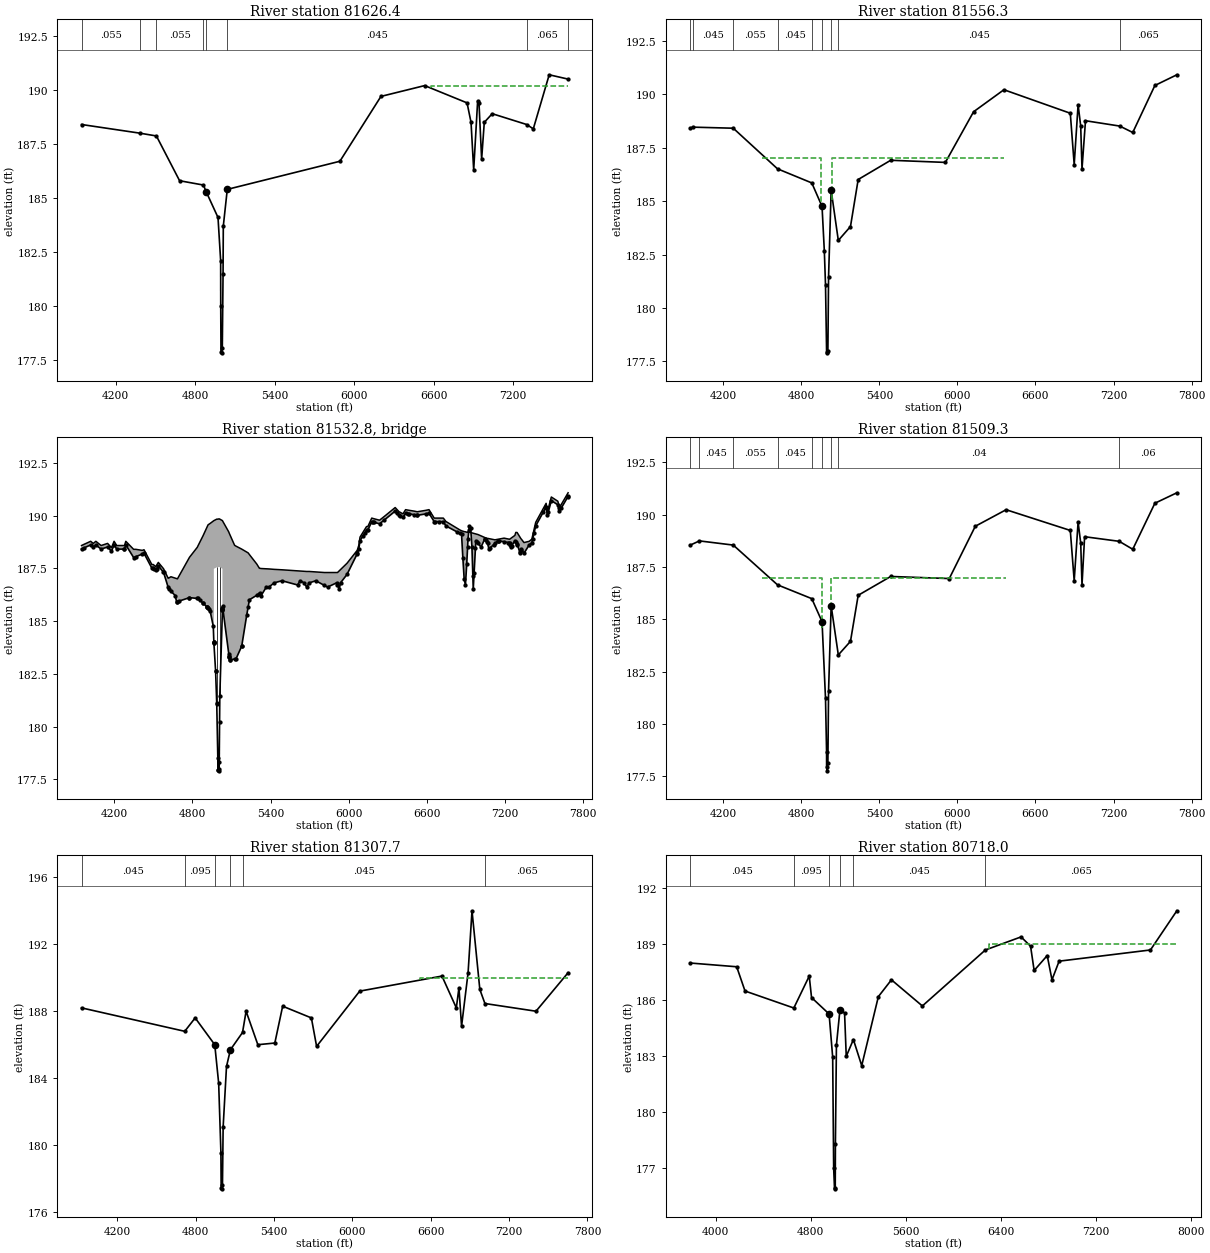
Type RM Length L Ch R = 1 ,81626.4 ,70.1,70.1,70.1
BEGIN DESCRIPTION:
Cross Section Bauer-US_Con
END DESCRIPTION:
XS GIS Cut Line= 2
     2986676.403   13938206.7429    2986792.2086   13934535.9182
#Sta/Elev= 30
  3942.3   188.4  4382.3     188  4507.4  187.87  4682.3   185.8  4862.3   185.6
  4882.3   185.3  4972.3   184.1  4992.3   182.1  4992.9  180.01  4994.8   177.9
  5000.1  177.84  5004.7  178.06  5010.4  181.49  5012.3   183.7  5042.3   185.4
  5892.3   186.7  6202.3   189.7  6532.3   190.2  6852.3   189.4  6882.3   188.5
  6902.3   186.3  6932.3   189.5  6942.3   189.4  6962.3   186.8  6982.3   188.5
  7042.3   188.9  7302.3   188.4  7352.3   188.2  7472.3   190.7    7615   190.5
#Mann= 8 ,-1 , 0
  3942.3    .055       0  4382.3    .045       0  4507.4    .055       0
  4862.3     .09       0  4882.3     .06       0  5042.3    .045       0
  7302.3    .065       0    7615      .2       0
#XS Ineff= 2 , 0
       0                    6580       0   190.2
Permanent Ineff=
       F       F
Bank Sta=4882.3,5042.3
XS Rating Curve= 0 ,0
Exp/Cntr=0.5,0.3

Type RM Length L Ch R = 1 ,81556.3 ,47,47,47
BEGIN DESCRIPTION:
Upstream Section of Bridge/Culvert/Weir
END DESCRIPTION:
XS GIS Cut Line= 2
     2986746.309   13938210.8492    2986864.2012   13934473.8574
#Sta/Elev= 30
  3947.5  188.41  3964.3  188.46  4277.5  188.41  4617.5  186.51    4881  185.85
  4959.8  184.75  4977.5  182.65  4986.4  181.08  4994.8  177.96  5000.1   177.9
  5004.7  177.98  5009.9  181.45  5029.8  185.51  5084.8  183.16  5178.3  183.81
  5237.5  186.01  5487.5  186.91  5907.5  186.81  6124.3  189.18  6357.5  190.21
  6867.5  189.11  6897.5  186.71  6927.5  189.51  6947.5  188.51  6957.5  186.51
  6984.3  188.76  7247.5  188.51  7347.5  188.21  7517.5  190.41  7686.4  190.91
#Mann= 9 ,-1 , 0
  3947.5      .2       0  3964.3    .045       0  4277.5    .055       0
  4617.5    .045       0    4881    .095       0  4959.8     .06       0
  5029.8    .095       0  5084.8    .045       0  7247.5    .065       0
#XS Ineff= 3 ,-1
    4500    4954     187    5040    6358     187    6358    7600   190.2
Permanent Ineff=
       F       F       F
Bank Sta=4959.8,5029.8
XS Rating Curve= 0 ,0
Exp/Cntr=0.5,0.3

Type RM Length L Ch R = 3 ,81532.8 ,,,
BEGIN DESCRIPTION:
BAUER ROAD
Structure ID: L100-00-00-S7
END DESCRIPTION:
Bridge Culvert--1,0,-1,-1, 0
Deck Dist Width WeirC Skew NumUp NumDn MinLoCord MaxHiCord MaxSubmerge Is_Ogee
10,27,2.2,0, 173, 173, , , 0.95, 0, 1,1,,
  3947.5  3964.3  4017.5  4037.5  4057.5  4097.5  4147.5  4177.5  4197.5  4217.5
  4273.2  4277.5  4287.5  4347.5  4364.3  4414.3  4427.5  4487.5  4497.5  4504.3
  4517.5  4524.3  4537.5  4574.3  4577.5    4613  4617.5  4634.3  4667.5  4677.5
  4684.3  4776.2  4776.7  4837.3  4840.2  4854.8    4881  4881.6 4913.69  4913.8
 4913.91  4919.6  4924.7  4936.1  4959.8  4963.9    4964 4964.11  4964.2  4964.3
  4977.5  4977.6  4986.1  4986.4  4994.7  4994.8 4994.91  5000.1  5004.7  5005.4
  5008.1  5009.9  5029.8  5029.9 5029.99  5030.1  5030.2  5030.3  5030.8  5078.2
 5081.19  5081.3 5081.41  5084.5  5084.8  5123.7  5134.5  5177.7  5178.3  5217.5
  5227.8  5237.5  5294.3  5314.3  5317.5  5327.5  5367.5  5387.5  5427.5  5487.5
  5607.5  5627.5  5657.5  5677.5  5697.5  5747.5  5814.3  5837.5  5907.5  5914.3
  5927.5  5937.5  5987.5  6064.3  6067.5  6077.5  6087.5  6107.5  6124.3  6137.5
  6147.5  6177.5  6184.3  6194.3  6237.5  6274.3  6357.5  6374.3  6387.5  6394.3
  6417.5  6437.5  6454.3  6464.3  6504.3  6524.3  6527.5  6594.3  6617.5  6657.5
  6664.3  6694.3  6727.5  6747.5  6854.3  6867.5  6877.5  6887.5  6897.5  6907.5
  6914.3  6917.5  6994.3  7064.3  7067.5  7124.3  7194.3  7224.3  7234.3  7237.5
  7277.5  7284.3  7294.3  7324.3  7327.5  7347.5  7387.5  7407.5  7414.3  7424.3
  7437.5  7494.3  7514.3  7517.5  7527.5  7534.3  7557.5  7607.5  7614.3  7620.2
  7634.3  7684.3  7686.4
  188.58  188.63  188.78  188.68  188.78  188.58  188.68  188.48  188.78  188.58
  188.58  188.58  188.78   188.4   188.4  188.35  188.38  187.68  187.68  187.65
  187.58  187.65  187.78   187.5  187.48  187.03  187.04   187.1  187.03  187.01
     187  188.01  188.02   188.5  188.54  188.72  189.04  189.05  189.48  189.48
  189.48  189.56  189.58  189.63  189.74  189.76  189.76  189.76  189.76  189.76
   189.8   189.8  189.83  189.83  189.83  189.83  189.83  189.84  189.84  189.84
  189.84  189.83  189.76  189.76  189.76  189.76  189.76  189.76  189.75  189.23
  189.18  189.18  189.18  189.14  189.13  188.59  188.55  188.41  188.41  188.27
  188.23  188.15   187.7   187.5   187.5  187.49  187.48  187.47  187.45  187.43
  187.38  187.37  187.36  187.35  187.35  187.33   187.3   187.3   187.3   187.3
  187.38  187.44  187.74  188.34  188.38  188.58  188.98  189.18  189.35  189.48
  189.48  189.88  189.87  189.85  189.78  189.96  190.38  190.27  190.18  190.16
  190.08  190.28  190.26  190.25  190.21  190.18  190.18  190.25  190.28  189.88
  189.88  189.88  189.88  189.72  189.32  189.28  189.26  189.24  189.23  189.21
   189.2  189.23   189.1  188.91  188.92  188.85  188.93  188.89  188.88  188.88
  189.06   189.2   189.2   188.9  188.88  188.72  188.78  188.88  189.06  189.33
  189.68  190.32  190.54  190.58  190.18  190.34  190.88  190.68  190.52  190.38
  190.53  191.06  191.08
                                                                                
                                                                                
                                                                                
                                                                                
                                                  184.17  184.16  187.48  187.48
  187.52  187.52  187.55  187.55  187.55  187.55  187.55  187.56  187.56  187.56
  187.56  187.55  187.48  187.48  187.48
                                                                                
                                                                                
                                                                                
                                                                                
                                                                                
                                                                                
                                                                                
                                                                                
                                                                                
                                                                                
                        
  3947.5  3964.3  4017.5  4037.5  4057.5  4097.5  4147.5  4177.5  4197.5  4217.5
  4273.2  4277.5  4287.5  4347.5  4364.3  4414.3  4427.5  4487.5  4497.5  4504.3
  4517.5  4524.3  4537.5  4574.3  4577.5    4613  4617.5  4634.3  4667.5  4677.5
  4684.3  4776.2  4776.7  4837.3  4840.2  4854.8    4881  4881.6 4913.69  4913.8
 4913.91  4919.6  4924.7  4936.1  4959.8  4963.9    4964 4964.11  4964.2  4964.3
  4977.5  4977.6  4986.1  4986.4  4994.7  4994.8 4994.91  5000.1  5004.7  5005.4
  5008.1  5009.9  5029.8  5029.9 5029.99  5030.1  5030.2  5030.3  5030.8  5078.2
 5081.19  5081.3 5081.41  5084.5  5084.8  5123.7  5134.5  5177.7  5178.3  5217.5
  5227.8  5237.5  5294.3  5314.3  5317.5  5327.5  5367.5  5387.5  5427.5  5487.5
  5607.5  5627.5  5657.5  5677.5  5697.5  5747.5  5814.3  5837.5  5907.5  5914.3
  5927.5  5937.5  5987.5  6064.3  6067.5  6077.5  6087.5  6107.5  6124.3  6137.5
  6147.5  6177.5  6184.3  6194.3  6237.5  6274.3  6357.5  6374.3  6387.5  6394.3
  6417.5  6437.5  6454.3  6464.3  6504.3  6524.3  6527.5  6594.3  6617.5  6657.5
  6664.3  6694.3  6727.5  6747.5  6854.3  6867.5  6877.5  6887.5  6897.5  6907.5
  6914.3  6917.5  6994.3  7064.3  7067.5  7124.3  7194.3  7224.3  7234.3  7237.5
  7277.5  7284.3  7294.3  7324.3  7327.5  7347.5  7387.5  7407.5  7414.3  7424.3
  7437.5  7494.3  7514.3  7517.5  7527.5  7534.3  7557.5  7607.5  7614.3  7620.2
  7634.3  7684.3  7686.4
   188.4  188.46  188.61  188.51  188.61  188.41  188.51  188.35  188.61  188.41
  188.41  188.41  188.61   188.4   188.4  188.18  188.21  187.51  187.51  187.48
  187.47   187.5  187.61  187.33  187.31  187.03  187.04   187.1  187.03  187.01
     187  188.01  188.02   188.5  188.54  188.72  189.04  189.05  189.48  189.48
  189.48  189.56  189.58  189.63  189.74  189.76  189.76  189.76  189.76  189.76
   189.8   189.8  189.83  189.83  189.83  189.83  189.83  189.84  189.84  189.84
  189.84  189.83  189.76  189.76  189.76  189.76  189.76  189.76  189.75  189.23
  189.18  189.18  189.18  189.14  189.13  188.59  188.55  188.41  188.41  188.27
  188.23  188.15   187.7   187.5   187.5  187.49  187.48  187.47  187.45  187.43
  187.38  187.37  187.36  187.35  187.35  187.33   187.3   187.3   187.3   187.3
  187.38  187.44  187.74   188.2  188.21  188.41  188.81  189.01  189.18  189.31
  189.31  189.71   189.7  189.68  189.61  189.79  190.21   190.1  190.01  189.99
  189.91  190.11  190.09  190.08  190.04  190.01  190.01  190.08  190.11  189.78
   189.8   189.8  189.75  189.72   189.3  189.28  189.26  189.24  189.23  189.21
   189.2  189.23   189.1   188.9  188.92  188.68  188.76  188.72   188.8  188.77
  189.06   189.2   189.2   188.9  188.88  188.72  188.61  188.71  188.89  189.16
  189.51  190.15  190.37  190.41  190.01  190.17  190.71  190.51  190.35  190.21
  190.36  190.89   190.9
                                                                                
                                                                                
                                                                                
                                                                                
                                                  183.99  183.98   187.3   187.3
  187.34  187.34  187.37  187.37  187.37  187.37  187.37  187.38  187.38  187.38
  187.38  187.37   187.3   187.3   187.3
                                                                                
                                                                                
                                                                                
                                                                                
                                                                                
                                                                                
                                                                                
                                                                                
                                                                                
                                                                                
                        
Pier Skew, UpSta & Num, DnSta & Num=  ,4986.4, 2 ,4986.4, 2 , 0 , 0 , 0 ,,
       2       2
  179.76  188.37
       2       2
  179.94  188.55
Pier Skew, UpSta & Num, DnSta & Num=  ,5009.9, 2 ,5009.9, 2 , 0 , 0 , 0 ,,
       2       2
  179.75  188.38
       2       2
  179.93  188.56
Abutment Skew #Up #Dn= , 2 , 2
    4964  4977.6
   187.3  182.62
    4964  4977.6
  187.48   182.8
BR Coef= 1 , 1 , 1 ,1.25, 0 ,,,0.8,0,2,0,
WSPro=,,,, 1 ,,,, 0 ,,,, 0 ,,,,-1 ,-1 ,-1 , 0 , 0 , 0 , 0 , 0
BR U #Sta/Elev= 200
  3947.5  188.41  3964.3  188.46  4017.5  188.61  4037.5  188.51  4057.5  188.61
  4097.5  188.41  4147.5  188.51  4177.5  188.31  4197.5  188.61  4217.5  188.41
  4273.2  188.41  4277.5  188.41  4287.5  188.61  4347.5  188.01  4364.3  188.05
  4414.3  188.18  4427.5  188.21  4487.5  187.51  4497.5  187.51  4504.3  187.48
  4517.5  187.41  4524.3  187.48  4537.5  187.61  4574.3  187.33  4577.5  187.31
    4613   186.6  4617.5  186.51  4634.3  186.41  4667.5  186.21  4677.5  185.91
  4684.3  185.92  4694.3  185.94  4776.2  186.11  4776.7  186.11  4837.3  186.07
  4840.2  186.07  4854.8  185.99    4881  185.85  4881.6  185.85 4913.69  185.65
  4913.8  185.65 4913.91  185.65  4919.6  185.61  4924.7  185.58  4936.1  185.46
  4959.8  184.75  4963.9  184.01    4964     184 4964.11  183.99  4964.2  183.98
  4964.3  183.97  4977.5  182.65  4977.6  182.63  4986.1  181.13  4986.4  181.08
  4994.7   178.5  4994.8  177.96 4994.91  177.96  5000.1   177.9  5004.7  177.98
  5005.4  178.32  5008.1   180.2  5009.9  181.45  5029.8  185.51  5029.9  185.53
  5030.1  185.57  5030.2  185.59  5030.3  185.61  5030.8   185.7  5078.2  183.46
 5081.19  183.32  5081.3  183.31 5081.41  183.31  5084.5  183.16  5084.8  183.16
  5123.7   183.2  5134.5  183.21  5177.7   183.8  5178.3  183.81  5217.5  185.31
  5227.8  185.67  5237.5  186.01  5294.3  186.22  5314.3   186.3  5317.5  186.31
  5327.5  186.21  5367.5  186.61  5387.5  186.61  5427.5  186.81  5487.5  186.91
  5607.5  186.71  5627.5  186.91  5657.5  186.81  5677.5  186.61  5697.5  186.81
  5747.5  186.91  5814.3  186.69  5837.5  186.61  5907.5  186.81  5914.3  186.71
  5927.5  186.51  5937.5  186.81  5987.5  187.21  6064.3  188.17  6067.5  188.21
  6077.5  188.41  6087.5  188.81  6107.5  189.01  6124.3  189.18  6137.5  189.31
  6147.5  189.31  6177.5  189.71  6184.3   189.7  6194.3  189.68  6237.5  189.61
  6274.3  189.79  6357.5  190.21  6374.3   190.1  6387.5  190.01  6394.3  189.99
  6417.5  189.91  6437.5  190.11  6454.3  190.09  6464.3  190.08  6504.3  190.04
  6524.3  190.01  6527.5  190.01  6594.3  190.08  6617.5  190.11  6657.5  189.71
  6664.3  189.71  6694.3  189.71  6727.5  189.71  6747.5  189.51  6834.3  189.22
  6854.3  189.15  6867.5  189.11  6877.5  188.01  6887.5  187.01  6897.5  186.71
  6907.5  187.71  6914.3  188.53  6917.5  188.91  6924.3  189.32  6927.5  189.51
  6937.5  189.41  6947.5  188.51  6954.3  187.15  6957.5  186.51  6964.3  187.29
  6974.3  188.44  6977.5  188.81  6984.3  188.76  6994.3  188.68  7017.5  188.51
  7044.3  188.87  7047.5  188.91  7054.3  188.84  7064.3  188.74  7067.5  188.71
  7077.5  188.41  7084.3  188.45  7114.3  188.62  7124.3  188.68  7144.3  188.79
  7147.5  188.81  7154.3   188.8  7194.3  188.76  7224.3  188.72  7234.3  188.71
  7237.5  188.71  7243.4  188.59  7247.5  188.51  7254.3  188.58  7277.5  188.81
  7284.3  188.74  7294.3  188.64  7297.5  188.61  7314.3  188.27  7317.5  188.21
  7324.3  188.35  7327.5  188.41  7347.5  188.21  7387.5  188.61  7407.5  188.71
  7414.3  188.89  7424.3  189.16  7437.5  189.51  7494.3  190.15  7514.3  190.37
  7517.5  190.41  7527.5  190.01  7534.3  190.17  7557.5  190.71  7607.5  190.51
  7614.3  190.35  7620.2  190.21  7634.3  190.36  7684.3  190.89  7686.4  190.91
BR U #Mann= 9
  3947.5      .2  3964.3    .045  4273.2    .055    4613    .045  4854.8    .095
  4959.8    .055  5029.8    .095  5084.8    .045  7243.4    .065
BR D #Sta/Elev= 200
  3947.5  188.55  3964.3   188.6  4017.5  188.75  4037.5  188.65  4057.5  188.75
  4097.5  188.55  4147.5  188.65  4177.5  188.45  4197.5  188.75  4217.5  188.55
  4273.2  188.55  4277.5  188.55  4287.5  188.75  4347.5  188.15  4364.3  188.19
  4414.3  188.32  4427.5  188.35  4487.5  187.65  4497.5  187.65  4504.3  187.62
  4517.5  187.55  4524.3  187.62  4537.5  187.75  4574.3  187.47  4577.5  187.45
    4613  186.74  4617.5  186.65  4634.3  186.55  4667.5  186.35  4677.5  186.05
  4684.3  186.06  4694.3  186.08  4776.2  186.25  4776.7  186.25  4837.3  186.21
  4840.2  186.21  4854.8  186.13    4881  185.99  4881.6  185.99 4913.69  185.79
  4913.8  185.79 4913.91  185.79  4919.6  185.75  4924.7  185.72  4936.1   185.6
  4959.8  184.89  4963.9  184.15    4964  184.14 4964.11  184.13  4964.2  184.12
  4964.3  184.11  4977.5  182.79  4977.6  182.77  4986.1  181.27  4986.4  181.22
  4994.7  178.64  4994.8  177.96 4994.91  177.96  5000.1  177.76  5004.7  178.12
  5005.4  178.46  5008.1  180.34  5009.9  181.59  5029.8  185.65  5029.9  185.67
  5030.1  185.71  5030.2  185.73  5030.3  185.75  5030.8  185.84  5078.2   183.6
 5081.19  183.46  5081.3  183.45 5081.41  183.45  5084.5   183.3  5084.8   183.3
  5123.7  183.34  5134.5  183.35  5177.7  183.94  5178.3  183.95  5217.5  185.45
  5227.8  185.81  5237.5  186.15  5294.3  186.36  5314.3  186.44  5317.5  186.45
  5327.5  186.35  5367.5  186.75  5387.5  186.75  5427.5  186.95  5487.5  187.05
  5607.5  186.85  5627.5  187.05  5657.5  186.95  5677.5  186.75  5697.5  186.95
  5747.5  187.05  5814.3  186.83  5837.5  186.75  5907.5  186.95  5914.3  186.85
  5927.5  186.65  5937.5  186.95  5987.5  187.35  6064.3  188.31  6067.5  188.35
  6077.5  188.55  6087.5  188.95  6107.5  189.15  6124.3  189.32  6137.5  189.45
  6147.5  189.45  6177.5  189.85  6184.3  189.84  6194.3  189.82  6237.5  189.75
  6274.3  189.93  6357.5  190.35  6374.3  190.24  6387.5  190.15  6394.3  190.13
  6417.5  190.05  6437.5  190.25  6454.3  190.23  6464.3  190.22  6504.3  190.18
  6524.3  190.15  6527.5  190.15  6594.3  190.22  6617.5  190.25  6657.5  189.85
  6664.3  189.85  6694.3  189.85  6727.5  189.85  6747.5  189.65  6834.3  189.36
  6854.3  189.29  6867.5  189.25  6877.5  188.15  6887.5  187.15  6897.5  186.85
  6907.5  187.85  6914.3  188.67  6917.5  189.05  6924.3  189.46  6927.5  189.65
  6937.5  189.55  6947.5  188.65  6954.3  187.29  6957.5  186.65  6964.3  187.43
  6974.3  188.58  6977.5  188.95  6984.3   188.9  6994.3  188.82  7017.5  188.65
  7044.3  189.01  7047.5  189.05  7054.3  188.98  7064.3  188.88  7067.5  188.85
  7077.5  188.55  7084.3  188.59  7114.3  188.76  7124.3  188.82  7144.3  188.93
  7147.5  188.95  7154.3  188.94  7194.3   188.9  7224.3  188.86  7234.3  188.85
  7237.5  188.85  7243.4  188.73  7247.5  188.65  7254.3  188.72  7277.5  188.95
  7284.3  188.88  7294.3  188.78  7297.5  188.75  7314.3  188.41  7317.5  188.35
  7324.3  188.49  7327.5  188.55  7347.5  188.35  7387.5  188.75  7407.5  188.85
  7414.3  189.03  7424.3   189.3  7437.5  189.65  7494.3  190.29  7514.3  190.51
  7517.5  190.55  7527.5  190.15  7534.3  190.31  7557.5  190.85  7607.5  190.65
  7614.3  190.49  7620.2  190.35  7634.3   190.5  7684.3  191.03  7686.4  191.05
BR D #Mann= 9
  3947.5      .2  3964.3    .045  4273.2    .055    4613    .045  4854.8    .095
  4959.8    .055  5029.8    .095  5084.8     .04  7243.4     .06
BC Design=,, 0 ,, 0 ,,,,,,
BC HTab HWMax=190.91
BC Use User HTab Curves=0
BC User HTab FreeFlow(D)= 0

Type RM Length L Ch R = 1 ,81509.3 ,150.3,201.6,164.2
BEGIN DESCRIPTION:
Downstream Section of Bridge/Culvert/Weir
END DESCRIPTION:
XS GIS Cut Line= 2
     2986773.029   13938212.0769    2986930.1444   13934476.5296
#Sta/Elev= 30
  3947.5  188.55  4017.5  188.75  4277.5  188.55  4617.5  186.65    4881  185.99
  4959.8  184.89  4986.4  181.22  4994.7  178.64  4994.8  177.96  5000.1  177.76
  5004.7  178.12  5009.9  181.59  5029.8  185.65  5084.8   183.3  5178.3  183.95
  5237.5  186.15  5487.5  187.05  5937.5  186.95  6137.5  189.45  6374.3  190.24
  6867.5  189.25  6897.5  186.85  6927.5  189.65  6947.5  188.65  6957.5  186.65
  6977.5  188.95  7243.4  188.73  7347.5  188.35  7517.5  190.55  7686.4  191.05
#Mann= 9 ,-1 , 0
  3947.5      .2       0  4017.5    .045       0  4277.5    .055       0
  4617.5    .045       0    4881    .095       0  4959.8     .06       0
  5029.8    .095       0  5084.8     .04       0  7243.4     .06       0
#XS Ineff= 3 ,-1
    4500    4962     187    5032    6374     187    6374    7500   190.2
Permanent Ineff=
       F       F       F
Bank Sta=4959.8,5029.8
XS Rating Curve= 0 ,0
Exp/Cntr=0.5,0.3

Type RM Length L Ch R = 1 ,81307.7 ,454.7,589.7,572.1
BEGIN DESCRIPTION:
Cross Section XS86
END DESCRIPTION:
XS GIS Cut Line= 2
    2986907.9585   13938110.5713    2987122.0652   13934390.8019
#Sta/Elev= 30
  3925.7   188.2  4715.8   186.8  4795.7   187.6  4945.7     186  4975.7   183.7
  4992.9  179.56  4994.8  177.45  5000.1  177.39  5004.7  177.61  5009.9  181.08
  5035.7   184.7  5065.7   185.7  5158.4  186.73  5185.7     188  5275.7     186
  5405.7   186.1  5465.7   188.3  5685.7   187.6  5725.7   185.9  6055.7   189.2
  6685.7   190.1  6795.7   188.2  6815.7   189.4  6835.7   187.1  6885.7   190.3
  6915.7     194  6975.7   189.3  7014.6  188.46  7405.7     188  7651.6   190.3
#Mann= 6 ,-1 , 0
  3925.7    .045       0  4715.8    .095       0  4945.7     .06       0
  5065.7    .095       0  5158.4    .045       0  7014.6    .065       0
#XS Ineff= 2 , 0
       0                    6520       0     190
Permanent Ineff=
       F       F
Bank Sta=4945.7,5065.7
XS Rating Curve= 0 ,0
Exp/Cntr=0.3,0.1

Type RM Length L Ch R = 1 ,80718.0 ,2163.2,2607.5,1727.3
BEGIN DESCRIPTION:
Cross Section XS85
END DESCRIPTION:
XS GIS Cut Line= 4
     2986979.272    13938118.495    2987502.2374   13937183.4961
    2987663.3739    13935111.741    2987290.1955   13934246.6902
#Sta/Elev= 30
  3787.2     188  4177.2   187.8  4247.2   186.5  4657.7  185.59  4787.2   187.3
  4806.6  186.15  4954.2  185.27  4984.3  182.96  4992.7  177.01  4999.9   175.9
  5005.9  175.93  5007.3  178.32  5015.9   183.6  5045.6   185.5  5084.3  185.33
  5098.5     183  5158.5   183.9  5228.5   182.5  5368.5   186.2  5478.5   187.1
  5738.5   185.7  6268.5   188.7  6568.5   189.4  6648.5   188.9  6678.5   187.6
  6788.5   188.4  6828.5   187.1  6888.5   188.1  7656.5   188.7  7878.6   190.8
#Mann= 6 ,-1 , 0
  3787.2    .045       0  4657.7    .095       0  4954.2     .06       0
  5045.6    .095       0  5158.5    .045       0  6268.5    .065       0
#XS Ineff= 2 , 0
       0                    6300       0     189
Permanent Ineff=
       F       F
Bank Sta=4954.2,5045.6
XS Rating Curve= 0 ,0
Exp/Cntr=0.3,0.1

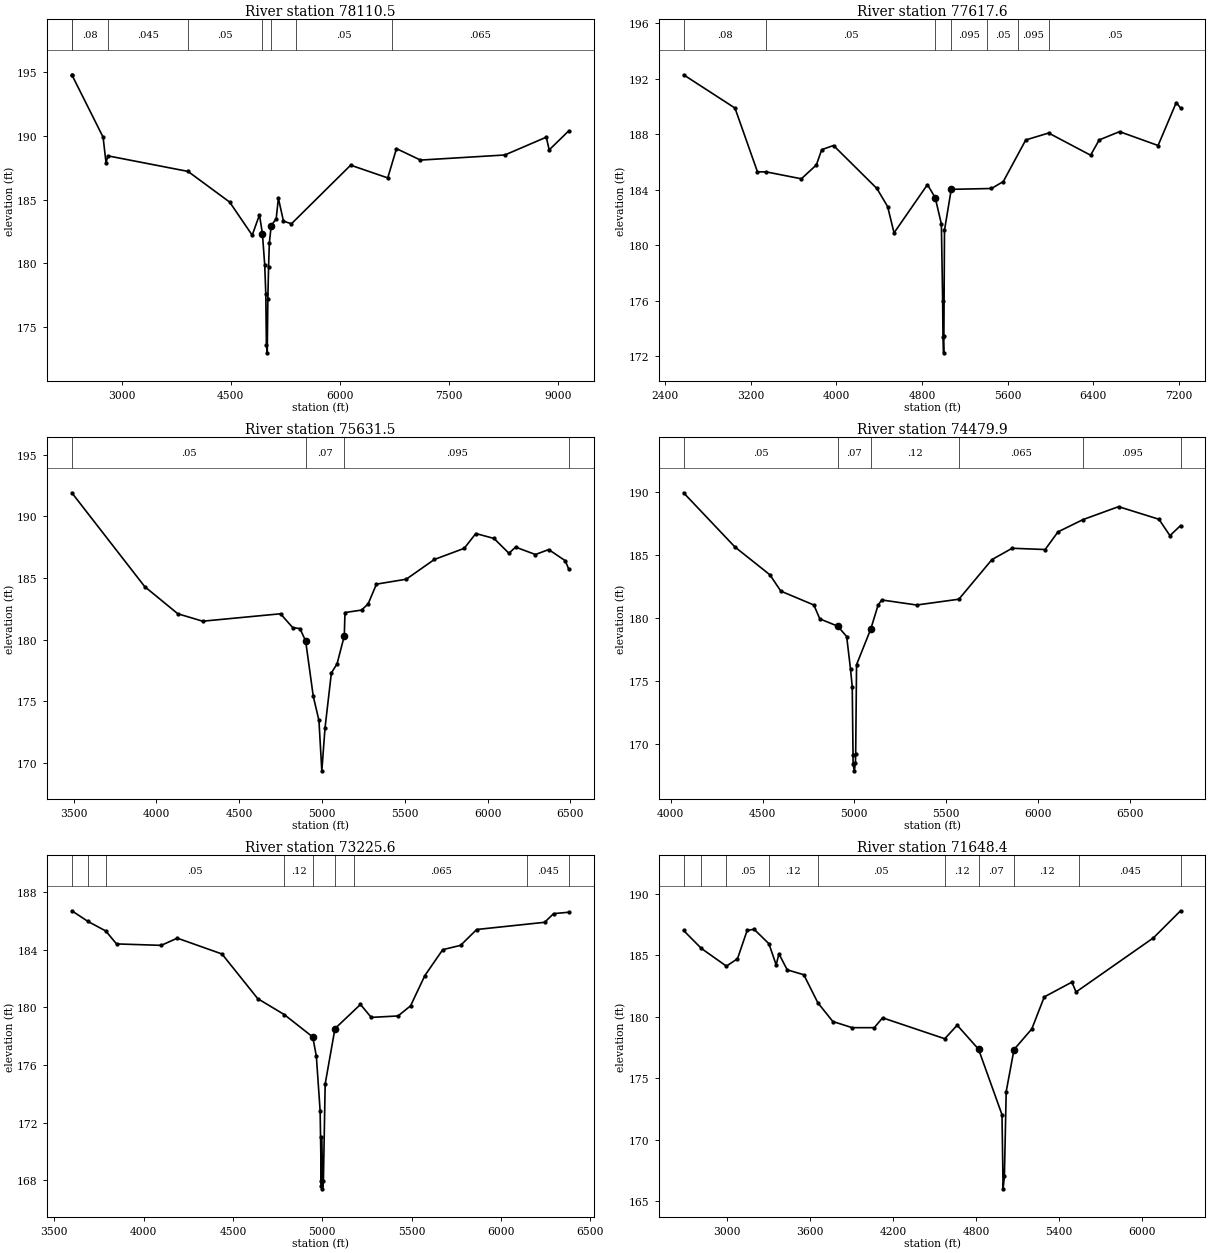
Type RM Length L Ch R = 1 ,78110.5 ,381.5,492.9,387.8
BEGIN DESCRIPTION:
Cross Section XS84
END DESCRIPTION:
XS GIS Cut Line= 4
    2990508.0109    13940149.244    2989692.5995   13938634.2196
    2988926.9808   13937056.2981     2987920.997   13933850.4996
#Sta/Elev= 30
    2315   194.8  2315.1   194.8    2745   189.9    2785   187.9  2812.3  188.43
  3912.6  187.21  4485.4   184.8  4795.4   182.2  4895.4   183.8  4935.8  182.32
  4967.9  179.83  4982.1   177.6  4990.5  173.59    5002  172.96  5010.5   177.2
  5020.4   179.7  5031.3   181.6  5056.8  182.95  5125.4   183.5  5155.4   185.1
  5225.4   183.3  5335.4   183.1  6149.3   187.7  6659.3   186.7  6779.3     189
  7109.3   188.1  8269.3   188.5  8839.3   189.9  8879.3   188.9  9149.3   190.4
#Mann= 8 ,-1 , 0
    2315      .2       0  2315.1     .08       0  2812.3    .045       0
  3912.6     .05       0  4935.8     .06       0  5056.8    .095       0
  5398.5     .05       0  6714.1    .065       0
Bank Sta=4935.8,5056.8
XS Rating Curve= 0 ,0
Exp/Cntr=0.3,0.1

Type RM Length L Ch R = 1 ,77617.6 ,1363.8,1986.1,1596.2
BEGIN DESCRIPTION:
Cross Section XS83
END DESCRIPTION:
XS GIS Cut Line= 4
     2990722.251   13939506.2933    2989956.9384   13938327.7119
    2988939.4738   13936192.1981    2988971.0916   13935322.7081
#Sta/Elev= 30
  2573.5   192.3  3053.5   189.9  3263.5   185.3  3343.5   185.3  3673.5   184.8
  3813.5   185.8  3863.5   186.9  3973.5   187.2  4378.8   184.1  4478.8   182.8
  4538.8   180.9  4850.9  184.38  4923.6  183.43  4980.7  181.54  4992.8  175.97
  4995.7  173.42  5001.8  172.25  5004.3  173.43  5009.9  181.09  5073.1  184.04
  5448.8   184.1  5558.8   184.6  5768.8   187.6  5982.3   188.1  6374.3   186.5
  6454.3   187.6  6644.3   188.2  7004.3   187.2  7174.3   190.3  7214.3   189.9
#Mann= 7 ,-1 , 0
  2573.5     .08       0  3343.5     .05       0  4923.6     .07       0
  5073.1    .095       0  5408.8     .05       0  5698.8    .095       0
  5982.3     .05       0
Bank Sta=4923.6,5073.1
XS Rating Curve= 0 ,0
Exp/Cntr=0.3,0.1

Type RM Length L Ch R = 1 ,75631.5 ,1160.7,1151.6,995.1
BEGIN DESCRIPTION:
Cross Section XS82
END DESCRIPTION:
XS GIS Cut Line= 3
    2991693.8849   13938292.8168    2990711.3437   13936993.3269
    2990117.0647   13935757.2267
#Sta/Elev= 30
  3489.8   191.9  3929.8   184.3  4129.8   182.1  4279.8   181.5  4749.8   182.1
  4823.4  180.98  4867.1   180.9  4901.5   179.9  4947.5  175.42  4981.8  173.46
  4999.2  169.38  5018.5  172.85  5056.9  177.31    5091  178.04  5134.9  180.31
  5138.9   182.2  5238.9   182.4  5278.9   182.9  5328.9   184.5  5508.9   184.9
  5678.9   186.5  5858.9   187.4  5928.9   188.6  6038.9   188.2  6128.9     187
  6168.9   187.5  6288.9   186.9  6368.9   187.3  6468.9   186.4  6490.5   185.7
#Mann= 4 ,-1 , 0
  3489.8     .05       0  4901.5     .07       0  5134.9    .095       0
  6490.5      .2       0
Bank Sta=4901.5,5134.9
XS Rating Curve= 0 ,0
Exp/Cntr=0.3,0.1

Type RM Length L Ch R = 1 ,74479.9 ,1173.6,1254.3,1189.4
BEGIN DESCRIPTION:
Cross Section XS81
END DESCRIPTION:
XS GIS Cut Line= 2
     2992433.804   13936966.0336    2990164.7859   13935488.3458
#Sta/Elev= 30
  4069.5   189.9  4349.5   185.6  4539.5   183.4  4599.5   182.1  4779.5     181
  4811.8   179.9  4909.6  179.32  4958.1   178.5  4979.2   175.9  4988.4  174.52
  4992.8  169.13  4993.1  168.36  4999.8  167.85  5005.9  168.49  5007.2   169.2
    5012  176.27  5089.5   179.1  5129.5     181  5149.5   181.4  5339.5     181
  5569.4  181.46  5749.5   184.6  5859.5   185.5  6039.5   185.4  6109.5   186.8
  6245.3  187.77  6439.5   188.8  6659.5   187.8  6719.5   186.5  6777.3   187.3
#Mann= 6 ,-1 , 0
  4069.5     .05       0  4909.6     .07       0  5089.5     .12       0
  5569.4    .065       0  6245.3    .095       0  6777.3      .2       0
Bank Sta=4909.6,5089.5
XS Rating Curve= 0 ,0
Exp/Cntr=0.3,0.1

Type RM Length L Ch R = 1 ,73225.6 ,1064.5,1577.2,1331.3
BEGIN DESCRIPTION:
Cross Section XS80
END DESCRIPTION:
XS GIS Cut Line= 3
     2992869.843   13936295.8255    2991941.2413   13935351.0742
    2990794.6201   13934454.7717
#Sta/Elev= 30
  3598.8   186.7  3689.1  185.96  3788.4   185.3  3848.8   184.4  4098.8   184.3
  4188.8   184.8  4438.8   183.7  4638.8   180.6  4786.6   179.5  4946.6  177.94
  4966.6   176.6  4987.8   172.8  4994.1  167.92    4995  167.59  4995.3     171
  5000.8   167.4    5006  167.93    5016  174.68  5070.7  178.52  5213.5   180.2
  5273.5   179.3  5423.5   179.4  5493.5   180.1  5573.5   182.2  5673.5     184
  5773.5   184.3  5863.5   185.4  6243.5   185.9  6293.5   186.5  6378.9   186.6
#Mann= 9 ,-1 , 0
  3598.8     .05       0  3689.1     .12       0  3788.4     .05       0
  4786.6     .12       0  4946.6     .07       0  5070.7     .12       0
  5179.6    .065       0  6143.5    .045       0  6378.9      .2       0
Bank Sta=4946.6,5070.7
XS Rating Curve= 0 ,0
Exp/Cntr=0.3,0.1

Type RM Length L Ch R = 1 ,71648.4 ,1022.5,1390.2,1326.9
BEGIN DESCRIPTION:
Cross Section XS79
END DESCRIPTION:
XS GIS Cut Line= 2
    2993047.4885   13936271.6011    2991828.1942    13932888.261
#Sta/Elev= 30
  2684.1     187  2812.8  185.54  2994.1   184.1  3074.1   184.7  3144.1     187
  3194.1   187.1  3301.8  185.92  3354.1   184.2  3374.1   185.1  3434.1   183.8
  3554.1   183.4  3655.9  181.12  3764.1   179.6  3904.1   179.1  4064.1   179.1
  4124.1   179.9  4574.1   178.2  4664.1   179.3  4818.4  177.35  4988.2  172.03
  4996.3     166  5005.6  167.01  5018.7  173.91  5075.2  177.32  5204.1     179
  5294.1   181.6  5494.1   182.8  5524.1     182  6084.1   186.4  6280.4   188.6
#Mann= 10 ,-1 , 0
  2684.1     .05       0  2812.8     .12       0  2994.1     .05       0
  3301.8     .12       0  3655.9     .05       0  4574.1     .12       0
  4818.4     .07       0  5075.2     .12       0  5548.6    .045       0
  6280.4      .2       0
Bank Sta=4818.4,5075.2
XS Rating Curve= 0 ,0
Exp/Cntr=0.3,0.1

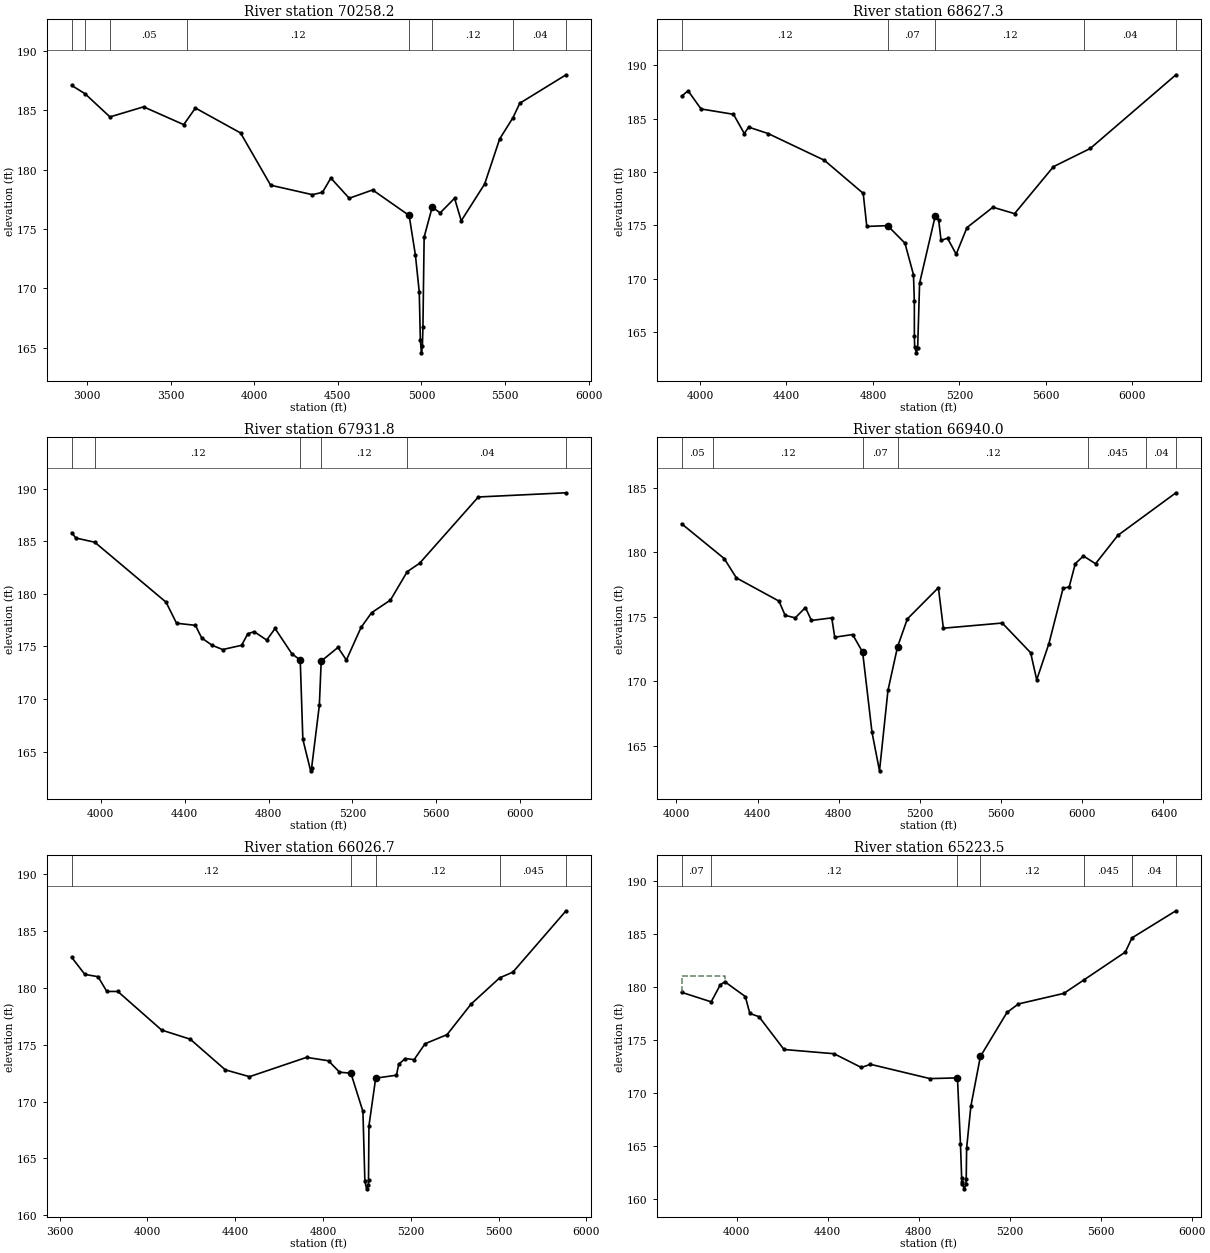
Type RM Length L Ch R = 1 ,70258.2 ,1145.2,1630.9,1477.8
BEGIN DESCRIPTION:
Cross Section XS78
END DESCRIPTION:
XS GIS Cut Line= 2
    2993229.1715   13936231.2271    2993552.1634   13933292.0009
#Sta/Elev= 30
  2908.1   187.1  2988.1   186.4  3137.1  184.45  3338.1   185.3  3578.1   183.8
  3648.1   185.2  3918.1   183.1  4098.1   178.7  4348.1   177.9  4408.1   178.1
  4458.1   179.3  4568.1   177.6  4708.1   178.3  4926.5  176.15  4964.1   172.8
    4987   169.7  4993.6  165.63  5000.2  164.58  5005.7  165.13  5008.9  166.74
  5016.2  174.33  5064.3  176.85  5112.2  176.37  5198.1   177.6  5238.1   175.7
  5378.1   178.8  5468.1   182.6  5548.1   184.4  5588.1   185.6    5865     188
#Mann= 8 ,-1 , 0
  2908.1     .05       0  2988.1     .12       0  3137.1     .05       0
  3597.7     .12       0  4926.5     .07       0  5064.3     .12       0
  5548.1     .04       0    5865      .2       0
Bank Sta=4926.5,5064.3
XS Rating Curve= 0 ,0
Exp/Cntr=0.3,0.1

Type RM Length L Ch R = 1 ,68627.3 ,539.7,695.5,535.4
BEGIN DESCRIPTION:
Cross Section XS77
END DESCRIPTION:
XS GIS Cut Line= 2
    2993786.3325   13936081.8433    2994973.3277   13934127.7424
#Sta/Elev= 30
  3915.2   187.1  3945.2   187.6  4005.2   185.9  4155.2   185.4  4205.2   183.6
  4225.2   184.2  4315.2   183.6  4575.2   181.1  4755.2     178  4771.8   174.9
  4867.9  174.98  4948.2  173.34  4987.7  170.38  4991.7  167.88  4991.8  164.65
  4993.2  163.63  5001.1  163.07    5007  163.49    5016   169.6  5088.8  175.92
  5104.5  175.46  5115.2   173.6  5145.2   173.8  5185.2   172.3  5235.2   174.8
  5355.2   176.7  5455.2   176.1  5635.2   180.5  5805.2   182.2  6201.6   189.1
#Mann= 5 ,-1 , 0
  3915.2     .12       0  4867.9     .07       0  5088.8     .12       0
  5775.2     .04       0  6201.6      .2       0
Bank Sta=4867.9,5088.8
XS Rating Curve= 0 ,0
Exp/Cntr=0.3,0.1

Type RM Length L Ch R = 1 ,67931.8 ,887.1,991.8,982.7
BEGIN DESCRIPTION:
Cross Section XS76
END DESCRIPTION:
XS GIS Cut Line= 4
    2994343.4935   13936255.4515    2995025.8139   13935044.2319
      2995157.88    13934809.794     2995038.886    13934121.582
#Sta/Elev= 30
  3861.1   185.8  3881.1   185.3  3971.1   184.9  4311.1   179.2  4361.1   177.2
  4451.1     177  4481.1   175.8  4531.1   175.1  4581.1   174.7  4671.1   175.1
  4701.1   176.2  4731.1   176.4  4791.1   175.6  4831.1   176.7  4911.1   174.3
  4951.1   173.7  4963.5  166.17  5000.6  163.17  5005.3  163.44  5042.2   169.4
  5051.1   173.6  5131.1   174.9  5171.1   173.7  5241.1   176.8  5291.3   178.2
  5381.3   179.4  5461.3   182.1  5520.4   182.9  5800.4   189.2  6218.8   189.6
#Mann= 6 ,-1 , 0
  3861.1     .05       0  3971.1     .12       0  4951.1     .07       0
  5051.1     .12       0  5461.3     .04       0  6218.8      .2       0
Bank Sta=4951.1,5051.1
XS Rating Curve= 0 ,0
Exp/Cntr=0.3,0.1

Type RM Length L Ch R = 1 ,66940.0 ,847,913.3,717.3
BEGIN DESCRIPTION:
Cross Section XS75
END DESCRIPTION:
XS GIS Cut Line= 2
    2995227.6838   13936368.4986    2996535.8009   13934313.4628
#Sta/Elev= 30
  4025.3   182.2  4235.3   179.5  4295.3     178  4505.3   176.2  4535.3   175.1
  4585.3   174.9  4635.3   175.7  4665.3   174.7  4765.3   174.9    4780   173.4
  4868.2  173.61  4917.5  172.24  4963.5  166.04  5000.6  163.04  5042.2  169.27
  5089.4  172.65  5137.8  174.82  5290.8  177.24  5315.3   174.1  5605.3   174.5
  5745.3   172.2  5775.3   170.1  5835.3   172.9  5905.3   177.2  5935.3   177.3
  5965.3   179.1  6005.3   179.7  6065.3   179.1  6175.3   181.3  6461.4   184.6
#Mann= 7 ,-1 , 0
  4025.3     .05       0  4179.1     .12       0  4917.5     .07       0
  5089.4     .12       0  6025.7    .045       0  6312.8     .04       0
  6461.4      .2       0
Bank Sta=4917.5,5089.4
XS Rating Curve= 0 ,0
Exp/Cntr=0.3,0.1

Type RM Length L Ch R = 1 ,66026.7 ,790.3,803.2,755.2
BEGIN DESCRIPTION:
Cross Section XS74
END DESCRIPTION:
XS GIS Cut Line= 2
    2996140.1359   13936687.4531    2996866.8676   13934555.7067
#Sta/Elev= 30
  3654.8   182.7  3714.8   181.2  3774.8     181  3814.8   179.7  3864.8   179.7
  4064.8   176.3  4194.8   175.5  4354.8   172.8  4464.8   172.2  4724.8   173.9
  4824.8   173.6  4874.8   172.6  4926.9   172.5  4981.6  169.14  4990.5  162.99
  4998.4  162.33  5006.6  162.68    5007  163.08    5009  167.87  5039.7  172.07
  5134.3  172.33  5144.8   173.3  5174.8   173.8  5214.8   173.7  5264.8   175.1
  5364.8   175.9  5474.8   178.6  5604.8   180.9  5664.8   181.4    5907   186.8
#Mann= 5 ,-1 , 0
  3654.8     .12       0  4926.9     .07       0  5039.7     .12       0
  5605.9    .045       0    5907      .2       0
Bank Sta=4926.9,5039.7
XS Rating Curve= 0 ,0
Exp/Cntr=0.3,0.1

Type RM Length L Ch R = 1 ,65223.5 ,902.9,1633.5,1503.3
BEGIN DESCRIPTION:
Cross Section XS73
END DESCRIPTION:
XS GIS Cut Line= 3
    2996766.3655   13936797.8423     2997147.209   13936253.0612
    2997463.5516   13934778.9051
#Sta/Elev= 30
  3758.6   179.5  3888.6   178.6  3928.6   180.2  3948.6   180.5  4038.6   179.1
  4058.6   177.5  4098.6   177.2  4208.6   174.1  4428.6   173.7  4548.6   172.4
  4588.6   172.7  4850.3  171.35  4970.9  171.42  4984.1  165.19  4990.2  161.43
  4990.8  161.93    4991  161.55  5000.1  160.94  5008.8  161.39  5009.4  161.89
  5011.2  164.79  5029.7  168.73  5071.6  173.44  5188.6   177.6  5238.6   178.4
  5438.6   179.4  5528.6   180.7  5708.6   183.3  5737.8  184.64    5931   187.2
#Mann= 7 ,-1 , 0
  3758.6     .07       0  3888.6     .12       0  4970.9     .07       0
  5071.6     .12       0  5528.6    .045       0  5737.8     .04       0
    5931      .2       0
#XS Ineff= 2 , 0
       0  3948.6     181               0
Permanent Ineff=
       F       F
Bank Sta=4970.9,5071.6
XS Rating Curve= 0 ,0
Exp/Cntr=0.3,0.1

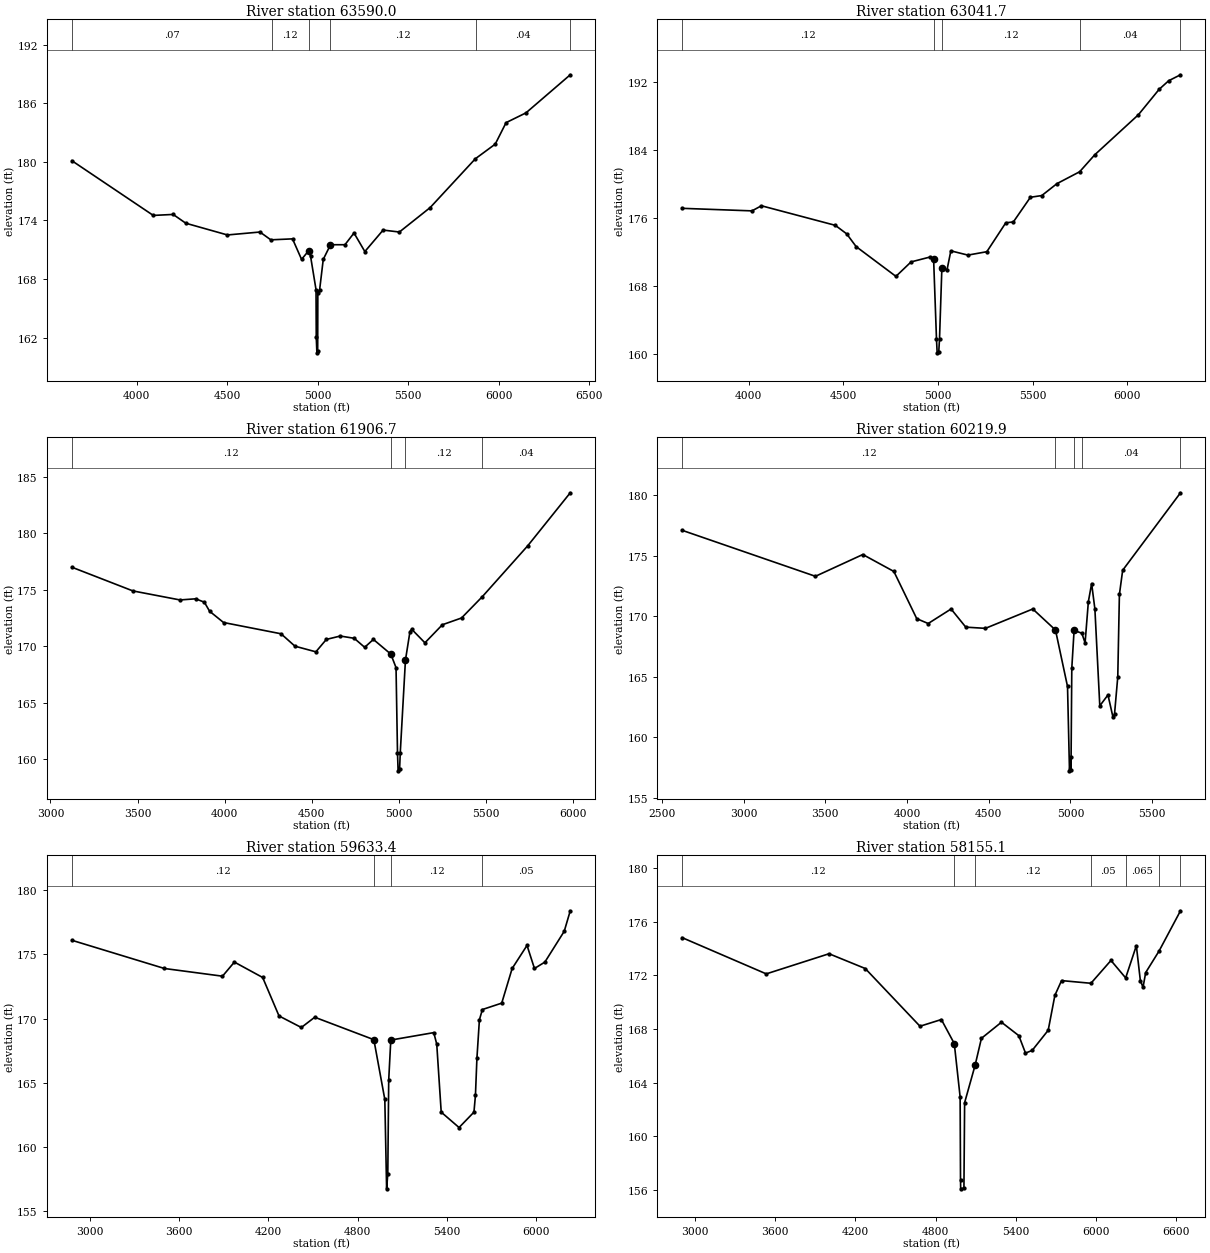
Type RM Length L Ch R = 1 ,63590.0 ,736.9,548.3,361.8
BEGIN DESCRIPTION:
Cross Section XS72.5
END DESCRIPTION:
XS GIS Cut Line= 3
      2997206.48   13937256.0082    2998403.0228   13936103.9967
    2998497.6324   13935013.2032
#Sta/Elev= 30
  3640.7   180.1  4090.7   174.5  4200.7   174.6  4270.7   173.7  4500.7   172.5
  4680.7   172.8  4740.7     172  4860.7   172.1  4910.7     170  4950.7   170.9
  4960.7   170.3  4990.7   166.9    4992  162.03  4995.5  160.43  4999.8  160.57
  5000.7   166.6  5010.7   166.9  5030.7     170  5070.7   171.5  5150.7   171.5
  5200.7   172.7  5260.7   170.8  5361.7     173  5451.7   172.8  5621.7   175.3
  5871.7   180.3  5981.7   181.8  6041.7     184  6151.7     185  6396.6   188.9
#Mann= 6 ,-1 , 0
  3640.7     .07       0  4747.4     .12       0  4950.7     .07       0
  5070.7     .12       0  5874.5     .04       0  6396.6      .2       0
Bank Sta=4950.7,5070.7
XS Rating Curve= 0 ,0
Exp/Cntr=0.3,0.1

Type RM Length L Ch R = 1 ,63041.7 ,869.9,1135,1092.1
BEGIN DESCRIPTION:
Cross Section XS72
END DESCRIPTION:
XS GIS Cut Line= 3
     2998551.003    13937618.915    2998575.7111   13937331.4023
    2998776.2644   13934997.6906
#Sta/Elev= 30
  3649.2   177.1  4017.8   176.8  4067.8   177.4  4457.8   175.1  4517.8   174.1
  4567.8   172.6  4777.8   169.1  4857.8   170.8  4958.9  171.38  4976.7  171.17
    4992  161.71  4995.5  160.11    5004  160.25  5007.9  161.72  5020.3  170.03
  5047.8   169.9  5067.8   172.1  5157.8   171.6  5257.8     172  5357.8   175.4
  5397.8   175.5  5487.8   178.4  5547.8   178.6  5627.8     180  5747.8   181.4
  5827.8   183.4  6057.8   188.1  6167.8   191.1  6217.8   192.1  6280.1   192.8
#Mann= 5 ,-1 , 0
  3649.2     .12       0  4976.7     .07       0  5020.3     .12       0
  5747.8     .04       0  6280.1      .2       0
Bank Sta=4976.7,5020.3
XS Rating Curve= 0 ,0
Exp/Cntr=0.3,0.1

Type RM Length L Ch R = 1 ,61906.7 ,1062.6,1686.8,864.9
BEGIN DESCRIPTION:
Cross Section XS71
END DESCRIPTION:
XS GIS Cut Line= 4
     2998918.936    13937754.768    2999095.3266   13937340.5183
    2999696.9866   13935927.5288    2999815.4954    13935061.503
#Sta/Elev= 30
  3123.4     177  3473.4   174.9  3743.6   174.1  3833.6   174.2  3883.6   173.9
  3913.6   173.1  3993.6   172.1  4323.6   171.1  4403.6     170  4523.6   169.5
  4583.6   170.6  4663.6   170.9  4743.6   170.7  4803.6   169.9  4853.6   170.6
  4953.6   169.3  4983.6   168.1    4992  160.55  4995.5  158.95    5004  159.09
  5007.9  160.56  5037.6  168.76  5063.6   171.3  5073.6   171.5  5149.4   170.3
  5249.4   171.9  5359.4   172.5  5479.4   174.4  5739.4   178.9  5983.5   183.6
#Mann= 4 ,-1 , 0
  3123.4     .12       0  4953.6     .07       0  5037.6     .12       0
  5479.4     .04       0
Bank Sta=4953.6,5037.6
XS Rating Curve= 0 ,0
Exp/Cntr=0.3,0.1

Type RM Length L Ch R = 1 ,60219.9 ,424,586.5,517.9
BEGIN DESCRIPTION:
Cross Section XS70 **Note**
A blocked obstruction was used in lieu of a permanent ineffective flow area due to the flow area cacluation error in RAS version 3.01.
END DESCRIPTION:
XS GIS Cut Line= 2
    3000799.7951   13937968.6804     3000353.343   13934952.1102
#Sta/Elev= 30
  2624.2   177.1  3439.8   173.3  3729.8   175.1  3919.8   173.7  4059.8   169.8
  4129.8   169.4  4269.8   170.6  4359.8   169.1  4479.8     169  4769.8   170.6
  4908.7  168.86  4982.3   164.2  4994.4  157.23  5002.3   158.4  5003.5  157.27
  5008.5  165.72  5022.5  168.83  5069.8   168.6  5089.8   167.8  5109.8   171.2
  5129.8   172.7  5149.8   170.6  5179.8   162.6  5229.8   163.5  5259.8   161.7
  5269.8   161.9  5289.8     165  5299.8   171.8  5319.8   173.8  5673.6   180.2
#Mann= 5 ,-1 , 0
  2624.2     .12       0  4908.7     .07       0  5022.5     .12       0
  5069.8     .04       0  5673.6      .2       0
#Block Obstruct= 2 , 0
       0                    5130       0     170
Bank Sta=4908.7,5022.5
XS Rating Curve= 0 ,0
Exp/Cntr=0.3,0.1

Type RM Length L Ch R = 1 ,59633.4 ,1398.6,1478.3,846.4
BEGIN DESCRIPTION:
Cross Section XS69 **Note**
A blocked obstruction was used in lieu of a permanent ineffective flow area due to the flow area cacluation error in RAS version 3.01.
END DESCRIPTION:
XS GIS Cut Line= 3
    3000831.9738     13937968.52    3000936.8453   13935241.8919
    3000603.6735   13934718.2714
#Sta/Elev= 30
  2879.3   176.1  3501.3   173.9  3891.3   173.3  3971.3   174.4  4161.3   173.2
  4271.3   170.2  4421.3   169.3  4511.3   170.1  4908.7  168.35  4982.3  163.69
  4994.4  156.72  5002.3  157.89  5008.5  165.21  5022.5  168.32  5311.3   168.9
  5331.3     168  5361.3   162.7  5481.3   161.5  5581.3   162.7  5591.3     164
  5601.3   166.9    5618   169.9    5638   170.7    5768   171.2    5838   173.9
    5938   175.7    5988   173.9    6058   174.4    6188   176.8  6228.6   178.4
#Mann= 4 ,-1 , 0
  2879.3     .12       0  4908.7     .07       0  5022.5     .12       0
    5638     .05       0
#Block Obstruct= 2 , 0
       0                  5241.3       0     169
Bank Sta=4908.7,5022.5
XS Rating Curve= 0 ,0
Exp/Cntr=0.3,0.1

Type RM Length L Ch R = 1 ,58155.1 ,1051.9,1352.8,1005.4
BEGIN DESCRIPTION:
Cross Section XS68
END DESCRIPTION:
XS GIS Cut Line= 3
     3002830.325    13937489.681     3002648.093    13936322.836
     3000945.887    13934423.379
#Sta/Elev= 30
  2902.6   174.8  3532.6   172.1  4002.6   173.6  4273.6   172.5  4683.6   168.2
  4843.6   168.7  4940.4  166.91  4984.1  162.94    4987  156.78  4988.2  156.09
  5012.6  156.14  5017.8  162.51  5095.9  165.28  5143.6   167.3  5293.6   168.5
  5423.6   167.5  5473.6   166.2  5523.6   166.4  5643.6   167.9  5693.6   170.5
  5743.6   171.6  5963.6   171.4  6113.6   173.1  6223.6   171.8  6303.6   174.2
  6333.6   171.6  6353.6   171.1  6373.6   172.2  6473.6   173.8  6634.2   176.8
#Mann= 7 ,-1 , 0
  2902.6     .12       0  4940.4     .07       0  5095.9     .12       0
  5963.6     .05       0  6223.6    .065       0  6473.6    .075       0
  6634.2      .2       0
Bank Sta=4940.4,5095.9
XS Rating Curve= 0 ,0
Exp/Cntr=0.3,0.1