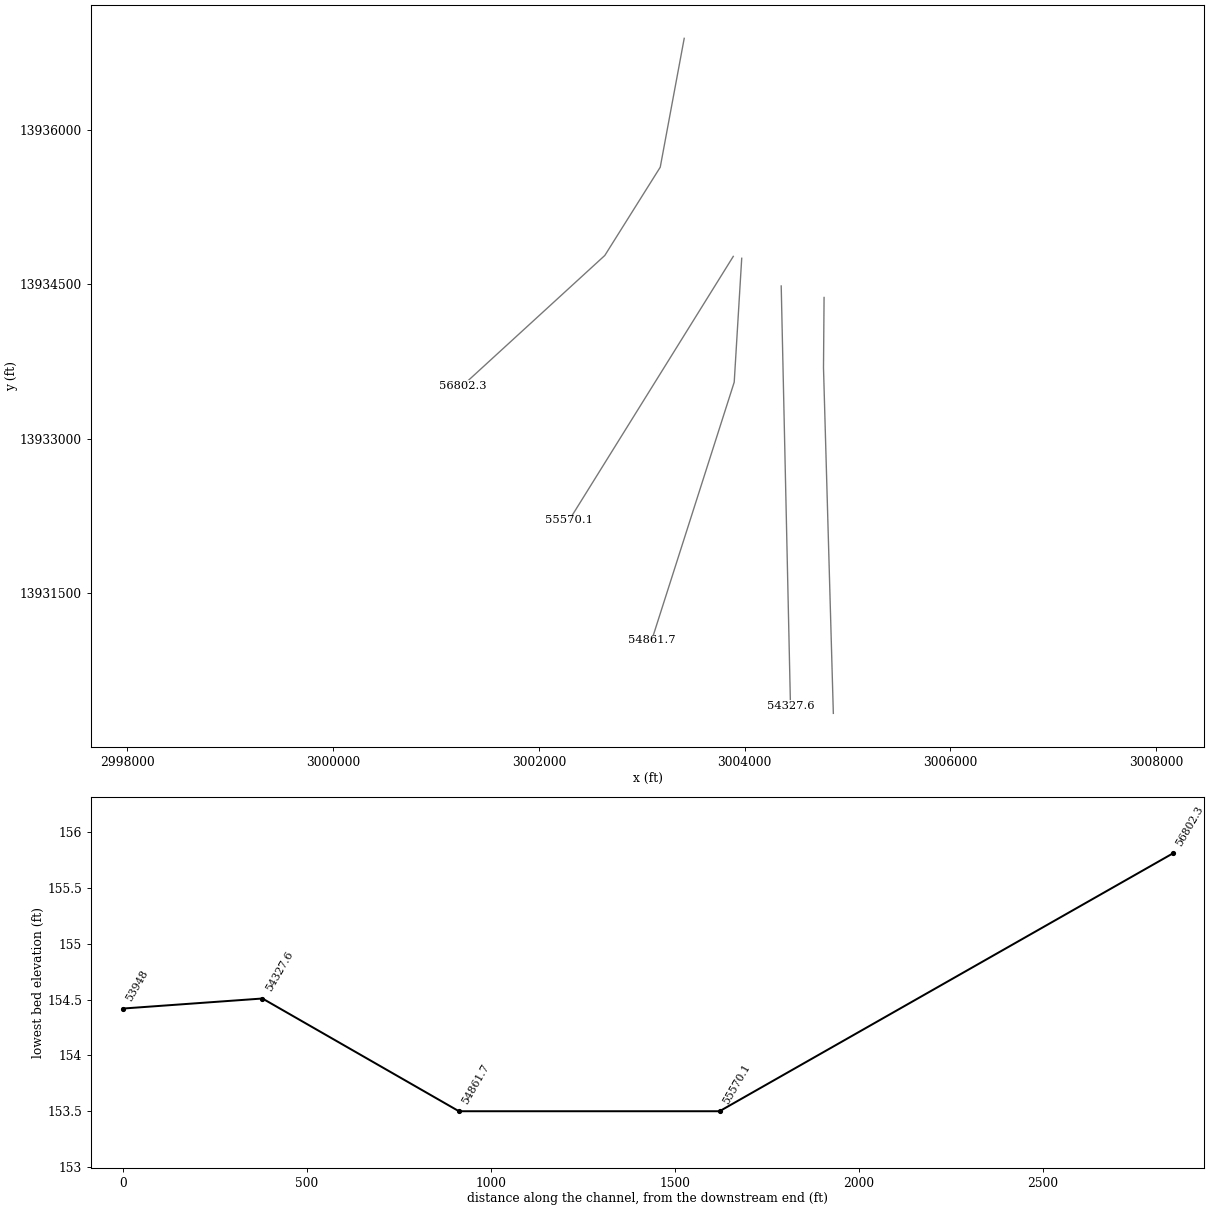
HEC-RAS study L100-00-00.prj: L100-00-00

--- L100-00-00.g01 (geometry) --- (continued)

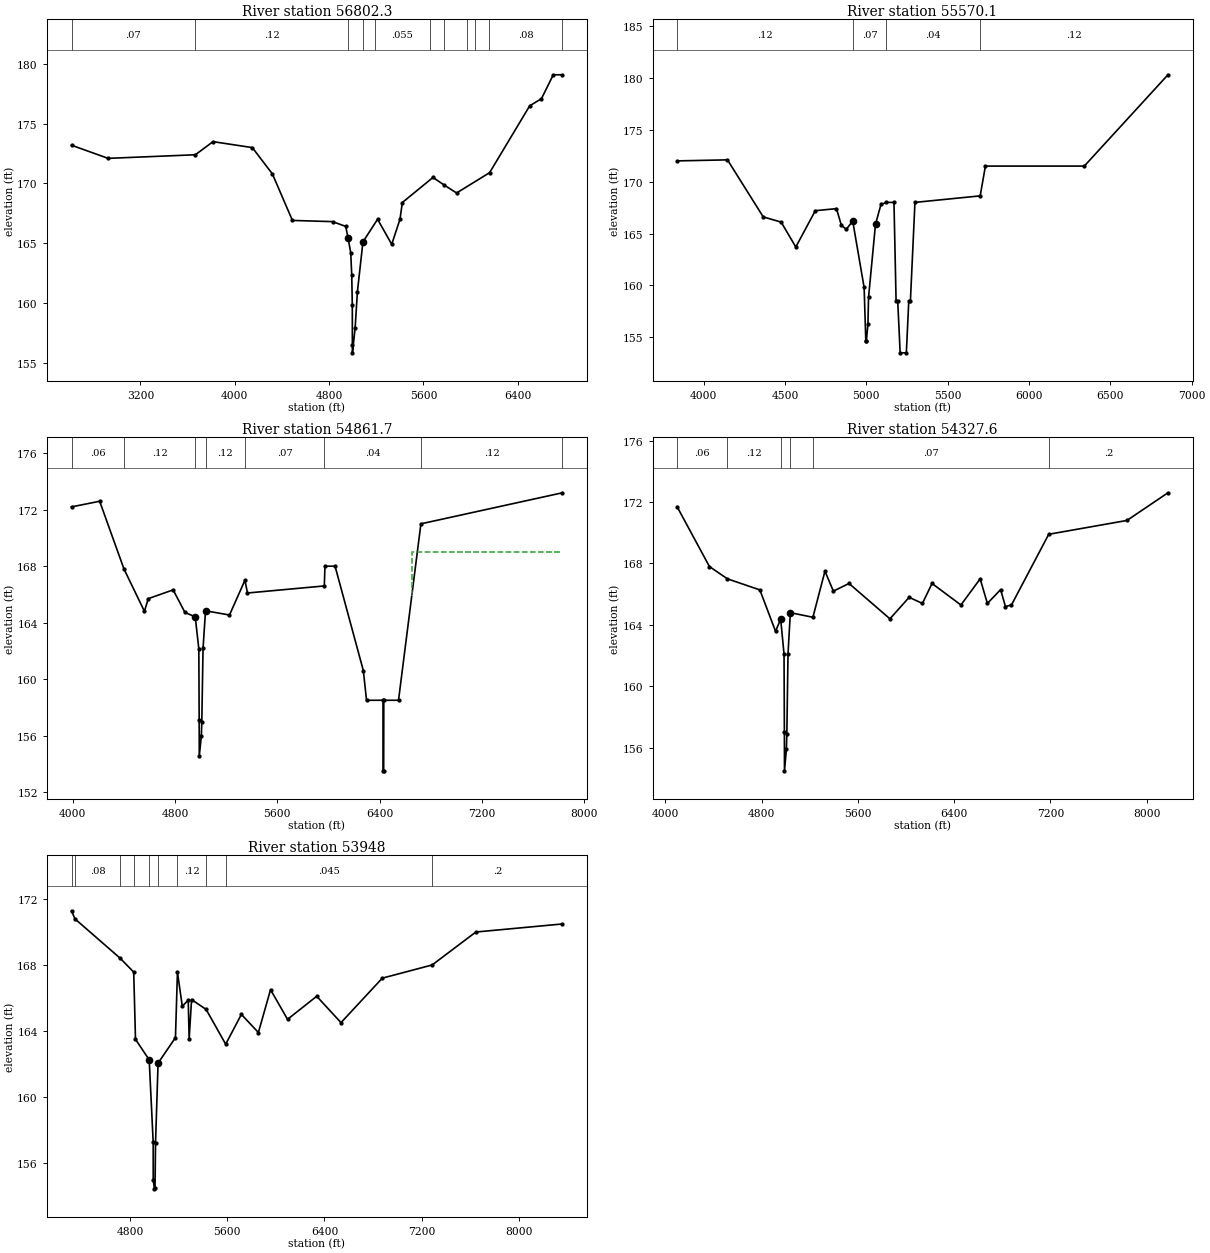
Type RM Length L Ch R = 1 ,56802.3 ,1141.4,1232.2,1268.5
BEGIN DESCRIPTION:
Cross Section XS67
END DESCRIPTION:
XS GIS Cut Line= 4
     3003413.358    13936887.374     3003180.236    13935635.731
    3002641.4745   13934778.9051    3001255.8331   13933511.7725
#Sta/Elev= 30
  2616.1   173.2  2926.1   172.1  3666.1   172.4  3816.1   173.5  4149.3     173
  4319.3   170.8  4489.3   166.9  4829.3   166.8  4941.4   166.4  4960.7  165.45
  4983.7   164.2  4992.3  162.34  4997.2  159.78  4997.6  156.43  4998.3  155.81
  5021.3  157.92  5040.2  160.91  5087.3   165.1  5211.4     167  5331.4   164.9
  5401.4     167  5421.4   168.4  5681.4   170.5  5770.9   169.9  5881.4   169.2
  6161.4   170.9  6501.4   176.5  6601.4   177.1  6701.4   179.1  6779.1   179.1
#Mann= 11 ,-1 , 0
  2616.1     .07       0  3666.1     .12       0  4960.7     .07       0
  5087.3     .12       0  5186.4    .055       0    5659     .08       0
  5770.9     .05       0  5966.3     .08       0  6034.1     .05       0
    6159     .08       0  6779.1      .2       0
Bank Sta=4960.7,5087.3
XS Rating Curve= 0 ,0
Exp/Cntr=0.3,0.1

Type RM Length L Ch R = 1 ,55570.1 ,510.2,708.4,784.4
BEGIN DESCRIPTION:
Cross Section XS66
END DESCRIPTION:
XS GIS Cut Line= 2
    3003890.3749    13934769.789    3002295.0641   13932208.1758
#Sta/Elev= 30
  3836.5     172  4146.5   172.1  4366.5   166.6  4476.5   166.1  4566.5   163.7
  4686.5   167.2  4816.5   167.4  4846.5   165.8  4876.5   165.4  4916.5   166.2
  4986.5   159.8  4996.9  154.66  5000.1  154.62  5009.9  156.28  5013.7  158.85
  5056.5   165.9    5090   167.8    5124     168    5170     168    5183   158.5
    5193   158.5    5208   153.5    5246   153.5    5261   158.5    5271   158.5
    5299     168    5700  168.63    5732   171.5    6340   171.5  6854.3   180.3
#Mann= 4 ,-1 , 0
  3836.5     .12       0  4916.5     .07       0    5124     .04       0
    5700     .12       0
#XS Ineff= 2 , 0
       0                    5729       0   169.8
Permanent Ineff=
       F       F
#Block Obstruct= 2 , 0
       0                    5170       0     168
Bank Sta=4916.5,5056.5
XS Rating Curve= 0 ,0
Exp/Cntr=0.3,0.1

Type RM Length L Ch R = 1 ,54861.7 ,468.9,534.1,673.8
BEGIN DESCRIPTION:
Cross Section XS65
END DESCRIPTION:
XS GIS Cut Line= 3
    3003972.4194   13934751.5569    3003899.4909   13933548.2368
    3003097.2775   13931041.3199
#Sta/Elev= 30
  3991.8   172.2  4211.8   172.6  4401.8   167.8  4561.8   164.8  4591.8   165.7
    4786  166.32  4878.7  164.72  4958.9  164.41  4986.9  162.15  4989.7  157.08
  4990.5  154.55  5006.4  155.95  5010.2  156.94  5019.9  162.17  5039.3  164.84
  5226.7  164.54  5347.3     167  5367.3   166.1    5968   166.6    5973     168
    6052     168    6273   160.6    6298   158.5    6427   158.5    6428   153.5
    6432   153.5    6433   158.5    6548   158.5    6723     171  7829.5   173.2
#Mann= 8 ,-1 , 0
  3991.8     .06       0  4401.8     .12       0  4958.9     .07       0
  5039.3     .12       0  5347.3     .07       0    5968     .04       0
    6723     .12       0  7829.5      .2       0
#XS Ineff= 2 , 0
       0                    6651       0     169
Permanent Ineff=
       F       F
#Block Obstruct= 2 , 0
       0                    6000       0     168
Bank Sta=4958.9,5039.3
XS Rating Curve= 0 ,0
Exp/Cntr=0.3,0.1

Type RM Length L Ch R = 1 ,54327.6 ,358.8,379.6,360.5
BEGIN DESCRIPTION:
Cross Section XS64
END DESCRIPTION:
XS GIS Cut Line= 2
      3004356.35      13934482.4    3004446.4546   13930403.1956
#Sta/Elev= 30
  4097.6   171.7  4366.9   167.8  4516.9     167    4786  166.28  4916.1  163.59
  4958.9  164.37  4986.8  162.11  4989.7  157.04  4990.5  154.51  5006.4  155.91
  5010.2   156.9  5019.9  162.13  5039.3   164.8  5226.7   164.5  5326.9   167.5
  5396.9   166.2  5526.9   166.7  5866.9   164.4  6026.9   165.8  6136.9   165.4
  6216.9   166.7  6456.9   165.3  6616.9     167  6676.9   165.4  6786.9   166.3
  6826.9   165.2  6876.9   165.3  7186.9   169.9  7836.9   170.8  8177.8   172.6
#Mann= 6 ,-1 , 0
  4097.6     .06       0  4516.9     .12       0  4958.9     .07       0
  5039.3     .12       0  5226.7     .07       0  7186.9      .2       0
Bank Sta=4958.9,5039.3
XS Rating Curve= 0 ,0
Exp/Cntr=0.5,0.3

Type RM Length L Ch R = 1 ,53948   ,100,100,100
BEGIN DESCRIPTION:
Upstream Section of Bridge/Culvert/Weir
END DESCRIPTION:
XS GIS Cut Line= 3
      3004773.06      13934370.9     3004767.466   13933688.2196
    3004863.1701   13930331.7383
#Sta/Elev= 30
  4318.2   171.3  4346.2  170.81  4716.9  168.43 4829.95  167.58 4844.71   163.5
  4957.5  162.25  4990.4  157.24  4990.7  154.97  5000.8  154.42  5005.4  154.47
  5009.6  157.18  5030.5  162.05 5173.69   163.6 5190.01  167.58  5229.7  165.51
  5278.8  165.87  5286.2  163.51  5306.2  165.91  5426.2  165.31  5587.1   163.2
  5716.2  165.01  5856.2  163.91  5956.2  166.51  6096.2  164.71  6336.2  166.11
  6536.2  164.51  6876.2  167.21  7286.2  168.01  7646.2  170.01  8358.8   170.5
#Mann= 10 ,-1 , 0
  4318.2     .06       0  4346.2     .08       0  4716.9     .12       0
 4829.95     .04       0  4957.5     .07       0  5030.5     .04       0
 5190.01     .12       0  5426.2     .07       0  5587.1    .045       0
  7286.2      .2       0
#XS Ineff= 2 , 0
       0 4829.95  166.37 5190.01       0  166.37
Permanent Ineff=
       F       F
Bank Sta=4957.5,5030.5
XS Rating Curve= 0 ,0
Exp/Cntr=0.5,0.3