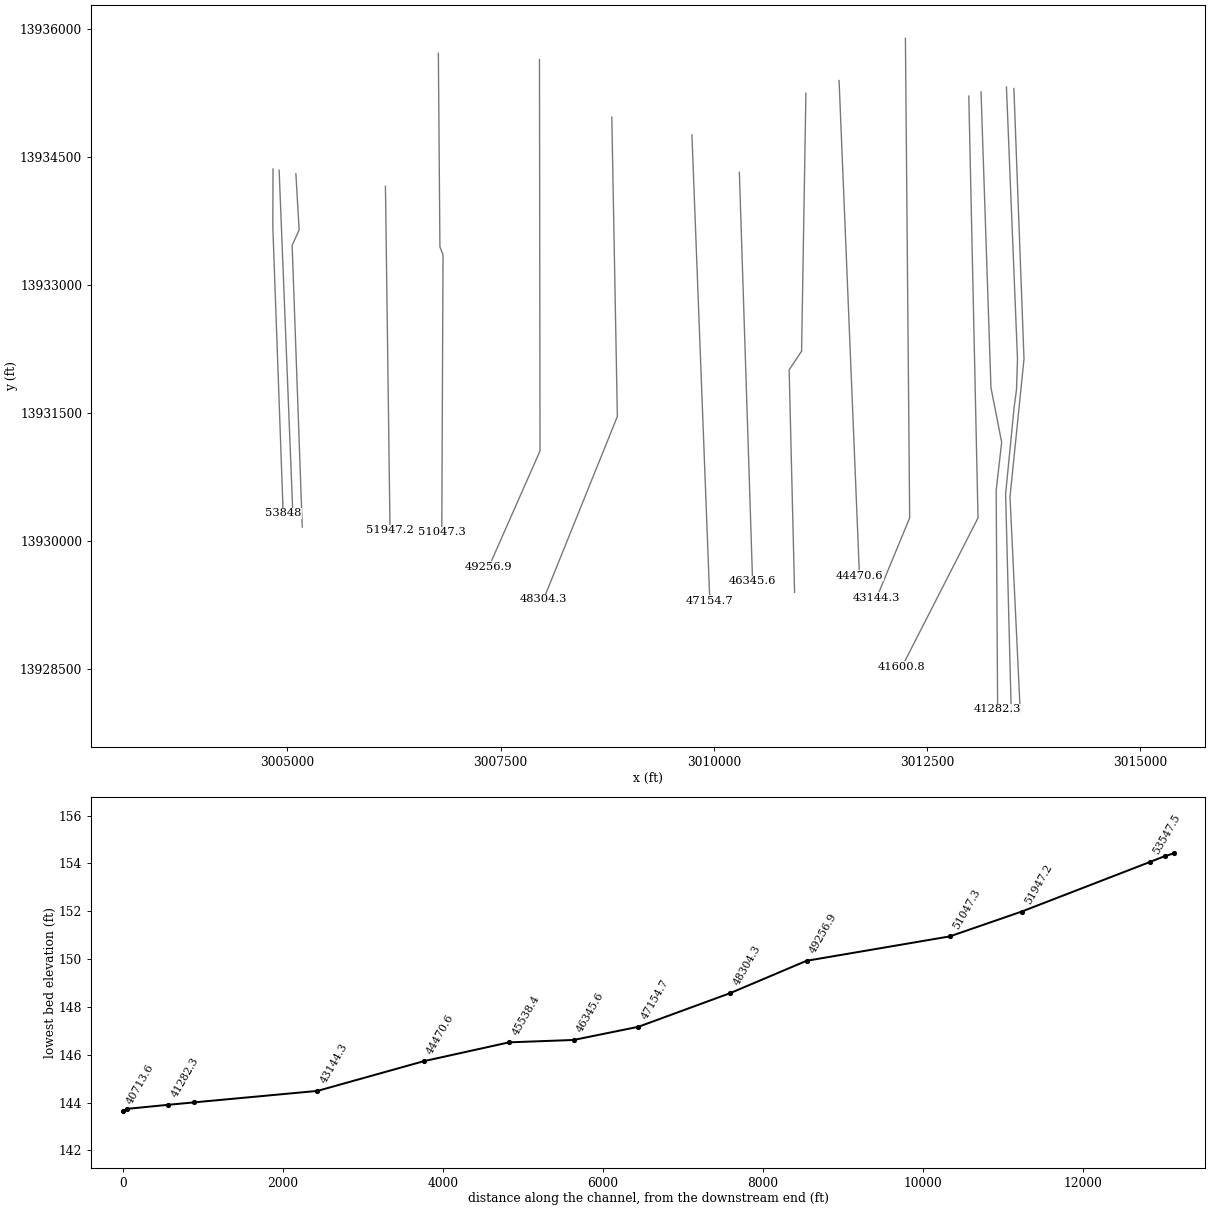
HEC-RAS study L100-00-00.prj: L100-00-00

--- L100-00-00.g01 (geometry) --- (continued)

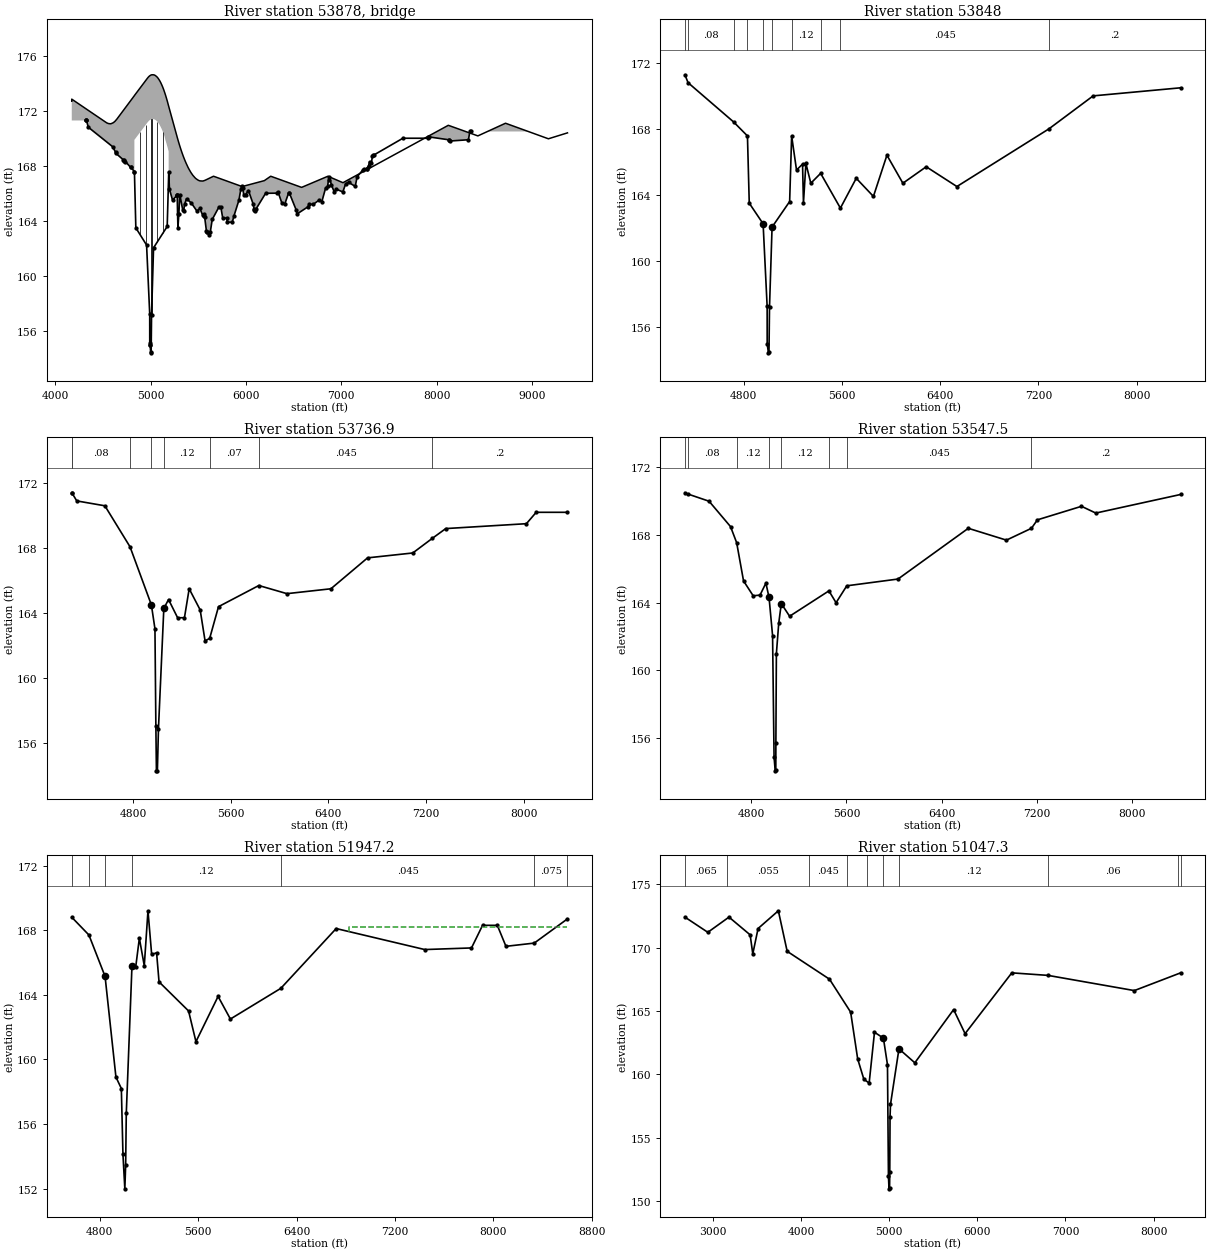
Type RM Length L Ch R = 3 ,53878   ,,,
BEGIN DESCRIPTION:
MUESCHKE
Structure ID: L100-00-00-S5
END DESCRIPTION:
Bridge Culvert--1,0,-1,-1, 0
Deck Dist Width WeirC Skew NumUp NumDn MinLoCord MaxHiCord MaxSubmerge Is_Ogee
10,75,3,0, 81, 81, , , 0.95, 0, 1,1,,
  4172.6  4172.6  4538.8  4545.8  4555.8  4565.8  4575.8  4585.8  4595.8  4605.8
  4615.8  4625.8  4635.8  4645.8    4829  4829.5  4965.3  4975.9  4985.9  4995.9
  5005.9  5015.9  5025.9  5035.9  5045.9  5055.9  5065.9  5075.9  5085.9  5095.9
  5105.9  5115.9  5125.9  5135.9  5145.9  5155.9  5165.9  5175.9  5188.9  5189.4
  5272.6  5282.6  5292.6  5302.6  5312.6  5322.6  5332.6  5342.6  5352.6  5362.6
  5372.6  5382.6  5392.6  5402.6  5412.6  5422.6  5432.6  5442.6  5452.6  5462.6
  5472.6  5482.6  5492.6  5502.6  5512.6  5522.6  5542.6  5552.6  5572.6  5659.6
  5959.6  6192.6  6259.6  6583.6  6859.6  7017.6  8122.6  8432.6  8722.6  9172.6
  9372.8
   172.7  172.85  171.13  171.11  171.08  171.07  171.06  171.07   171.1  171.13
  171.18  171.24  171.32   171.4   173.1  173.11  174.36  174.45  174.52  174.57
  174.61  174.62  174.62  174.61  174.58  174.53  174.47  174.39  174.29  174.18
  174.05   173.9  173.74  173.56  173.36  173.15  172.92  172.68  172.34  172.33
  170.24  169.99  169.75  169.52   169.3  169.09  168.89   168.7  168.52  168.35
  168.19  168.04  167.89  167.76  167.64  167.52  167.42  167.32  167.24  167.16
  167.09  167.04  166.99  166.95  166.92  166.91   166.9  166.91  166.96  167.25
   166.5  166.93  167.25  166.44  167.25  166.78  170.95  170.18   171.1  169.97
   170.4
                                                                                
                                          169.89  171.14  171.23   171.3  171.35
  171.39   171.4   171.4  171.39  171.36  171.31  171.25  171.17  171.07  170.96
  170.83  170.68  170.52  170.34  170.14  169.86  169.63  169.39  169.05
                                                                                
                                                                                
                                                                                
                                                                                
        
  4172.6  4172.6  4538.8  4545.8  4555.8  4565.8  4575.8  4585.8  4595.8  4605.8
  4615.8  4625.8  4635.8  4645.8    4829  4829.5  4965.3  4975.9  4985.9  4995.9
  5005.9  5015.9  5025.9  5035.9  5045.9  5055.9  5065.9  5075.9  5085.9  5095.9
  5105.9  5115.9  5125.9  5135.9  5145.9  5155.9  5165.9  5175.9  5188.9  5189.4
  5272.6  5282.6  5292.6  5302.6  5312.6  5322.6  5332.6  5342.6  5352.6  5362.6
  5372.6  5382.6  5392.6  5402.6  5412.6  5422.6  5432.6  5442.6  5452.6  5462.6
  5472.6  5482.6  5492.6  5502.6  5512.6  5522.6  5542.6  5552.6  5572.6  5659.6
  5959.6  6192.6  6259.6  6583.6  6859.6  7017.6  8122.6  8432.6  8722.6  9172.6
  9372.8
   172.7  172.85  171.13  171.11  171.08  171.07  171.06  171.07   171.1  171.13
  171.18  171.24  171.32   171.4   173.1  173.11  174.36  174.45  174.52  174.57
  174.61  174.62  174.62  174.61  174.58  174.53  174.47  174.39  174.29  174.18
  174.05   173.9  173.74  173.56  173.36  173.15  172.92  172.68  172.34  172.33
  170.24  169.99  169.75  169.52   169.3  169.09  168.89   168.7  168.52  168.35
  168.19  168.04  167.89  167.76  167.64  167.52  167.42  167.32  167.24  167.16
  167.09  167.04  166.99  166.95  166.92  166.91   166.9  166.91  166.96  167.25
   166.5  166.93  167.25  166.44  167.25  166.78  170.95  170.18   171.1  169.97
   170.4
                                                                                
                                          169.89  171.14  171.23   171.3  171.35
  171.39   171.4   171.4  171.39  171.36  171.31  171.25  171.17  171.07  170.96
  170.83  170.68  170.52  170.34  170.14  169.86  169.63  169.39  169.05
                                                                                
                                                                                
                                                                                
                                                                                
        
Pier Skew, UpSta & Num, DnSta & Num=  ,4889.97, 4 ,4889.97, 4 , 3 , 3 , 0 ,,
     1.5     1.5    2.75    2.75
   154.3  167.19  167.19     172
     1.5     1.5    2.75    2.75
   154.3  167.19  167.19     172
Pier Skew, UpSta & Num, DnSta & Num=  ,4949.97, 4 ,4949.97, 4 , 3 , 3 , 0 ,,
     1.5     1.5    2.75    2.75
   154.3  167.75  167.75     172
     1.5     1.5    2.75    2.75
   154.3  167.75  167.75     172
Pier Skew, UpSta & Num, DnSta & Num=  ,5009.97, 4 ,5009.97, 4 , 3 , 3 , 0 ,,
     1.5     1.5    2.75    2.75
   154.3  168.15  168.15     172
     1.5     1.5    2.75    2.75
   154.3  168.15  168.15     172
Pier Skew, UpSta & Num, DnSta & Num=  ,5069.97, 4 ,5069.97, 4 , 3 , 3 , 0 ,,
     1.5     1.5    2.75    2.75
   154.3  167.99  167.99     172
     1.5     1.5    2.75    2.75
   154.3  167.99  167.99     172
Pier Skew, UpSta & Num, DnSta & Num=  ,5129.97, 4 ,5129.97, 4 , 3 , 3 , 0 ,,
     1.5     1.5    2.75    2.75
   154.3   167.2   167.2     172
     1.5     1.5    2.75    2.75
   154.3   167.2   167.2     172
BR Coef= 1 , 1 , 1 ,1.25, 0 ,,,0.8,0,2,0,
WSPro=,,,, 1 ,,,, 0 ,,,, 0 ,,,,-1 ,-1 ,-1 , 0 , 0 , 0 , 0 , 0
BR U #Sta/Elev= 118
  4318.2   171.3  4322.1   171.3  4326.2  171.31  4346.2  170.81  4602.1  169.39
  4632.1  168.99  4636.2  168.91  4712.1  168.45  4716.9  168.43  4722.1  168.39
  4736.2  168.31    4789   167.9  4795.2   167.9 4828.39  167.58 4829.95  167.58
 4844.71   163.5  4957.5  162.25  4990.4  157.24  4990.7  154.97  4991.1     155
  4992.9  155.13  5000.8  154.42  5005.4  154.47  5009.6  157.18  5030.5  162.05
 5173.69   163.6 5190.01  167.58    5197  166.32  5229.7  165.51 5276.79  165.86
 5277.01  165.86  5278.8  165.87  5282.6  164.54  5286.2  163.51  5296.2  164.51
  5306.2  165.91  5336.2  164.81  5346.2  164.71  5356.2  165.21  5376.2  165.61
  5426.2  165.31  5486.2  164.71  5516.2  164.91  5546.2  164.41  5556.2  164.51
  5564.8  164.34  5566.2  164.31  5584.8  163.29  5586.2  163.21  5587.1   163.2
  5616.2  163.01  5626.2  163.21  5646.2  164.11  5716.2  165.01  5736.2  165.01
  5756.2  164.21  5796.2  164.21  5806.2  163.91  5856.2  163.91  5874.8  164.38
  5926.2  165.51  5946.2  166.31  5956.2  166.51  5966.2  166.41  5976.2  165.91
  5996.2  165.91  6026.2  166.21  6076.2  165.21  6084.8  164.87  6086.2  164.81
  6096.2  164.71  6104.8  164.86  6206.2  166.01  6324.8  166.02  6336.2  166.11
  6376.2  165.31  6406.2  165.21  6446.2  166.01  6456.2  166.01  6526.2  164.81
  6536.2  164.51  6646.2  165.01  6666.2  165.21  6706.2  165.21  6766.2  165.51
  6796.2  165.41  6836.2  166.41  6856.2  166.51  6866.2  167.01  6876.2  167.21
  6896.2  166.61  6926.2  166.11  6946.2  166.31  7016.2  166.11  7046.2  166.71
  7076.2  166.81  7146.2  166.51  7166.2  167.21  7226.2  167.71  7236.2  167.76
  7264.8  167.81  7266.2  167.81  7286.2  168.01  7296.2  168.31  7316.2  168.21
  7326.2  168.71  7336.2  168.76  7346.2  168.81  7646.2  170.01  7906.2  170.01
  7914.8   170.1  7916.2  170.11  8124.8   169.9  8126.2  169.91    8144  169.81
  8333.8   169.9  8348.8   170.5  8358.8   170.5
BR U #Mann= 10
  4318.2     .06  4346.2     .08  4716.9     .12 4829.95     .04  4957.5     .07
  5030.5     .04 5190.01     .12  5426.2     .07  5587.1    .045  7286.2      .2
BR U Banks=,5030.5
BR D #Sta/Elev= 95
  4320.5  171.29  4326.2  171.31  4346.2  170.81  4616.2  169.31  4636.2  168.91
  4712.1  168.45  4716.9  168.43  4722.1  168.39  4736.2  168.31  4745.2  168.25
  4795.2   168.2 4828.39  168.15 4829.95  167.58 4844.71   163.5  4957.5  162.25
  4990.4  157.24  4990.7  154.97  4991.1     155  4992.9  155.13  5000.8  154.42
  5005.4  154.47  5009.6  157.18 5026.32  161.59  5030.5  162.05 5173.69   163.6
 5190.01  167.58    5197  166.32  5229.7  165.51 5276.79  165.86 5277.01  165.86
  5278.8  165.87  5282.6  164.54  5286.2  163.51  5296.2  164.51  5306.2  165.91
  5336.2  164.81  5346.2  164.71  5356.2  165.21  5376.2  165.61  5426.2  165.31
  5486.2  164.71  5516.2  164.91  5546.2  164.41  5556.2  164.51  5564.8  164.34
  5566.2  164.31  5584.8  163.29  5586.2  163.21  5587.1   163.2  5616.2  163.01
  5626.2  163.21  5646.2  164.11  5716.2  165.01  5736.2  165.01  5756.2  164.21
  5796.2  164.21  5806.2  163.91  5856.2  163.91  5874.8  164.38  5966.2  166.41
  6026.2  166.21  6076.2  165.21  6084.8  164.87  6086.2  164.81  6096.2  164.71
  6104.8  164.86  6176.2  165.41  6286.2  165.71  6406.2  165.21  6506.2  165.01
  6526.2  164.81  6536.2  164.51  6646.2  165.01  6666.2  165.21  6706.2  165.21
  6766.2  165.51  6836.2  166.41  6856.2  166.51  6896.2  166.61  7046.2  166.71
  7166.2  167.21  7226.2  167.71  7264.8  167.81  7266.2  167.81  7286.2  168.01
  7296.2  168.31  7326.2  168.71  7646.2  170.01  7814.8  170.01  7914.8   170.1
  7916.2  170.11  8096.2  169.61  8333.8   169.9  8348.8   170.5  8358.8   170.5
BR D #Mann= 10
  4320.5     .06  4346.2     .08  4716.9     .12 4829.95     .12  4957.5     .07
  5030.5     .12 5190.01     .12  5426.2     .07  5587.1    .045  7286.2      .2
BR D Banks=,5030.5
BC Design=,, 0 ,, 0 ,,,,,,
BC HTab HWMax=173.71
BC Use User HTab Curves=0
BC User HTab FreeFlow(D)= 0

Type RM Length L Ch R = 1 ,53848   ,99.9,111.1,103.3
BEGIN DESCRIPTION:
Downstream Section of Bridge/Culvert/Weir
END DESCRIPTION:
XS GIS Cut Line= 3
      3004833.03      13934361.3    3004830.8637   13933681.2794
    3004952.0556   13930325.1966
#Sta/Elev= 30
  4320.5  171.29  4346.2  170.81  4716.9  168.43 4829.95  167.58 4844.71   163.5
  4957.5  162.25  4990.4  157.24  4990.7  154.97  5000.8  154.42  5005.4  154.47
  5009.6  157.18  5030.5  162.05 5173.69   163.6 5190.01  167.58  5229.7  165.51
  5278.8  165.87  5286.2  163.51  5306.2  165.91  5346.2  164.71  5426.2  165.31
  5587.1   163.2  5716.2  165.01  5856.2  163.91  5966.2  166.41  6096.2  164.71
  6286.2  165.71  6536.2  164.51  7286.2  168.01  7646.2  170.01  8358.8   170.5
#Mann= 10 ,-1 , 0
  4320.5     .06       0  4346.2     .08       0  4716.9     .12       0
 4829.95     .12       0  4957.5     .07       0  5030.5     .12       0
 5190.01     .12       0  5426.2     .07       0  5587.1    .045       0
  7286.2      .2       0
#XS Ineff= 2 , 0
       0 4829.95  166.87 5190.01       0  166.87
Permanent Ineff=
       F       F
Bank Sta=4957.5,5030.5
XS Rating Curve= 0 ,0
Exp/Cntr=0.5,0.3

Type RM Length L Ch R = 1 ,53736.9 ,210.2,189.4,105
BEGIN DESCRIPTION:
Cross Section XS63
END DESCRIPTION:
XS GIS Cut Line= 2
      3004904.77      13934347.6    3005066.3468   13930293.8028
#Sta/Elev= 30
  4299.7   171.4  4300.6   171.4  4340.6   170.9  4570.6   170.6  4776.5  168.08
  4951.3  164.51  4980.5  163.04    4988  157.07  4992.5  154.33  5000.4  154.31
  5009.2  156.89  5053.1  164.29  5091.7  164.84  5165.9  163.72  5221.9  163.72
  5260.6   165.5  5350.6   164.2  5390.6   162.3  5428.3  162.45  5500.6   164.4
  5830.6   165.7  6060.6   165.2  6420.6   165.5  6720.6   167.4  7090.6   167.7
  7250.6   168.6  7360.6   169.2  8020.6   169.5  8100.6   170.2  8356.7   170.2
#Mann= 8 ,-1 , 0
  4299.7     .06       0  4300.6     .08       0  4776.5     .12       0
  4951.3     .07       0  5053.1     .12       0  5428.3     .07       0
  5830.6    .045       0  7250.6      .2       0
Bank Sta=4951.3,5053.1
XS Rating Curve= 0 ,0
Exp/Cntr=0.3,0.1

Type RM Length L Ch R = 1 ,53547.5 ,1047.1,1600.3,1097.7
BEGIN DESCRIPTION:
Cross Section XS62
END DESCRIPTION:
XS GIS Cut Line= 4
      3005100.99      13934306.1    3005139.2753   13933648.5135
    3005057.2308   13933466.1922    3005175.7395    13930166.178
#Sta/Elev= 30
  4244.7   170.5    4268  170.43  4447.6     170  4627.6   168.5    4679  167.55
  4736.8  165.29  4817.7  164.41  4875.2  164.45  4924.6  165.16  4950.9  164.31
  4980.5  162.06    4993  154.88  5002.6  154.06  5007.6  154.09  5008.2  155.71
  5012.5  160.99  5032.1  162.78  5053.7  163.95  5123.4   163.2  5453.4   164.7
  5513.4     164  5603.4     165  6033.4   165.4  6623.4   168.4  6943.4   167.7
  7153.4   168.4  7203.4   168.9  7573.4   169.7  7693.4   169.3  8405.5   170.4
#Mann= 8 ,-1 , 0
  4244.7     .06       0    4268     .08       0    4679     .12       0
  4950.9     .07       0  5053.7     .12       0  5453.4     .07       0
  5603.4    .045       0  7153.4      .2       0
Bank Sta=4950.9,5053.7
XS Rating Curve= 0 ,0
Exp/Cntr=0.3,0.1

Type RM Length L Ch R = 1 ,51947.2 ,742.2,899.9,659.9
BEGIN DESCRIPTION:
Cross Section XS61
END DESCRIPTION:
XS GIS Cut Line= 3
      3006150.48      13934158.7      3006152.72      13934017.6
    3006204.7034   13930129.2515
#Sta/Elev= 30
  4571.9   168.8  4711.4   167.7  4842.6  165.14  4930.9  158.91  4974.9   158.2
    4988  154.12  5003.3  151.99    5010  153.45  5015.1  156.66  5061.4   165.8
  5091.4   165.7  5121.4   167.5  5161.4   165.8  5191.4   169.2  5221.4   166.5
  5261.4   166.6  5281.4   164.8  5521.4     163  5581.4   161.1  5761.4   163.9
  5861.4   162.5  6271.4   164.4  6721.4   168.1  7441.4   166.8  7821.4   166.9
  7911.4   168.3  8031.4   168.3  8101.4     167  8331.4   167.2  8601.7   168.7
#Mann= 7 ,-1 , 0
  4571.9    .045       0  4711.4     .12       0  4842.6     .07       0
  5061.4     .12       0  6271.4    .045       0  8331.4    .075       0
  8601.7      .2       0
#XS Ineff= 2 , 0
       0                    6825       0   168.2
Permanent Ineff=
       F       F
Bank Sta=4842.6,5061.4
XS Rating Curve= 0 ,0
Exp/Cntr=0.3,0.1

Type RM Length L Ch R = 1 ,51047.3 ,1313.1,1790.4,1278.9
BEGIN DESCRIPTION:
Cross Section XS60
END DESCRIPTION:
XS GIS Cut Line= 4
    3006771.0503   13935717.8594    3006789.2824   13933447.9601
    3006825.7467   13933356.7995    3006811.0424   13930101.6906
#Sta/Elev= 30
  2683.5   172.4  2943.5   171.2  3183.5   172.4  3423.5     171  3453.5   169.5
  3513.5   171.5  3743.5   172.9  3843.5   169.7  4323.5   167.5  4563.5   164.9
  4643.5   161.2  4713.5   159.6  4773.5   159.3    4834  163.31  4935.1  162.85
  4981.3  160.75  4992.2  151.98  4998.7  150.95  5005.1     151  5007.4   152.3
  5010.6  156.65  5015.5  157.61  5111.7     162  5291.7   160.9  5731.7   165.1
  5861.7   163.2  6391.7     168    6802   167.8  7781.7   166.6  8306.8     168
#Mann= 10 ,-1 , 0
  2683.5    .065       0  3161.1    .055       0  4088.2    .045       0
  4522.6     .06       0  4751.1     .12       0  4935.1     .07       0
  5111.7     .12       0    6802     .06       0  8282.6    .075       0
  8306.8      .2       0
Bank Sta=4935.1,5111.7
XS Rating Curve= 0 ,0
Exp/Cntr=0.3,0.1

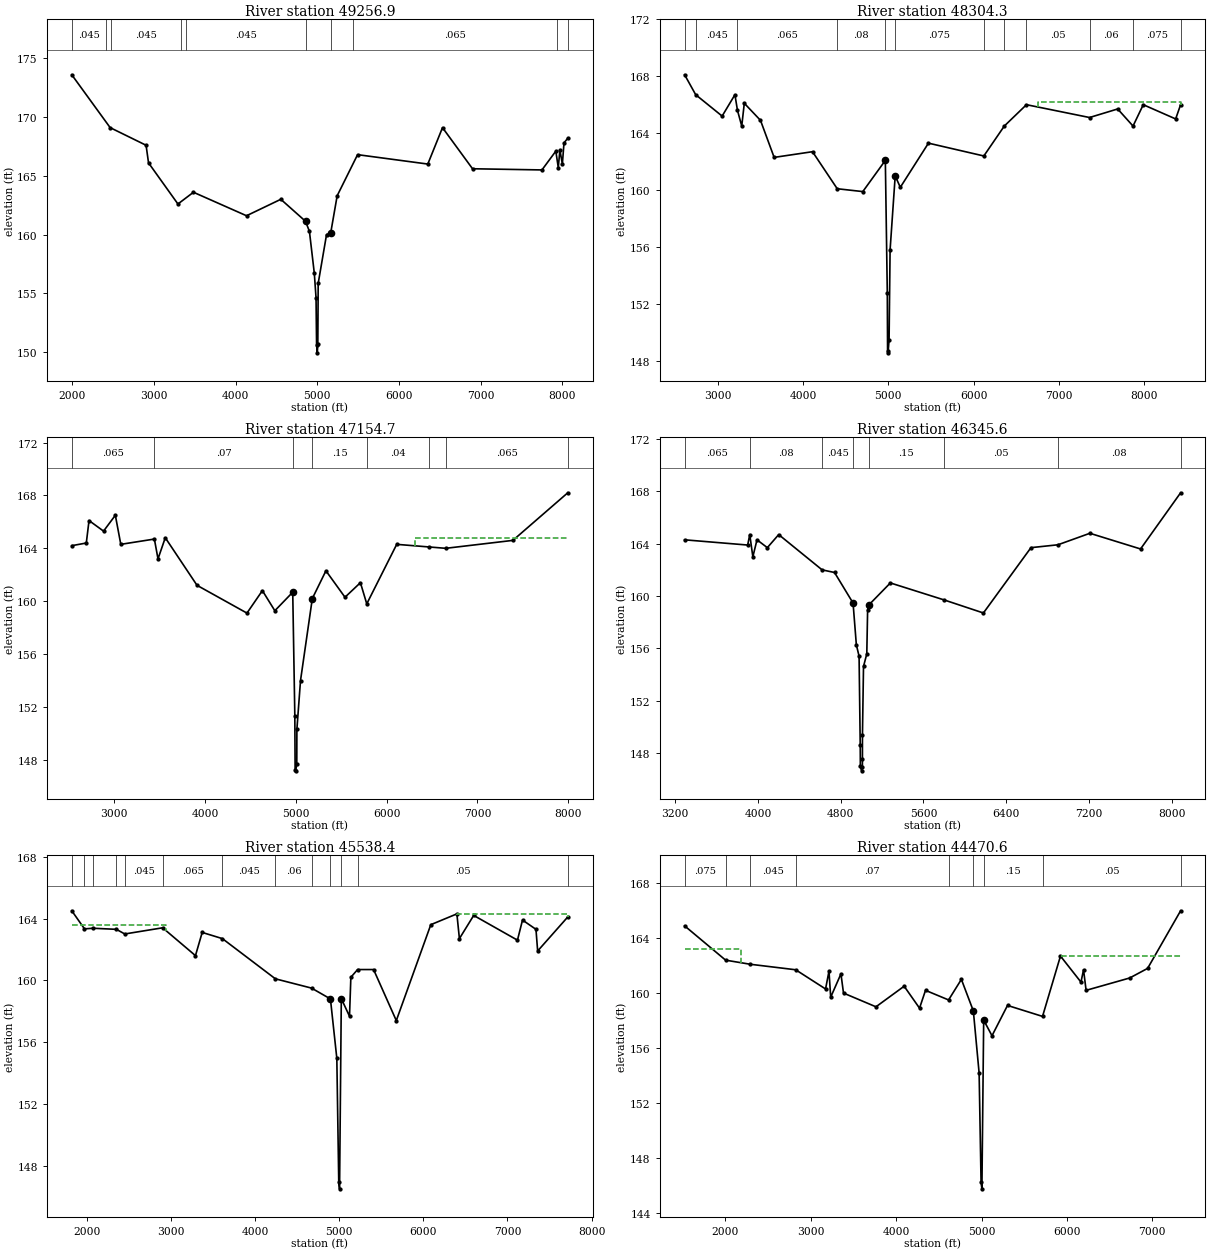
Type RM Length L Ch R = 1 ,49256.9 ,904.5,952.6,951.8
BEGIN DESCRIPTION:
Cross Section XS59
END DESCRIPTION:
XS GIS Cut Line= 3
    3007956.1383   13935644.9309    3007962.4663   13931057.1254
    3007362.2596   13929697.4646
#Sta/Elev= 30
  1993.9   173.6  2463.9   169.1  2903.9   167.6  2933.9   166.1  3293.9   162.6
  3483.9   163.6  4133.9   161.6  4553.9     163  4856.3  161.13  4904.2  160.27
  4964.1   156.7  4985.2  154.61  4991.9   150.6  5000.5  149.93    5007  150.67
  5011.6  155.84  5113.9     160  5163.9   160.1  5243.9   163.3  5493.9   166.8
  6353.9     166  6533.9   169.1  6901.7   165.6  7751.7   165.5  7921.7   167.1
  7951.7   165.7  7971.7   167.2  8001.7     166  8021.7   167.8    8068   168.2
#Mann= 10 ,-1 , 0
  1993.9    .045       0  2418.3    .065       0  2472.7    .045       0
  3329.8    .055       0  3394.3    .045       0  4856.3     .07       0
  5163.9     .12       0  5435.7    .065       0  7941.2    .075       0
    8068      .2       0
Bank Sta=4856.3,5163.9
XS Rating Curve= 0 ,0
Exp/Cntr=0.3,0.1

Type RM Length L Ch R = 1 ,48304.3 ,1007.6,1149.6,1022.8
BEGIN DESCRIPTION:
Cross Section XS58
END DESCRIPTION:
XS GIS Cut Line= 3
     3008803.932   13934970.3424    3008868.9202   13931461.3599
    3008005.3464   13929320.7995
#Sta/Elev= 30
  2610.8   168.1  2740.8   166.7  3050.8   165.2  3200.8   166.7  3230.8   165.6
  3280.8   164.5  3310.8   166.1  3500.8   164.9  3660.8   162.3  4110.8   162.7
  4400.8   160.1  4700.8   159.9  4965.1  162.09  4988.2  152.76  4991.4  148.68
  4997.1  148.58    5009  149.49  5020.8   155.8  5080.8     161  5140.8   160.2
  5470.8   163.3  6120.4   162.4  6360.4   164.5  6620.4     166  7360.4   165.1
  7690.4   165.7  7870.4   164.5  7990.4     166  8370.4     165  8428.6     166
#Mann= 12 ,-1 , 0
  2610.8    .065       0  2740.8    .045       0  3230.8    .065       0
  4400.8     .08       0  4965.1     .08       0  5080.8    .075       0
  6120.4     .05       0  6360.4     .06       0  6620.4     .05       0
  7360.4     .06       0  7870.4    .075       0  8428.6      .2       0
#XS Ineff= 2 , 0
       0                    6760       0   166.2
Permanent Ineff=
       F       F
Bank Sta=4965.1,5080.8
XS Rating Curve= 0 ,0
Exp/Cntr=0.3,0.1

Type RM Length L Ch R = 1 ,47154.7 ,531.4,809.1,540.9
BEGIN DESCRIPTION:
Cross Section XS57
END DESCRIPTION:
XS GIS Cut Line= 2
    3009742.8863    13934760.673    3009952.5557   13929300.1521
#Sta/Elev= 30
  2530.8   164.2  2690.8   164.4  2720.8   166.1  2880.8   165.3  3010.8   166.5
  3070.8   164.3  3440.8   164.7  3480.8   163.2  3560.8   164.8  3910.8   161.2
  4460.8   159.1  4630.8   160.8    4768  159.28  4965.1  160.68  4988.2  151.35
  4991.4  147.27  4997.1  147.17  5009.7  147.66  5010.8   150.3  5050.8     154
  5180.8   160.2  5330.8   162.3  5540.8   160.3  5710.8   161.4  5780.8   159.8
  6110.8   164.3  6470.8   164.1  6650.8     164  7390.8   164.6  7995.3   168.2
#Mann= 8 ,-1 , 0
  2530.8    .065       0  3440.8     .07       0  4965.1     .08       0
  5180.8     .15       0  5780.8     .04       0  6470.8     .15       0
  6650.8    .065       0  7995.3      .2       0
#XS Ineff= 2 , 0
       0                    6310       0   164.8
Permanent Ineff=
       F       F
Bank Sta=4965.1,5180.8
XS Rating Curve= 0 ,0
Exp/Cntr=0.3,0.1

Type RM Length L Ch R = 1 ,46345.6 ,725.5,807.2,678.3
BEGIN DESCRIPTION:
Cross Section XS56
END DESCRIPTION:
XS GIS Cut Line= 2
    3010298.9661    13934323.102    3010453.9391   13929528.0537
#Sta/Elev= 30
  3290.4   164.3  3900.4   163.9  3920.4   164.7  3950.4     163  3990.4   164.3
  4090.4   163.7  4200.4   164.7  4620.4     162  4740.4   161.8  4919.7  159.46
  4951.4  156.27  4977.9  155.39    4989  148.56  4990.2  146.96  5001.8  146.62
  5009.9   146.9  5010.3  147.54  5010.5  149.35  5020.7  154.61  5052.5  155.57
  5060.4   158.9  5070.4   159.3  5280.4     161  5800.4   159.7  6180.4   158.7
  6640.4   163.7  6901.3  163.92  7210.4   164.8  7700.4   163.6    8088   167.9
#Mann= 8 ,-1 , 0
  3290.4    .065       0  3920.4     .08       0  4620.4    .045       0
  4919.7     .08       0  5070.4     .15       0  5800.4     .05       0
  6901.3     .08       0    8088      .2       0
#XS Ineff= 2 , 0
       0                    7205       0   164.3
Permanent Ineff=
       F       F
Bank Sta=4919.7,5070.4
XS Rating Curve= 0 ,0
Exp/Cntr=0.3,0.1

Type RM Length L Ch R = 1 ,45538.4 ,559.8,1067.8,879.4
BEGIN DESCRIPTION:
Cross Section XS55
END DESCRIPTION:
XS GIS Cut Line= 4
    3011078.8464   13935250.0639     3011028.251   13932226.4079
     3010882.394   13932007.6224    3010946.2064   13929400.4288
#Sta/Elev= 30
  1822.1   164.5  1973.2  163.33  2074.7  163.37  2352.1   163.3  2452.1     163
  2902.1   163.4  3292.1   161.6  3372.1   163.1  3612.1   162.7  4242.1   160.1
  4671.9   159.5  4896.2   158.8  4972.2  154.96    4995  146.99  5004.7  146.52
  5025.6  158.82  5122.9  157.68  5139.1   160.2  5219.1   160.7  5409.1   160.7
  5679.1   157.4  6089.1   163.6  6399.1   164.3  6429.1   162.7  6599.1   164.2
  7119.1   162.6  7179.1   163.9  7339.1   163.3  7359.1   161.9  7717.1   164.1
#Mann= 13 ,-1 , 0
  1822.1      .2       0  1973.2    .085       0  2074.7    .035       0
  2352.1    .085       0  2452.1    .045       0  2902.1    .065       0
  3612.1    .045       0  4242.1     .06       0  4671.9     .15       0
  4896.2     .08       0  5025.6     .12       0  5219.1     .05       0
  7717.1      .2       0
#XS Ineff= 2 , 0
       0    2945   163.6    6400       0   164.3
Permanent Ineff=
       F       F
Bank Sta=4896.2,5025.6
XS Rating Curve= 0 ,0
Exp/Cntr=0.3,0.1

Type RM Length L Ch R = 1 ,44470.6 ,714.9,1326.3,674.2
BEGIN DESCRIPTION:
Cross Section XS53
END DESCRIPTION:
XS GIS Cut Line= 2
    3011467.5844   13935398.4911    3011706.5954   13929596.8923
#Sta/Elev= 30
  1524.5   164.9  2004.5   162.4  2294.5   162.1  2824.5   161.7  3174.5   160.3
  3214.5   161.6  3234.5   159.7  3354.5   161.4  3384.5     160  3764.5     159
  4094.5   160.5  4274.5   158.9  4344.5   160.2  4614.5   159.5  4764.5     161
  4904.5   158.7  4972.2  154.17    4995   146.2  5004.7  145.73  5025.6  158.03
  5122.9  156.89  5304.5   159.1  5714.5   158.3  5924.5   162.7  6164.5   160.8
  6194.5   161.7  6224.5   160.2  6734.5   161.1  6944.5   161.8    7331     166
#Mann= 9 ,-1 , 0
  1524.5    .075       0  2004.5     .05       0  2294.5    .045       0
  2824.5     .07       0  4614.5     .15       0  4904.5     .08       0
  5025.6     .15       0  5714.5     .05       0    7331      .2       0
#XS Ineff= 2 , 0
       0    2185   163.2    5925       0   162.7
Permanent Ineff=
       F       F
Bank Sta=4904.5,5025.6
XS Rating Curve= 0 ,0
Exp/Cntr=0.3,0.1

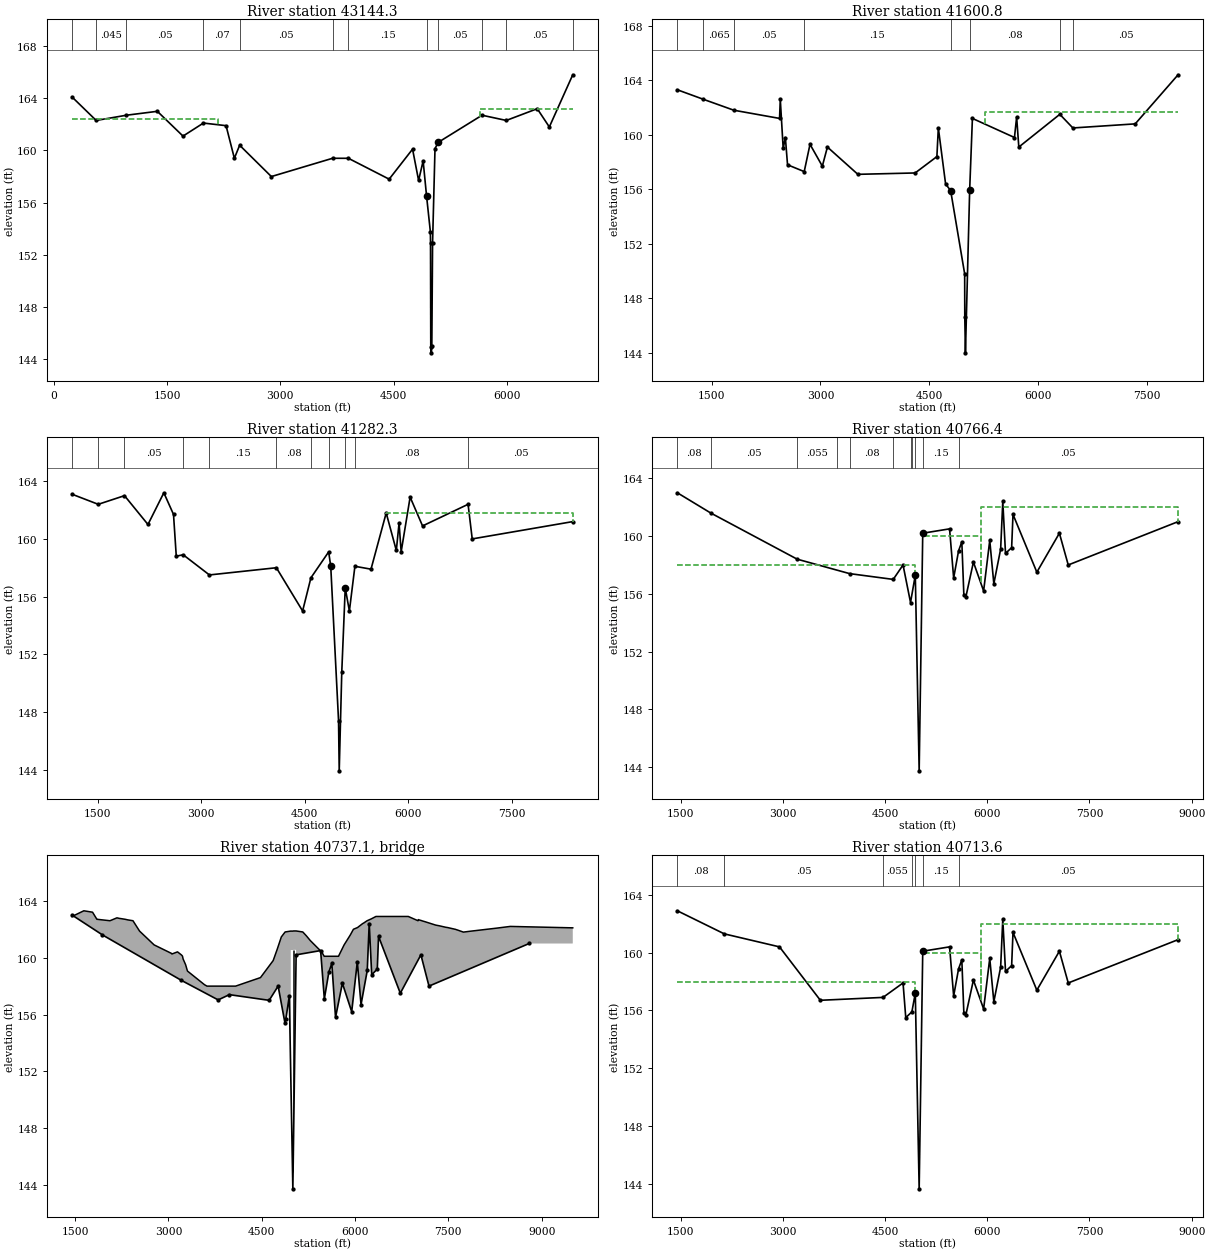
Type RM Length L Ch R = 1 ,43144.3 ,827.8,1543.5,821.8
BEGIN DESCRIPTION:
Cross Section XS52
END DESCRIPTION:
XS GIS Cut Line= 3
    3012245.0603   13935893.2485     3012295.008    13930272.246
     3011908.893    13929338.665
#Sta/Elev= 30
   242.1   164.1   562.1   162.3   962.1   162.7  1372.1     163  1712.1   161.1
  1982.1   162.1  2282.1   161.9  2392.1   159.4  2462.1   160.4  2882.1     158
  3692.1   159.4  3902.1   159.4  4442.1   157.8  4752.1   160.1  4832.1   157.7
  4892.1   159.2  4937.8  156.49  4987.9  153.77  4989.9  152.91  4993.3  144.92
  5000.9  144.49    5007  144.99  5017.1  152.93  5049.2  160.14  5091.5  160.62
  5672.1   162.7  5993.3   162.3  6403.3   163.2  6563.3   161.8  6873.6   165.8
#Mann= 12 ,-1 , 0
   242.1     .07       0   562.1    .045       0   962.1     .05       0
  1982.1     .07       0  2462.1     .05       0  3692.1     .07       0
  3902.1     .15       0  4937.8     .08       0  5091.5     .05       0
  5672.1    .065       0  5993.3     .05       0  6873.6      .2       0
#XS Ineff= 2 , 0
       0    2182   162.4    5640       0   163.2
Permanent Ineff=
       F       F
Bank Sta=4937.8,5091.5
XS Rating Curve= 0 ,0
Exp/Cntr=0.3,0.1

Type RM Length L Ch R = 1 ,41600.8 ,223.6,318.5,298.9
BEGIN DESCRIPTION:
Cross Section XS51
END DESCRIPTION:
XS GIS Cut Line= 3
    3012988.2042    13935216.476     3013096.032    13930272.122
     3012204.023    13928525.551
#Sta/Elev= 30
  1025.5   163.3  1385.6   162.6  1805.6   161.8  2435.6   161.2  2445.6   162.6
  2485.6     159  2515.6   159.8  2545.6   157.8  2775.6   157.3  2855.6   159.3
  3025.6   157.7  3095.6   159.1  3515.6   157.1  4305.6   157.2  4605.6   158.4
  4625.6   160.5  4725.6   156.4  4795.6   155.9  4988.8   149.8  4990.4  146.64
  4999.4  144.01 5057.82  155.96  5095.6   161.2  5675.6   159.8  5705.6   161.3
  5735.6   159.1  6301.1   161.5  6481.1   160.5  7341.1   160.8  7932.3   164.4
#Mann= 8 ,-1 , 0
  1025.5    .075       0  1385.6    .065       0  1805.6     .05       0
  2775.6     .15       0  4795.6     .08       0 5057.82     .08       0
  6301.1    .065       0  6481.1     .05       0
#XS Ineff= 2 , 0
       0    2450     162    5267       0   161.7
Permanent Ineff=
       F       F
Bank Sta=4795.6,5057.82
XS Rating Curve= 0 ,0
Exp/Cntr=0.3,0.1

Type RM Length L Ch R = 1 ,41282.3 ,410.9,515.9,170.9
BEGIN DESCRIPTION:
Cross Section Cypress-Rosehill-US_Con
END DESCRIPTION:
XS GIS Cut Line= 6
      3013131.38   13935264.5037     3013247.702   13931799.0501
     3013373.364   13931158.0862    3013308.8632   13930595.1706
    3013311.8998   13930145.7535    3013326.1983    13928029.635
#Sta/Elev= 30
  1129.2   163.1  1509.2   162.4  1889.2     163  2229.2     161  2459.2   163.2
  2599.2   161.7  2639.2   158.8  2739.2   158.9  3119.2   157.5  4089.2     158
  4469.2     155  4589.2   157.3  4846.6   159.1  4876.6   158.1  4989.6   147.4
  4999.4  143.91  5036.6   150.8  5086.6   156.6  5146.6     155  5226.6   158.1
  5459.8   157.9  5679.8   161.8  5826.4   159.2  5866.4   161.1  5896.4   159.1
  6026.4   162.9  6206.4   160.9  6865.8   162.4  6925.8     160    8382   161.2
#Mann= 11 ,-1 , 0
  1129.2     .07       0  1509.2    .065       0  1889.2     .05       0
  2739.2     .15       0  3119.2     .15       0  4089.2     .08       0
  4589.2     .15       0  4846.6     .08       0  5086.6     .15       0
  5226.6     .08       0  6865.8     .05       0
#XS Ineff= 2 , 0
       0    2460   162.9    5684       0   161.8
Permanent Ineff=
       F       F
Bank Sta=4876.6,5086.6
XS Rating Curve= 0 ,0
Exp/Cntr=0.5,0.3

Type RM Length L Ch R = 1 ,40766.4 ,52.8,52.8,52.8
BEGIN DESCRIPTION:
Upstream Section of Bridge/Culvert/Weir
END DESCRIPTION:
XS GIS Cut Line= 6
    3013429.2611   13935323.0295    3013558.7673   13932131.6264
    3013547.0402   13931773.9495    3013519.5204   13931570.6389
    3013419.6269   13930554.0763    3013485.8312   13927981.3829
#Sta/Elev= 30
  1448.7     163  1938.7   161.6  3208.8   158.4  3978.7   157.4  4618.7     157
  4762.7     158  4872.7   155.4  4942.6   157.3  4942.7   157.3  4999.4  143.74
    5052   160.2  5445.8   160.5  5505.8   157.1  5578.1  158.98  5625.8   159.6
  5655.8   155.9  5685.8   155.8  5795.8   158.2  5945.8   156.2  6035.8   159.7
  6095.8   156.7  6195.8   159.1  6227.2   162.4  6267.2   158.8  6357.2   159.2
  6377.2   161.5  6727.2   157.5  7058.3   160.2  7188.3     158  8800.8     161
#Mann= 11 ,-1 , 0
  1448.7     .08       0  1938.7     .05       0  3208.8    .055       0
  3798.8     .15       0  3978.7     .08       0  4618.7     .14       0
  4872.7     .05       0    4888     .12       0  4942.7     .08       0
    5052     .15       0  5578.1     .05       0
#XS Ineff= 3 ,-1
  1448.7    4940     158    5076    5900     160    5900  8800.8     162
Permanent Ineff=
       F       F       F
Bank Sta=4942.6,5052
XS Rating Curve= 0 ,0
Exp/Cntr=0.5,0.3

Type RM Length L Ch R = 3 ,40737.1 ,,,
BEGIN DESCRIPTION:
CYPRESS-ROSE HILL
Structure ID: L100-00-00-S4
END DESCRIPTION:
Bridge Culvert--1,0,-1,-1, 0
Deck Dist Width WeirC Skew NumUp NumDn MinLoCord MaxHiCord MaxSubmerge Is_Ogee
10,27,3,0, 198, 198, , , 0.95, 0, 1,1,,
  1448.8  1638.8  1778.8    1825  1848.8    1855    1915    2035  2058.8    2118
  2168.8    2175    2215    2235    2305    2345    2415  2428.8    2515  2528.8
    2535    2695  2768.8    2815  3048.8    3055    3145  3188.8    3205  3208.8
    3225    3235    3275    3305    3345    3435    3565  3578.8  3618.8    3775
    3955    4075  4078.8    4105    4195    4305    4435  4443.3  4478.8    4555
    4625  4642.6  4662.6  4683.4  4732.6  4749.1  4749.2    4814  4875.1    4888
  4894.3  4922.4  4940.9    4962  4962.6  4965.2 4965.31  4965.4  4965.5  4965.6
  4989.6  4990.4  4994.3  4999.4  5009.9  5010.5    5023  5051.4 5051.49  5051.6
  5051.7  5051.8    5052  5052.5  5096.6  5158.5    5159  5216.4  5267.9    5268
    5279    5309    5369    5419  5463.4    5489  5503.4    5519    5529  5533.4
    5539    5559  5578.1    5579    5609    5619    5629    5639    5649    5659
    5699    5729  5733.4    5749    5809    5819  5823.4    5849    5889  5923.4
    5959  5973.4    6019    6029  6033.4    6039    6059    6119  6123.4    6139
    6159    6179  6180.5  6190.5  6193.4  6220.5  6245.3  6260.5  6310.5  6330.5
  6335.3  6390.5  6400.5  6410.5  6420.5  6430.5  6480.5  6540.5  6660.5  6700.5
  6720.5  6800.5  6855.3  6860.5  7010.5  7011.9  7017.2  7027.2  7048.3  7058.3
  7068.3  7078.3  7118.3  7188.3  7218.3  7268.3  7291.5  7298.3  7328.3  7338.3
  7348.3  7358.3  7388.3  7398.3  7458.3  7488.3  7548.3  7578.3  7598.3  7611.5
  7618.3  7628.3  7638.3  7688.3  7718.3  7741.5  7758.3  7808.3  7848.3  7988.3
  8068.3  8138.3  8238.3  8278.3  8418.3  8468.3    8495    9500
   162.9   163.3   163.2  162.87   162.7   162.7  162.67  162.61   162.6  162.71
   162.8   162.8  162.76  162.75   162.7  162.66  162.61   162.6     162   161.9
  161.87  161.21   160.9   160.8   160.3  160.26  160.41  160.26  160.21  160.19
  160.11  159.91  159.51  159.06  158.92  158.61  158.15   158.1     158     158
     158     158     158  158.04  158.17  158.34  158.53  158.55   158.6  159.05
  159.46  159.56  159.68   159.8  160.41  160.61  160.61  161.46  161.81  161.82
  161.83  161.85  161.86  161.87  161.87  161.87  161.87  161.87  161.87  161.87
  161.87  161.87  161.87  161.87  161.88  161.88  161.88  161.88  161.88  161.88
  161.88  161.88  161.88  161.88  161.85  161.81  161.81  161.54  161.26  161.26
  161.21  161.08  160.82   160.6   160.4  160.21   160.1   160.1   160.1   160.1
   160.1   160.1   160.1   160.1   160.1   160.1   160.1   160.1   160.1   160.1
   160.1   160.1   160.1  160.24  160.77  160.86   160.9  161.08  161.36   161.6
  161.88     162  162.08  162.09   162.1  162.12  162.19  162.39   162.4  162.44
   162.5  162.56  162.56  162.59   162.6  162.65   162.7  162.73  162.84  162.89
   162.9   162.9   162.9   162.9   162.9   162.9   162.9   162.9   162.9   162.9
   162.9   162.9   162.9  162.89   162.6   162.6  162.68  162.66  162.63  162.62
  162.61  162.59  162.54  162.44   162.4  162.33   162.3  162.29  162.27  162.26
  162.25  162.24  162.21   162.2  162.14  162.12  162.06  162.03  162.01     162
  161.99  161.97  161.96  161.88  161.84   161.8  161.81  161.84  161.86  161.93
  161.97  162.01  162.06  162.08  162.16  162.19   162.2   162.1
                                                                                
                                                                                
                                                                                
                                                                                
                                                                                
                                                                                
                                                                  160.54  160.54
  160.54  160.54  160.54  160.54  160.55  160.55  160.55  160.55  160.55
                                                                                
                                                                                
                                                                                
                                                                                
                                                                                
                                                                                
                                                                                
                                                                                
                                                                                
                                                                                
                                                                                
                                                                
  1448.8  1638.8  1778.8    1825  1848.8    1855    1915    2035  2058.8    2118
  2168.8    2175    2215    2235    2305    2345    2415  2428.8    2515  2528.8
    2535    2695  2768.8    2815  3048.8    3055    3145  3188.8    3205  3208.8
    3225    3235    3275    3305    3345    3435    3565  3578.8  3618.8    3775
    3955    4075  4078.8    4105    4195    4305    4435  4443.3  4478.8    4555
    4625  4642.6  4662.6  4683.4  4732.6  4749.1  4749.2    4814  4875.1    4888
  4894.3  4922.4  4940.9    4962  4962.6  4965.2 4965.31  4965.4  4965.5  4965.6
  4989.6  4990.4  4994.3  4999.4  5009.9  5010.5    5023  5051.4 5051.49  5051.6
  5051.7  5051.8    5052  5052.5  5096.6  5158.5    5159  5216.4  5267.9    5268
    5279    5309    5369    5419  5463.4    5489  5503.4    5519    5529  5533.4
    5539    5559  5578.1    5579    5609    5619    5629    5639    5649    5659
    5699    5729  5733.4    5749    5809    5819  5823.4    5849    5889  5923.4
    5959  5973.4    6019    6029  6033.4    6039    6059    6119  6123.4    6139
    6159    6179  6180.5  6190.5  6193.4  6220.5  6245.3  6260.5  6310.5  6330.5
  6335.3  6390.5  6400.5  6410.5  6420.5  6430.5  6480.5  6540.5  6660.5  6700.5
  6720.5  6800.5  6855.3  6860.5  7010.5  7011.9  7017.2  7027.2  7048.3  7058.3
  7068.3  7078.3  7118.3  7188.3  7218.3  7268.3  7291.5  7298.3  7328.3  7338.3
  7348.3  7358.3  7388.3  7398.3  7458.3  7488.3  7548.3  7578.3  7598.3  7611.5
  7618.3  7628.3  7638.3  7688.3  7718.3  7741.5  7758.3  7808.3  7848.3  7988.3
  8068.3  8138.3  8238.3  8278.3  8418.3  8468.3    8495    9500
   162.9   163.3   163.2  162.87   162.7   162.7  162.67  162.61   162.6  162.71
   162.8   162.8  162.76  162.75   162.7  162.66  162.61   162.6     162   161.9
  161.87  161.21   160.9   160.8   160.3  160.26  160.41  160.26  160.21  160.19
  160.11  159.91  159.51  159.06  158.92  158.61  158.15   158.1     158     158
     158     158     158  158.04  158.17  158.34  158.53  158.55   158.6  159.05
  159.46  159.56  159.68   159.8  160.41  160.61  160.61  161.46  161.81  161.82
  161.83  161.85  161.86  161.87  161.87  161.87  161.87  161.87  161.87  161.87
  161.87  161.87  161.87  161.87  161.88  161.88  161.88  161.88  161.88  161.88
  161.88  161.88  161.88  161.88  161.85  161.81  161.81  161.54  161.26  161.26
  161.21  161.08  160.82   160.6   160.4  160.21   160.1   160.1   160.1   160.1
   160.1   160.1   160.1   160.1   160.1   160.1   160.1   160.1   160.1   160.1
   160.1   160.1   160.1  160.24  160.77  160.86   160.9  161.08  161.36   161.6
  161.88     162  162.08  162.09   162.1  162.12  162.19  162.39   162.4  162.44
   162.5  162.56  162.56  162.59   162.6  162.65   162.7  162.73  162.84  162.89
   162.9   162.9   162.9   162.9   162.9   162.9   162.9   162.9   162.9   162.9
   162.9   162.9   162.9  162.89   162.6   162.6  162.68  162.66  162.63  162.62
  162.61  162.59  162.54  162.44   162.4  162.33   162.3  162.29  162.27  162.26
  162.25  162.24  162.21   162.2  162.14  162.12  162.06  162.03  162.01     162
  161.99  161.97  161.96  161.88  161.84   161.8  161.81  161.84  161.86  161.93
  161.97  162.01  162.06  162.08  162.16  162.19   162.2   162.1
                                                                                
                                                                                
                                                                                
                                                                                
                                                                                
                                                                                
                                                                  160.46  160.46
  160.46  160.46  160.46  160.46  160.47  160.47  160.47  160.47  160.47
                                                                                
                                                                                
                                                                                
                                                                                
                                                                                
                                                                                
                                                                                
                                                                                
                                                                                
                                                                                
                                                                                
                                                                
Pier Skew, UpSta & Num, DnSta & Num=  ,4994.3, 2 ,4994.3, 2 , 0 , 0 , 0 ,,
       1       1
  144.13  161.54
       1       1
  144.05  161.46
Pier Skew, UpSta & Num, DnSta & Num=  ,5023, 2 ,5023, 2 , 0 , 0 , 0 ,,
       1       1
  149.83  161.55
       1       1
  149.75  161.47
BR Coef= 1 , 1 , 1 ,1.25, 0 ,,,0.8,0,2,0,
WSPro=,,,, 1 ,,,, 0 ,,,, 0 ,,,,-1 ,-1 ,-1 , 0 , 0 , 0 , 0 , 0
BR U #Sta/Elev= 30
  1448.7     163  1938.7   161.6  3208.8   158.4  3798.8  157.03  3978.7   157.4
  4618.7     157  4762.7     158  4872.7   155.4    4888  155.72  4942.6   157.3
  4999.4  143.74    5052   160.2  5445.8   160.5  5505.8   157.1  5578.1  158.98
  5625.8   159.6  5685.8   155.8  5795.8   158.2  5945.8   156.2  6035.8   159.7
  6095.8   156.7  6195.8   159.1  6227.2   162.4  6267.2   158.8  6357.2   159.2
  6377.2   161.5  6727.2   157.5  7058.3   160.2  7188.3     158  8800.8     161
BR U #Mann= 11
  1448.7     .08  1938.7     .05  3208.8    .055  3798.8     .15  3978.7     .08
  4618.7     .14  4872.7     .05    4888     .12  4942.6    .075    5052     .15
  5578.1     .05
BR D #Sta/Elev= 30
  1448.7   162.9    2118   161.2  2948.7   160.4  3548.7   156.7  4443.3  157.21
  4762.7   157.9  4802.7   155.5    4888  155.62  4942.6   157.2  4999.4  143.64
    5052   160.1  5445.8   160.4  5505.8     157  5578.1  158.88  5625.8   159.5
  5655.8   155.8  5795.8   158.1  5945.8   156.1  6035.8   159.6  6095.8   156.6
  6195.8     159  6227.2   162.3  6267.2   158.7  6357.2   159.1  6377.2   161.4
  6727.2   157.4  7058.3   160.1  7188.3   157.9  8707.7   160.9  9150.8   158.9
BR D #Mann= 7
  1448.7     .08    2118     .05  4443.3    .055    4888     .15  4942.6    .075
    5052     .15  5578.1     .05
BC Design=,, 0 ,, 0 ,,,,,,
BC HTab HWMax=164
BC Use User HTab Curves=0
BC User HTab FreeFlow(D)= 0

Type RM Length L Ch R = 1 ,40713.6 ,268.9,304.7,369.5
BEGIN DESCRIPTION:
Downstream Section of Bridge/Culvert/Weir
END DESCRIPTION:
XS GIS Cut Line= 5
    3013516.6042   13935304.9395    3013635.0682   13932133.7492
    3013470.9791   13930520.2064    3013508.2852   13929736.7772
    3013591.1655   13927996.2834
#Sta/Elev= 30
  1448.7   162.9  2138.7   161.3  2948.7   160.4  3548.7   156.7  4468.7   156.9
  4762.7   157.9  4802.7   155.5  4892.7   155.9  4942.6   157.2  4999.4  143.64
    5052   160.1  5445.8   160.4  5505.8     157  5578.1  158.88  5625.8   159.5
  5655.8   155.8  5685.8   155.7  5795.8   158.1  5945.8   156.1  6035.8   159.6
  6095.8   156.6  6195.8     159  6227.2   162.3  6267.2   158.7  6357.2   159.1
  6377.2   161.4  6727.2   157.4  7058.3   160.1  7188.3   157.9  8800.8   160.9
#Mann= 7 ,-1 , 0
  1448.7     .08       0  2138.7     .05       0  4468.7    .055       0
  4892.7     .15       0  4942.6     .08       0    5052     .15       0
  5578.1     .05       0
#XS Ineff= 3 ,-1
  1448.7    4940     158    5076    5900     160    5900  8800.8     162
Permanent Ineff=
       F       F       F
Bank Sta=4942.6,5052
XS Rating Curve= 0 ,0
Exp/Cntr=0.5,0.3