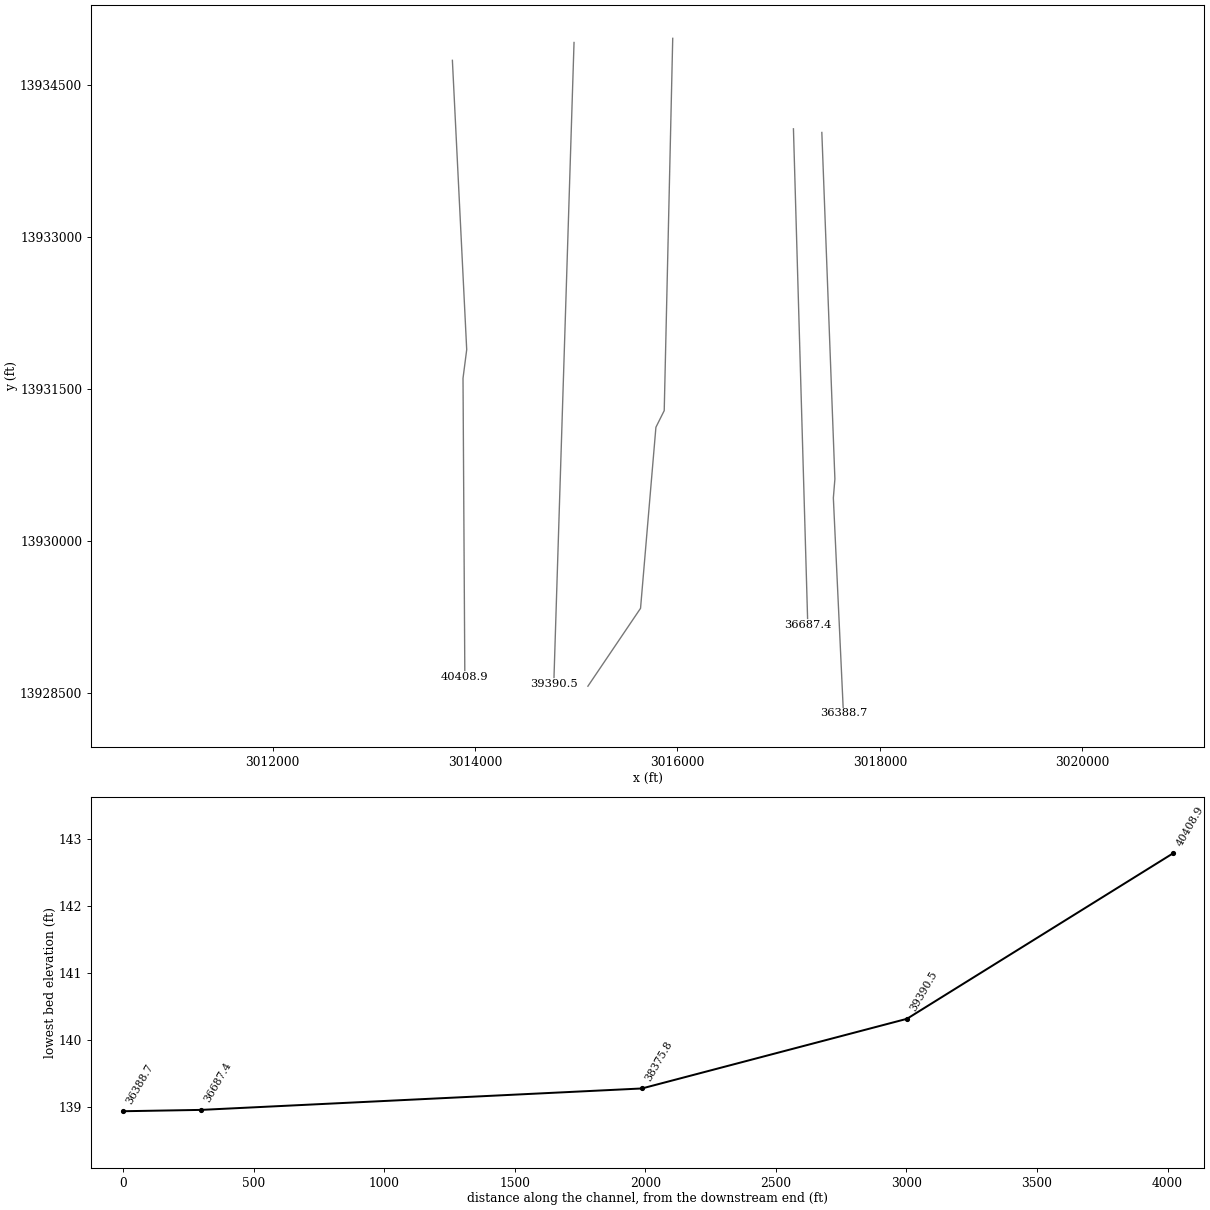
HEC-RAS study L100-00-00.prj: L100-00-00

--- L100-00-00.g01 (geometry) --- (continued)

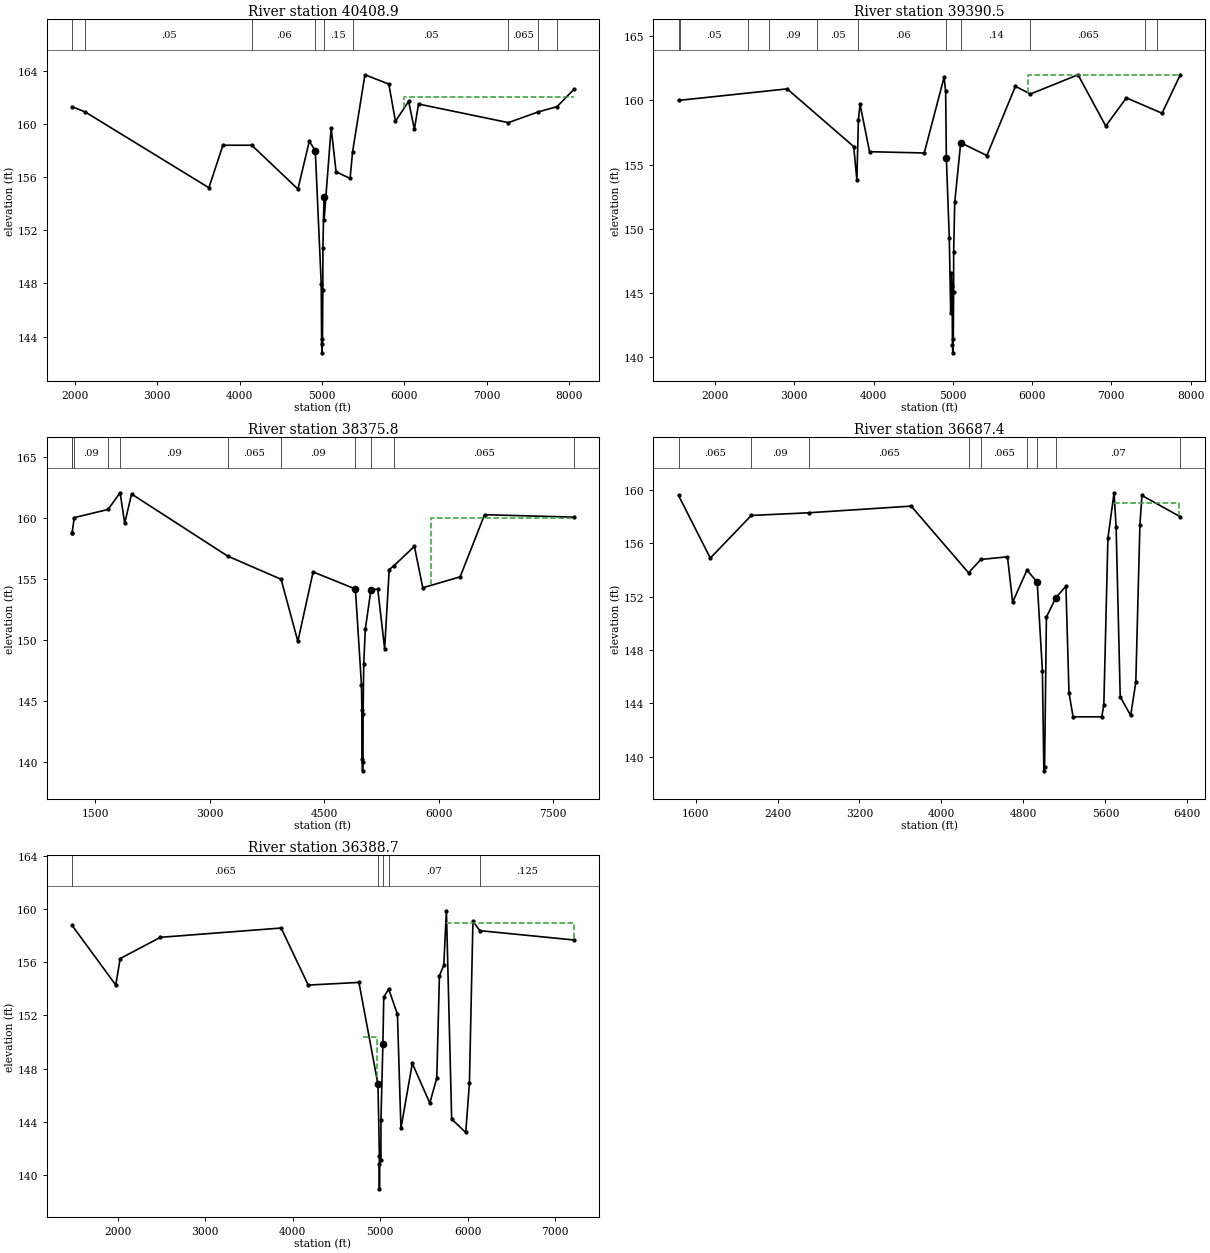
Type RM Length L Ch R = 1 ,40408.9 ,1088.9,1018.4,1018.4
BEGIN DESCRIPTION:
Cross Section XS50
END DESCRIPTION:
XS GIS Cut Line= 5
    3013776.6382   13934743.7117    3013918.0425   13931889.1136
    3013881.5782   13931606.5157    3013888.2649   13930516.5902
     3013899.643    13928661.914
#Sta/Elev= 30
  1967.5   161.3  2127.5   160.9  3627.5   155.2  3797.5   158.4  4147.5   158.4
  4707.5   155.1  4845.6   158.7  4918.2  157.99  4990.2  147.96  4995.1  143.42
  4999.6  142.78  5005.5  143.84  5009.8  147.49  5010.4  150.68  5023.8  154.52
  5025.6   152.8  5110.5   159.7  5170.5   156.4  5340.5   155.9  5370.5   157.9
  5520.5   163.7  5810.5     163  5890.5   160.2  6050.5   161.7  6120.5   159.6
  6170.5   161.5  7260.5   160.1  7620.5   160.9  7850.5   161.3  8055.2   162.6
#Mann= 9 ,-1 , 0
  1967.5     .08       0  2127.5     .05       0  4147.5     .06       0
  4918.2     .08       0  5023.8     .15       0  5370.5     .05       0
  7260.5    .065       0  7620.5     .05       0  7850.5     .07       0
#XS Ineff= 2 , 0
       0                    6000       0     162
Permanent Ineff=
       F       F
Bank Sta=4918.2,5023.8
XS Rating Curve= 0 ,0
Exp/Cntr=0.3,0.1

Type RM Length L Ch R = 1 ,39390.5 ,1041.6,1014.7,1014.7
BEGIN DESCRIPTION:
Cross Section XS49
END DESCRIPTION:
XS GIS Cut Line= 3
    3014978.0796   13934919.8083    3014783.4152   13928757.9288
     3014778.181     13928592.25
#Sta/Elev= 30
  1539.3     160  2909.3   160.9  3749.3   156.4  3789.3   153.8  3808.5  158.48
  3829.3   159.7  3949.3     156  4639.3   155.9  4889.3   161.8  4909.3   160.7
  4918.2  155.52  4955.2  149.26  4973.3   143.4  4981.6  146.52  4990.2  145.49
  4995.1  140.95  4999.6  140.31  5005.5  141.37  5009.8  145.02  5010.4  148.21
  5023.8  152.05  5099.3   156.7  5429.3   155.7  5789.3   161.1  5979.3   160.5
  6579.3     162  6929.3     158  7189.3   160.2  7639.3     159    7870     162
#Mann= 11 ,-1 , 0
  1539.3    .045       0  1555.5     .05       0  2415.8     .05       0
  2681.2     .09       0  3286.2     .05       0  3808.5     .06       0
  4918.2     .08       0  5099.3     .14       0  5979.3    .065       0
  7430.3     .05       0  7575.7    .065       0
#XS Ineff= 2 , 0
       0                    5950       0     162
Permanent Ineff=
       F       F
Bank Sta=4918.2,5099.3
XS Rating Curve= 0 ,0
Exp/Cntr=0.3,0.1

Type RM Length L Ch R = 1 ,38375.8 ,1510.6,1688.4,1609.1
BEGIN DESCRIPTION:
Cross Section XS48
END DESCRIPTION:
XS GIS Cut Line= 5
    3015952.8698   13934960.7086    3015868.8796   13931287.4535
    3015786.8351   13931123.3644    3015634.9547   13929336.7972
    3015115.1576   13928568.4086
#Sta/Elev= 30
    1193   158.8  1193.1   158.8  1221.6  160.06  1664.9  160.73  1823.1   162.1
  1883.1   159.6  1973.1     162  3233.1   156.9  3933.1     155  4153.1   149.9
  4353.1   155.6  4907.3   154.2  4987.3   146.3  4991.8  144.27  4993.4  140.23
  5001.4  139.27  5007.1  139.99  5008.3   143.9  5016.9  148.04  5037.3   150.9
  5110.8   154.1  5200.8   154.2  5290.8   149.3  5350.8   155.8  5410.8   156.1
  5680.8   157.7  5790.8   154.3  6280.8   155.2  6600.8   160.3  7771.5   160.1
#Mann= 11 ,-1 , 0
    1193      .2       0  1193.1    .095       0  1221.6     .09       0
  1664.9    .065       0  1823.1     .09       0  3233.1    .065       0
  3933.1     .09       0  4907.3     .08       0  5110.8     .14       0
  5410.8    .065       0  7771.5      .2       0
#XS Ineff= 2 , 0
       0    2750            5900       0     160
Permanent Ineff=
       F       F
Bank Sta=4907.3,5110.8
XS Rating Curve= 0 ,0
Exp/Cntr=0.3,0.1

Type RM Length L Ch R = 1 ,36687.4 ,307,298.7,298.7
BEGIN DESCRIPTION:
Cross Section XS47
END DESCRIPTION:
XS GIS Cut Line= 3
    3017145.1282   13934067.8523    3017271.8165   13929687.5816
     3017286.688    13929173.382
#Sta/Elev= 30
  1434.2   159.6  1744.2   154.9  2144.2   158.1  2704.2   158.3  3704.2   158.8
  4264.2   153.8  4384.2   154.8  4644.2     155  4694.2   151.6  4834.2     154
  4934.2   153.1  4984.7  146.47  4998.9  138.95  5006.3  139.22  5023.9  150.48
  5114.2   151.9  5214.2   152.8  5244.2   144.8  5284.2     143  5564.2     143
  5584.2   143.9  5624.2   156.4  5684.2   159.8  5704.2   157.2  5744.2   144.5
  5846.3   143.1  5896.3   145.6  5936.3   157.4  5956.3   159.6  6330.7     158
#Mann= 9 ,-1 , 0
  1434.2    .065       0  2144.2     .09       0  2704.2    .065       0
  4264.2     .09       0  4384.2    .065       0  4834.2     .14       0
  4934.2     .08       0  5114.2     .07       0  6330.7      .2       0
#XS Ineff= 2 ,-1
  1434.2    2000            5684    6316     159
Permanent Ineff=
       F       F
Bank Sta=4934.2,5114.2
XS Rating Curve= 0 ,0
Exp/Cntr=0.5,0.3

Type RM Length L Ch R = 1 ,36388.7 ,36,36,36
BEGIN DESCRIPTION:
Upstream Section of Bridge/Culvert/Weir
END DESCRIPTION:
XS GIS Cut Line= 5
    3017425.5486   13934031.9118    3017554.5367   13930613.1507
    3017539.3275   13930425.5709    3017577.8681   13929602.8379
      3017638.89    13928300.193
#Sta/Elev= 30
    1477  158.79    1977  154.29    2027  156.29    2487  157.89    3867  158.59
    4177  154.29    4757  154.49 4974.61   146.8  4990.6  141.42  4991.1  138.93
  4991.5  140.83  5008.4   141.1  5008.6  144.12  5030.7  149.82  5040.6  153.38
    5097  153.99    5197  152.09    5237  143.49    5367  148.39    5567  145.39
    5647  147.29    5677  154.99    5727  155.79    5757  159.89    5817  144.19
    5978  143.18    6020  146.89    6060  159.09    6140  158.39  7214.1  157.69
#Mann= 5 ,-1 , 0
    1477    .065       0 4974.61     .08       0  5030.7     .14       0
    5097     .07       0    6140    .125       0
#XS Ineff= 4 ,-1
    1477    3860            4800    4965   150.4    5042    5755   143.5
    5755    7250     159
Permanent Ineff=
       F       F       F       F
Bank Sta=4974.61,5030.7
XS Rating Curve= 0 ,0
Exp/Cntr=0.5,0.3