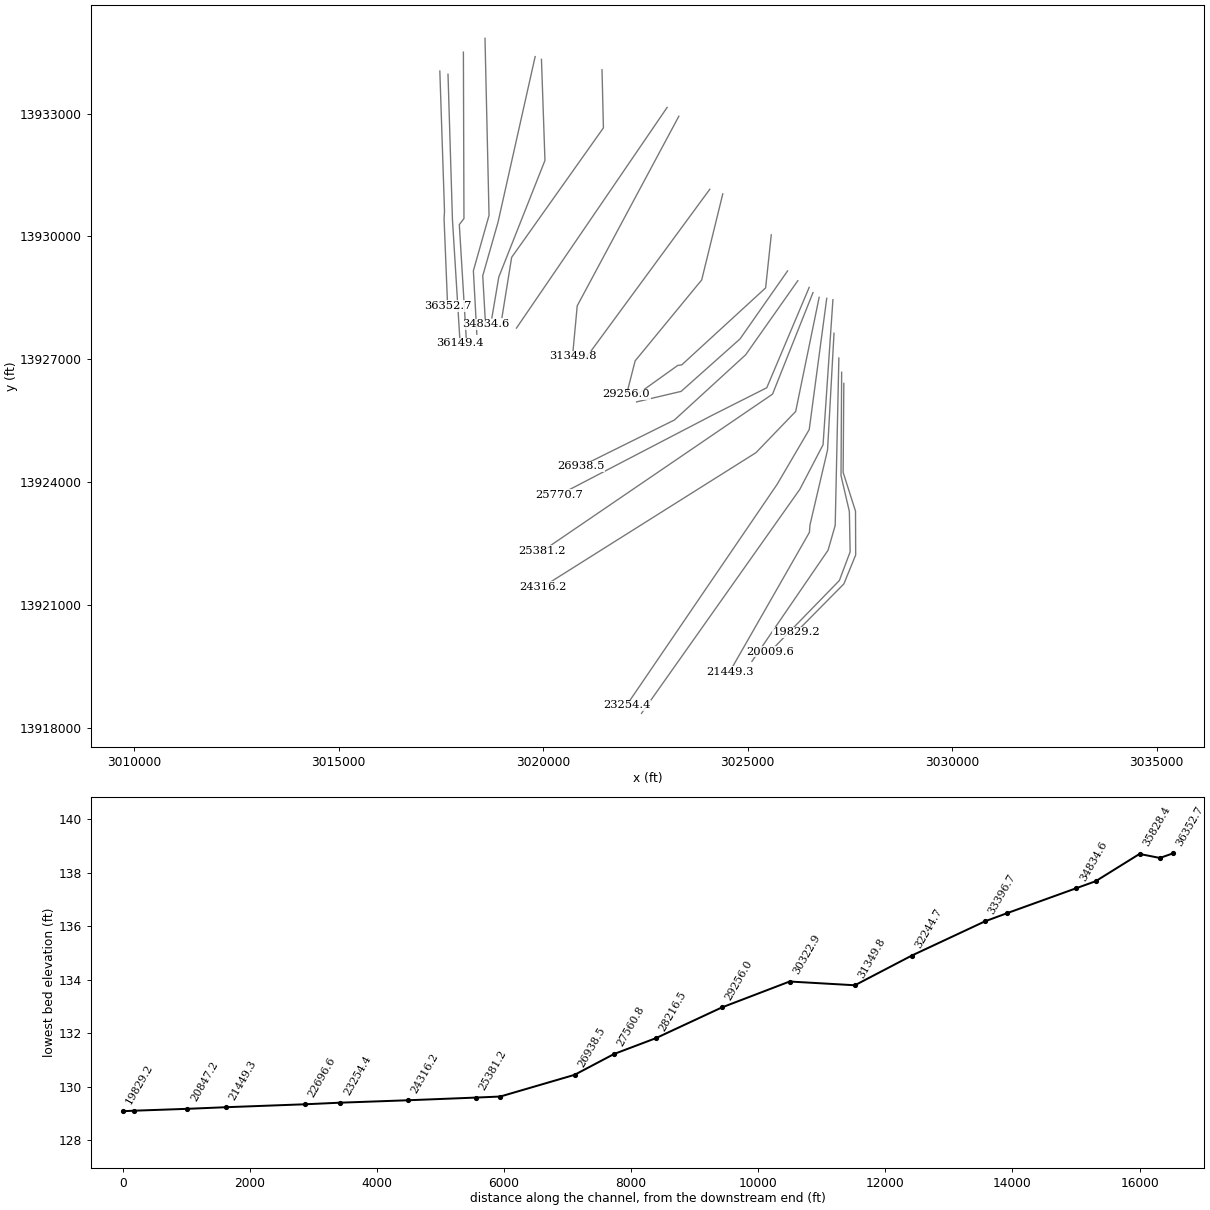
HEC-RAS study L100-00-00.prj: L100-00-00

--- L100-00-00.g01 (geometry) --- (continued)

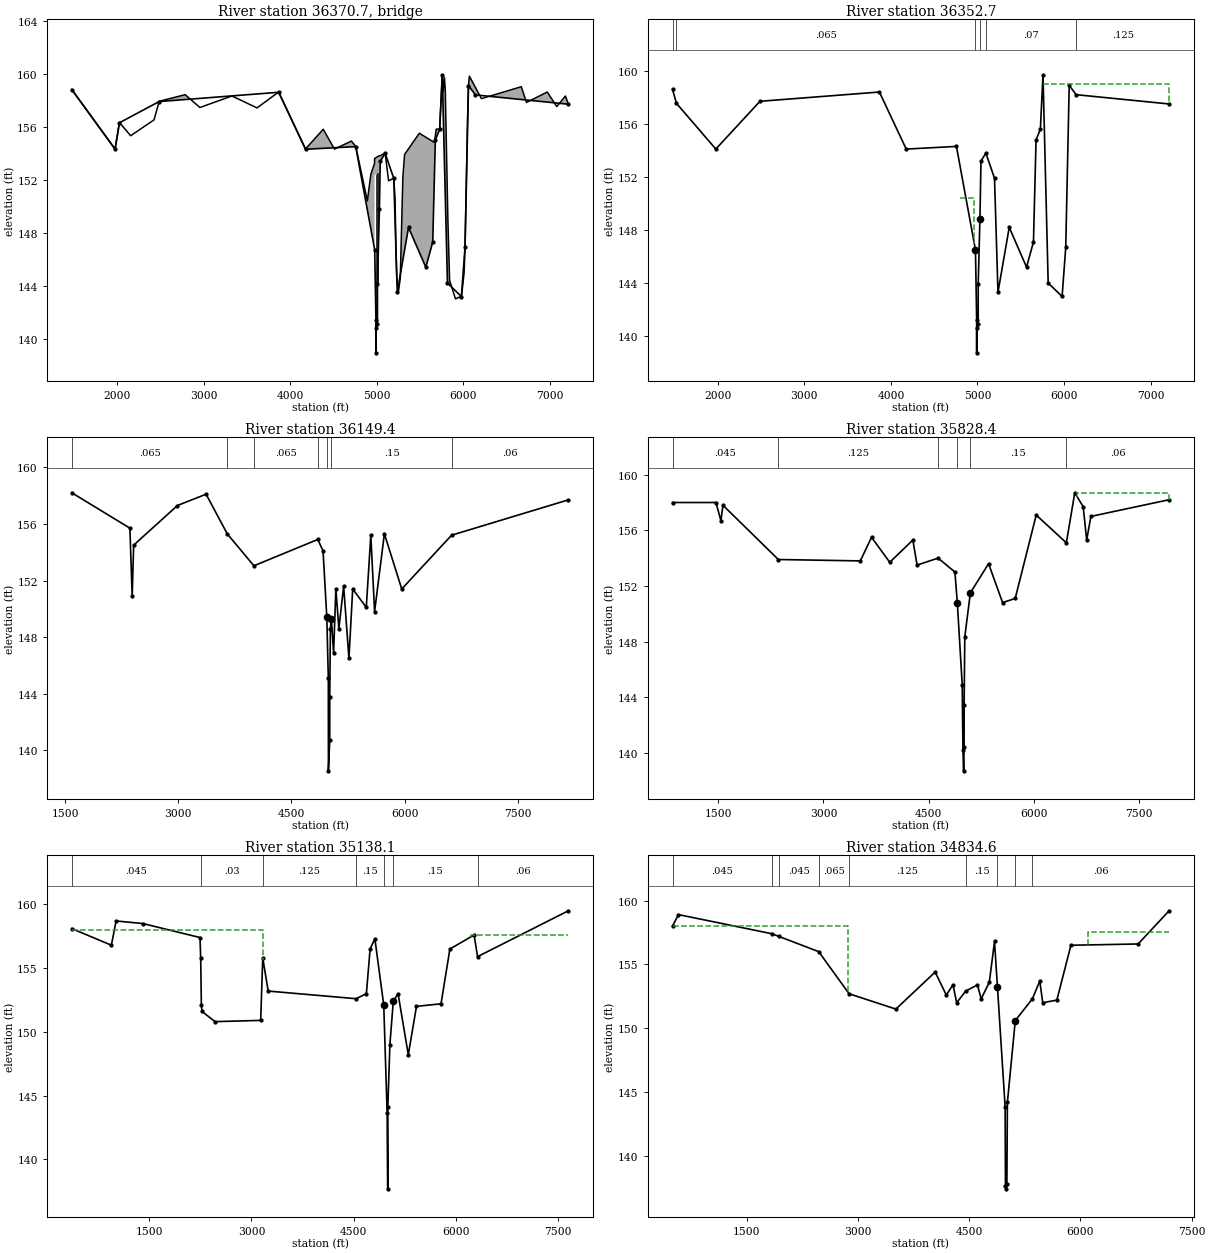
Type RM Length L Ch R = 3 ,36370.7 ,,,
BEGIN DESCRIPTION:
PRIVATE ROAD
Structure ID: L100-00-00-S22
END DESCRIPTION:
Bridge Culvert--1,0,-1,-1, 0
Deck Dist Width WeirC Skew NumUp NumDn MinLoCord MaxHiCord MaxSubmerge Is_Ogee
10,16,2.6,0, 60, 60, , , 0.95, 0, 1,1,,
    1477    1977    2027    2157    2427    2487    2787    2957    3327    3617
    3867    4177  4381.9  4511.9    4707    4757  4891.9  4931.9 4974.61  4974.7
  4974.8  4974.9  5028.2 5030.59 5030.71  5040.6    5097    5137    5197  5211.9
  5221.9  5231.9  5251.9  5271.9  5301.9  5321.9  5491.9    5667    5687    5727
    5757    5767  5781.9  5791.9  5821.9  5841.9    5910    5980    6010    6020
    6050    6060    6070    6210    6670    6730    6970    7080    7180  7214.1
   158.8  154.31  156.31  155.31  156.51  157.91  158.41  157.44  158.31  157.41
  158.61  154.31   155.8   154.3  154.91  154.51   150.4   152.4  153.22  153.34
  153.46  153.59   153.8   153.8   153.8   153.8  154.01  151.91  152.11   150.5
   146.7  144.48   143.6  144.55   152.2   153.9   155.5   154.8  155.81  155.81
  159.91  158.61   159.7   158.8     149   144.4     143  143.21  145.01  146.91
  156.81  159.11  159.81  158.11  159.01  157.82  158.61  157.51  158.31   157.7
                                                                                
                                                                   146.8   146.8
   152.2  152.33  152.54  152.54  149.82
                                                                                
                                                                                
                                                                                
    1477    1977    2027    2157    2427    2487    2787    2957    3327    3617
    3867    4177  4381.9  4511.9    4707    4757  4891.9  4931.9 4974.61  4974.7
  4974.8  4974.9  5028.2 5030.59 5030.71  5040.6    5097    5137    5197  5211.9
  5221.9  5231.9  5251.9  5271.9  5301.9  5321.9  5491.9    5667    5687    5727
    5757    5767  5781.9  5791.9  5821.9  5841.9    5910    5980    6010    6020
    6050    6060    6070    6210    6670    6730    6970    7080    7180  7214.1
   158.8  154.31  156.31  155.31  156.51  157.91  158.41  157.44  158.31  157.41
  158.61  154.31   155.8   154.3  154.91  154.51   150.4   152.4  153.22  153.34
  153.46  153.59   153.8   153.8   153.8   153.8  154.01  151.91  152.11   150.5
   146.7  144.48   143.6  144.55   152.2   153.9   155.5   154.8  155.81  155.81
  159.91  158.61   159.7   158.8     149   144.4     143  143.21  145.01  146.91
  156.81  159.11  159.81  158.11  159.01  157.82  158.61  157.51  158.31   157.7
                                                                                
                                                                   146.6   146.6
     152  152.13  152.34  152.34  149.62
                                                                                
                                                                                
                                                                                
Pier Skew, UpSta & Num, DnSta & Num=  ,4990.6, 2 ,4990.6, 2 , 0 , 0 , 0 ,,
       1       1
  137.93  153.39
       1       1
  137.73  153.19
Pier Skew, UpSta & Num, DnSta & Num=  ,5008.6, 2 ,5008.6, 2 , 0 , 0 , 0 ,,
       1       1
  140.03  153.46
       1       1
  139.83  153.26
BR Coef= 1 , 1 , 1 ,1.25, 0 ,,,0.8,0,2,0,
WSPro=,,,, 1 ,,,, 0 ,,,, 0 ,,,,-1 ,-1 ,-1 , 0 , 0 , 0 , 0 , 0
BR U #Sta/Elev= 30
    1477  158.79    1977  154.29    2027  156.29    2487  157.89    3867  158.59
    4177  154.29    4757  154.49  4976.9  146.69  4990.6  141.42  4991.1  138.93
  4991.5  140.83  5008.4   141.1  5008.6  144.12  5030.7  149.82  5040.6  153.38
    5097  153.99    5197  152.09    5237  143.49    5367  148.39    5567  145.39
    5647  147.29    5677  154.99    5727  155.79    5757  159.89    5817  144.19
    5978  143.18    6020  146.89    6060  159.09    6140  158.39  7214.1  157.69
BR U #Mann= 5
    1477    .065  4976.9    .075  5030.7     .14    5097     .07    6140    .125
BR U Banks=4976.9,
BR D #Sta/Elev= 30
    1477  158.58    1522  157.53    1977  154.08    2487  157.68    3867  158.38
    4177  154.08    4757  154.28  4976.9  146.48  4990.6  141.21  4991.1  138.72
  4991.5  140.62  5008.4  140.89  5008.6  143.91  5028.5  148.82  5040.6  153.17
    5097  153.78    5197  151.88    5237  143.28    5367  148.18    5567  145.18
    5647  147.08    5677  154.78    5727  155.58    5757  159.68    5817  143.98
    5978  142.97    6020  146.68    6060  158.88    6140  158.18  7214.1  157.48
BR D #Mann= 6
    1477      .2    1522    .065  4976.9    .075  5028.5     .14    5097     .07
    6140    .125
BC Design=,, 0 ,, 0 ,,,,,,
BC HTab HWMax=159.89
BC Use User HTab Curves=0
BC User HTab FreeFlow(D)= 0

Type RM Length L Ch R = 1 ,36352.7 ,189.9,203.2,269
BEGIN DESCRIPTION:
Downstream Section of Bridge/Culvert/Weir
END DESCRIPTION:
XS GIS Cut Line= 5
    3017472.9353   13934039.1231     3017587.173   13930617.9563
    3017576.7167   13930426.2575    3017610.0223   13929608.9495
    3017663.3171   13928301.1129
#Sta/Elev= 30
    1477  158.58    1522  157.53    1977  154.08    2487  157.68    3867  158.38
    4177  154.08    4757  154.28  4976.9  146.48  4990.6  141.21  4991.1  138.72
  4991.5  140.62  5008.4  140.89  5008.6  143.91  5028.5  148.82  5040.6  153.17
    5097  153.78    5197  151.88    5237  143.28    5367  148.18    5567  145.18
    5647  147.08    5677  154.78    5727  155.58    5757  159.68    5817  143.98
    5978  142.97    6020  146.68    6060  158.88    6140  158.18  7214.1  157.48
#Mann= 6 ,-1 , 0
    1477      .2       0    1522    .065       0  4976.9     .08       0
  5028.5     .14       0    5097     .07       0    6140    .125       0
#XS Ineff= 4 ,-1
    1477    3900            4800    4965   150.4    5042    5755   143.5
    5755    7250     159
Permanent Ineff=
       F       F       F       F
Bank Sta=4976.9,5028.5
XS Rating Curve= 0 ,0
Exp/Cntr=0.5,0.3

Type RM Length L Ch R = 1 ,36149.4 ,302.4,321.1,235.4
BEGIN DESCRIPTION:
Cross Section XS46
END DESCRIPTION:
XS GIS Cut Line= 3
    3017672.7682    13933961.937    3017781.3854   13930410.4445
     3017968.898    13927387.521
#Sta/Elev= 30
  1589.8   158.2  2359.8   155.7  2389.8   150.9  2409.8   154.5  2989.8   157.3
  3369.8   158.1  3649.8   155.3  4003.3  153.04  4849.8   154.9  4919.8   154.1
  4969.8   149.4  4989.8   145.1  4991.1  138.55  5008.4  140.72  5008.6  143.74
  5017.5   148.6  5029.8   149.3  5059.8   146.9  5089.8   151.4  5129.8   148.6
    5193   151.6    5263   146.5    5313   151.4    5493   150.1    5553   155.2
    5603   149.8    5733   155.3    5963   151.4    6623   155.2  8171.7   157.7
#Mann= 7 ,-1 , 0
  1589.8    .065       0  3649.8    .125       0  4003.3    .065       0
  4849.8     .15       0  4969.8     .08       0  5029.8     .15       0
    6623     .06       0
#XS Ineff= 2 , 0
       0    3800                       0
Permanent Ineff=
       F       F
Bank Sta=4969.8,5029.8
XS Rating Curve= 0 ,0
Exp/Cntr=0.3,0.1

Type RM Length L Ch R = 1 ,35828.4 ,628.3,690.3,545
BEGIN DESCRIPTION:
Cross Section XS45
END DESCRIPTION:
XS GIS Cut Line= 4
    3018049.1357   13934500.8512    3018062.8467   13930436.7018
    3017949.2718   13930289.0545     3018121.827    13927458.104
#Sta/Elev= 30
   846.9     158  1466.9     158  1536.9   156.7  1566.9   157.8  2356.9   153.9
  3526.9   153.8  3686.9   155.5  3946.9   153.7  4276.9   155.3  4336.9   153.5
  4636.9     154  4876.9     153  4911.1   150.8  4981.1   144.9  4991.5  140.17
  5001.4   138.7  5008.4  140.44  5008.6  143.46  5017.5  148.32  5097.3   151.5
  5357.3   153.6  5557.3   150.8  5737.3   151.1  6037.3   157.1  6467.3   155.1
  6587.3   158.7  6707.3   157.7  6757.3   155.3  6817.3     157  7933.6   158.2
#Mann= 6 ,-1 , 0
   846.9    .045       0  2356.9    .125       0  4636.9     .15       0
  4911.1     .08       0  5097.3     .15       0  6467.3     .06       0
#XS Ineff= 2 , 0
       0    3550            6625       0   158.7
Permanent Ineff=
       F       F
Bank Sta=4911.1,5097.3
XS Rating Curve= 0 ,0
Exp/Cntr=0.3,0.1

Type RM Length L Ch R = 1 ,35138.1 ,375.6,303.5,284.6
BEGIN DESCRIPTION:
Cross Section XS44.5
END DESCRIPTION:
XS GIS Cut Line= 4
     3018577.228    13934837.871     3018676.053     13930514.26
     3018293.176     13929161.97     3018377.804    13927612.043
#Sta/Elev= 30
     366   158.1     946   156.8    1016   158.7    1406   158.5    2246   157.4
    2256   155.8    2266   152.1    2276   151.6    2466   150.8    3136   150.9
    3166   155.8    3246   153.2    4536   152.6    4686     153  4740.7   156.5
  4810.7   157.3  4940.7   152.1  4990.7   143.6  4999.3  137.68  5000.7   144.1
  5030.7     149  5080.7   152.4  5150.7     153  5300.7   148.2  5420.7     152
  5780.7   152.2  5910.7   156.5  6266.2   157.6  6316.2   155.9  7648.4   159.5
#Mann= 7 ,-1 , 0
     366    .045       0    2256     .03       0    3166    .125       0
    4536     .15       0  4940.7     .08       0  5080.7     .15       0
  6316.2     .06       0
#XS Ineff= 2 , 0
       0    3170     158    6222       0   157.6
Permanent Ineff=
       F       F
Bank Sta=4940.7,5080.7
XS Rating Curve= 0 ,0
Exp/Cntr=0.3,0.1

Type RM Length L Ch R = 1 ,34834.6 ,627.4,1096.3,852.6
BEGIN DESCRIPTION:
Cross Section XS44
END DESCRIPTION:
XS GIS Cut Line= 4
      3019803.39     13934391.87     3018894.542   13930342.8422
      3018522.13    13929039.399     3018589.561    13927853.709
#Sta/Elev= 30
   502.9     158   582.9   158.9  1842.9   157.4  1932.9   157.2  2472.9     156
  2882.9   152.7  3512.9   151.5  4042.9   154.4  4192.9   152.6  4282.9   153.4
  4332.9     152  4452.9   152.9  4612.9   153.4  4662.7   152.3  4772.7   153.6
  4842.7   156.8  4882.7   153.2  4985.9  143.84  4990.3  137.63  4999.3  137.42
  5009.3  137.78  5016.3  144.19  5122.7   150.6  5352.7   152.3  5452.7   153.7
  5492.7     152  5682.7   152.2  5872.7   156.5  6778.3   156.6  7195.9   159.2
#Mann= 9 ,-1 , 0
   502.9    .045       0  1842.9    .065       0  1932.9    .045       0
  2472.9    .065       0  2882.9    .125       0  4452.9     .15       0
  4882.7     .08       0  5122.7     .15       0  5352.7     .06       0
#XS Ineff= 2 , 0
       0    2870     158    6100       0   157.5
Permanent Ineff=
       F       F
Bank Sta=4882.7,5122.7
XS Rating Curve= 0 ,0
Exp/Cntr=0.3,0.1

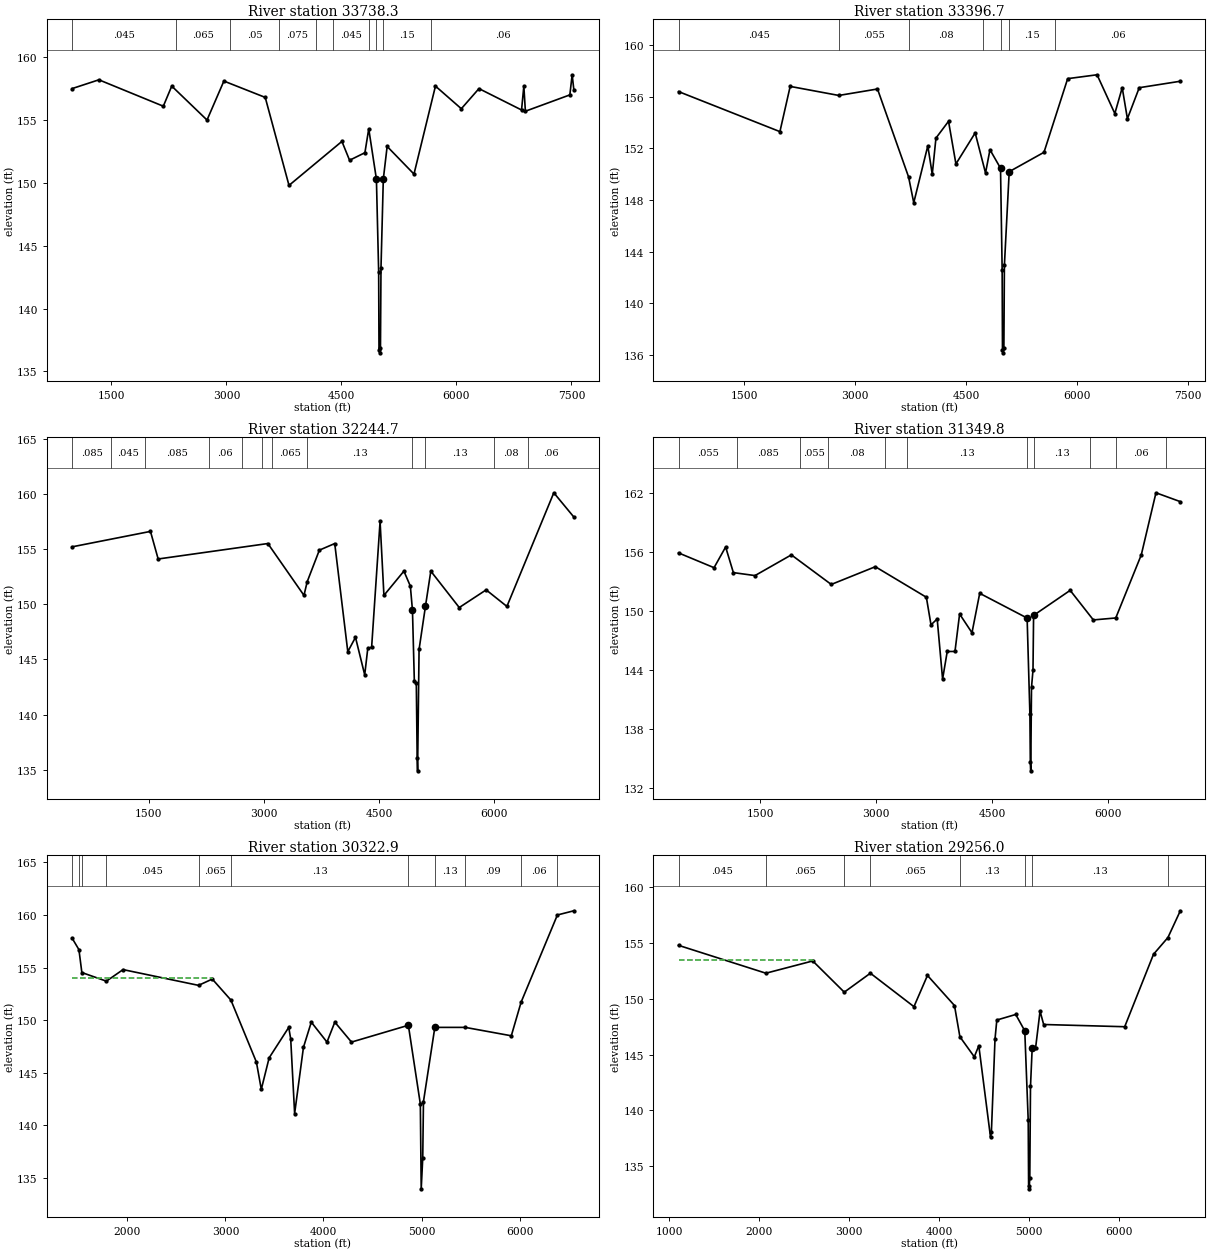
Type RM Length L Ch R = 1 ,33738.3 ,474.6,341.6,283.2
BEGIN DESCRIPTION:
Cross Section XS43.5
END DESCRIPTION:
XS GIS Cut Line= 5
     3019957.583    13934324.278     3020043.327    13931856.469
     3019152.571    13929609.073     3018914.749    13929009.044
     3018745.309    13928011.002
#Sta/Elev= 30
   987.2   157.5  1337.2   158.2  2177.2   156.1  2287.2   157.7  2747.2     155
  2967.2   158.1  3506.5   156.8  3816.5   149.8  4506.5   153.3  4606.5   151.8
  4806.5   152.4  4856.5   154.3  4956.5   150.3  4985.9   142.9  4990.3  136.69
  4999.3  136.48  5009.3  136.84  5016.3  143.25  5046.5   150.3  5096.5   152.9
  5446.5   150.7  5726.5   157.7    6064   155.9    6294   157.5  6849.4   155.8
  6879.4   157.7  6899.4   155.7  7479.4     157  7509.4   158.6  7531.7   157.4
#Mann= 10 ,-1 , 0
   987.2    .045       0  2341.7    .065       0  3047.1     .05       0
  3683.1    .075       0  4173.1     .06       0  4389.6    .045       0
  4861.5     .12       0  4956.5     .08       0  5046.5     .15       0
  5669.3     .06       0
Bank Sta=4956.5,5046.5
XS Rating Curve= 0 ,0
Exp/Cntr=0.3,0.1

Type RM Length L Ch R = 1 ,33396.7 ,1055.9,1152,1190.5
BEGIN DESCRIPTION:
Cross Section XS43
END DESCRIPTION:
XS GIS Cut Line= 4
     3021438.375    13934069.253     3021472.468    13932651.043
     3019228.846    13929488.958     3018992.348    13928022.766
#Sta/Elev= 30
   612.7   156.4  1982.7   153.3  2121.3   156.8  2778.6   156.1  3301.3   156.6
  3721.6  149.79  3791.3   147.8  3981.3   152.2  4041.3     150  4091.3   152.8
  4261.3   154.1  4361.3   150.8  4621.3   153.2  4761.3   150.1  4821.3   151.9
  4963.8  150.47  4985.9   142.6  4990.3  136.39  4999.3  136.18  5009.3  136.54
  5016.3  142.95  5081.3   150.2  5551.3   151.7  5871.3   157.4  6268.5   157.7
  6508.5   154.7  6608.5   156.7  6678.5   154.3  6838.5   156.7  7393.7   157.2
#Mann= 7 ,-1 , 0
   612.7    .045       0  2778.6    .055       0  3721.6     .08       0
  4727.1     .15       0  4963.8     .08       0  5081.3     .15       0
  5696.8     .06       0
Bank Sta=4963.8,5081.3
XS Rating Curve= 0 ,0
Exp/Cntr=0.3,0.1

Type RM Length L Ch R = 1 ,32244.7 ,863.7,894.9,895.2
BEGIN DESCRIPTION:
Cross Section XS42
END DESCRIPTION:
XS GIS Cut Line= 3
      3023029.93    13933150.392      3022010.14   13931658.4953
    3019346.0163   13927761.0166
#Sta/Elev= 30
   505.4   155.2  1525.4   156.6  1625.4   154.1  3052.5   155.5  3522.5   150.8
  3563.9  152.03  3722.5   154.9  3922.5   155.5  4092.5   145.7  4192.5     147
  4312.5   143.6  4352.5     146  4402.5   146.1  4512.5   157.5  4562.5   150.8
  4822.5     153  4906.3  151.64  4933.8  149.45  4958.2  143.03  4983.7  142.87
  4995.2  136.03  5000.5   134.9  5019.7   145.9  5102.5   149.8  5172.5     153
  5542.5   149.7  5892.5   151.3  6162.5   149.8  6772.5   160.1  7033.5   157.9
#Mann= 12 ,-1 , 0
   505.4    .085       0  1015.3    .045       0  1448.8    .085       0
  2285.4     .06       0  2711.6    .045       0    2981     .15       0
  3107.2    .065       0  3563.9     .13       0  4933.8     .08       0
  5102.5     .13       0  5995.3     .08       0  6440.9     .06       0
Bank Sta=4933.8,5102.5
XS Rating Curve= 0 ,0
Exp/Cntr=0.3,0.1

Type RM Length L Ch R = 1 ,31349.8 ,1137.8,1026.9,959.2
BEGIN DESCRIPTION:
Cross Section XS41
END DESCRIPTION:
XS GIS Cut Line= 5
     3023316.729    13932935.511     3023127.982    13932583.734
    3022600.3227   13931600.3084    3020832.1692    13928304.913
    3020717.5631   13927075.2433
#Sta/Elev= 30
   445.8   155.9     905   154.4    1055   156.5    1155   153.9    1435   153.6
    1905   155.7  2421.1   152.7  2991.1   154.5  3651.1   151.4  3711.1   148.6
  3791.1   149.2  3861.1   143.1  3921.1   145.9  4021.1   145.9  4081.1   149.7
  4241.1   147.8  4341.1   151.8  4954.3  149.29  4990.3  139.52  4995.6  134.68
  5001.2  133.79    5011  142.26  5030.3  144.01  5037.9  149.56  5511.1   152.1
  5810.8   149.1  6100.8   149.3  6430.8   155.7  6620.8     162  6935.8   161.1
#Mann= 11 ,-1 , 0
   445.8    .055       0  1202.2    .085       0    2014    .055       0
  2380.2     .08       0  3117.3     .05       0  3401.9     .13       0
  4954.3     .08       0  5037.9     .13       0  5766.9     .04       0
  6098.5     .06       0  6751.6    .045       0
Bank Sta=4954.3,5037.9
XS Rating Curve= 0 ,0
Exp/Cntr=0.3,0.1

Type RM Length L Ch R = 1 ,30322.9 ,1106.6,1066.9,1055.8
BEGIN DESCRIPTION:
Cross Section XS40
END DESCRIPTION:
XS GIS Cut Line= 2
     3024073.179    13931151.711    3021041.6882   13927028.0868
#Sta/Elev= 30
  1435.8   157.8  1505.8   156.7  1535.6  154.52  1785.8   153.7  1955.8   154.8
  2725.8   153.3  2865.8   153.9  3055.8   151.9  3315.8     146  3365.8   143.4
  3445.8   146.4  3645.8   149.3  3665.8   148.2  3705.8   141.1  3795.8   147.4
  3875.8   149.8  4035.8   147.9  4115.8   149.8  4285.8   147.9  4865.8   149.5
  4987.9  142.01  4996.9  133.93  5012.4  136.85  5019.8  142.23  5135.8   149.3
  5445.8   149.3  5915.8   148.5  6015.8   151.7  6385.8     160  6553.8   160.4
#Mann= 11 ,-1 , 0
  1435.8    .055       0  1505.8    .045       0  1535.6     .03       0
  1785.8    .045       0  2725.8    .065       0  3055.8     .13       0
  4865.8     .08       0  5135.8     .13       0  5445.8     .09       0
  6015.8     .06       0  6385.8    .045       0
#XS Ineff= 2 , 0
       0    2865     154               0
Permanent Ineff=
       F       F
Bank Sta=4865.8,5135.8
XS Rating Curve= 0 ,0
Exp/Cntr=0.3,0.1

Type RM Length L Ch R = 1 ,29256.0 ,1058.7,1039.5,849.4
BEGIN DESCRIPTION:
Cross Section XS39
END DESCRIPTION:
XS GIS Cut Line= 4
     3024390.704    13931038.771    3023875.3347   13928937.3313
    3022248.1714   13926961.3086     3022038.025   13926140.1598
#Sta/Elev= 30
    1105   154.8    2075   152.3    2595   153.4    2945   150.6    3235   152.3
  3718.7   149.3  3868.7   152.1  4168.7   149.4  4228.7   146.6  4388.7   144.8
  4438.7   145.8  4568.7   137.6  4578.7   138.1  4618.7   146.4  4638.7   148.1
  4848.7   148.6  4949.1  147.13  4987.3   139.1  4991.7  133.22  4997.6  132.96
  5004.9  133.95  5012.6  142.15  5031.5  145.62 5069.51  145.62  5118.7   148.9
  5158.7   147.7  6058.5   147.5  6378.5     154  6538.5   155.5  6676.1   157.9
#Mann= 8 ,-1 , 0
    1105    .045       0    2075    .065       0    2945     .13       0
    3235    .065       0  4228.7     .13       0  4949.1     .08       0
  5031.5     .13       0  6538.5     .06       0
#XS Ineff= 2 , 0
       0    2595   153.5               0
Permanent Ineff=
       F       F
Bank Sta=4949.1,5031.5
XS Rating Curve= 0 ,0
Exp/Cntr=0.3,0.1

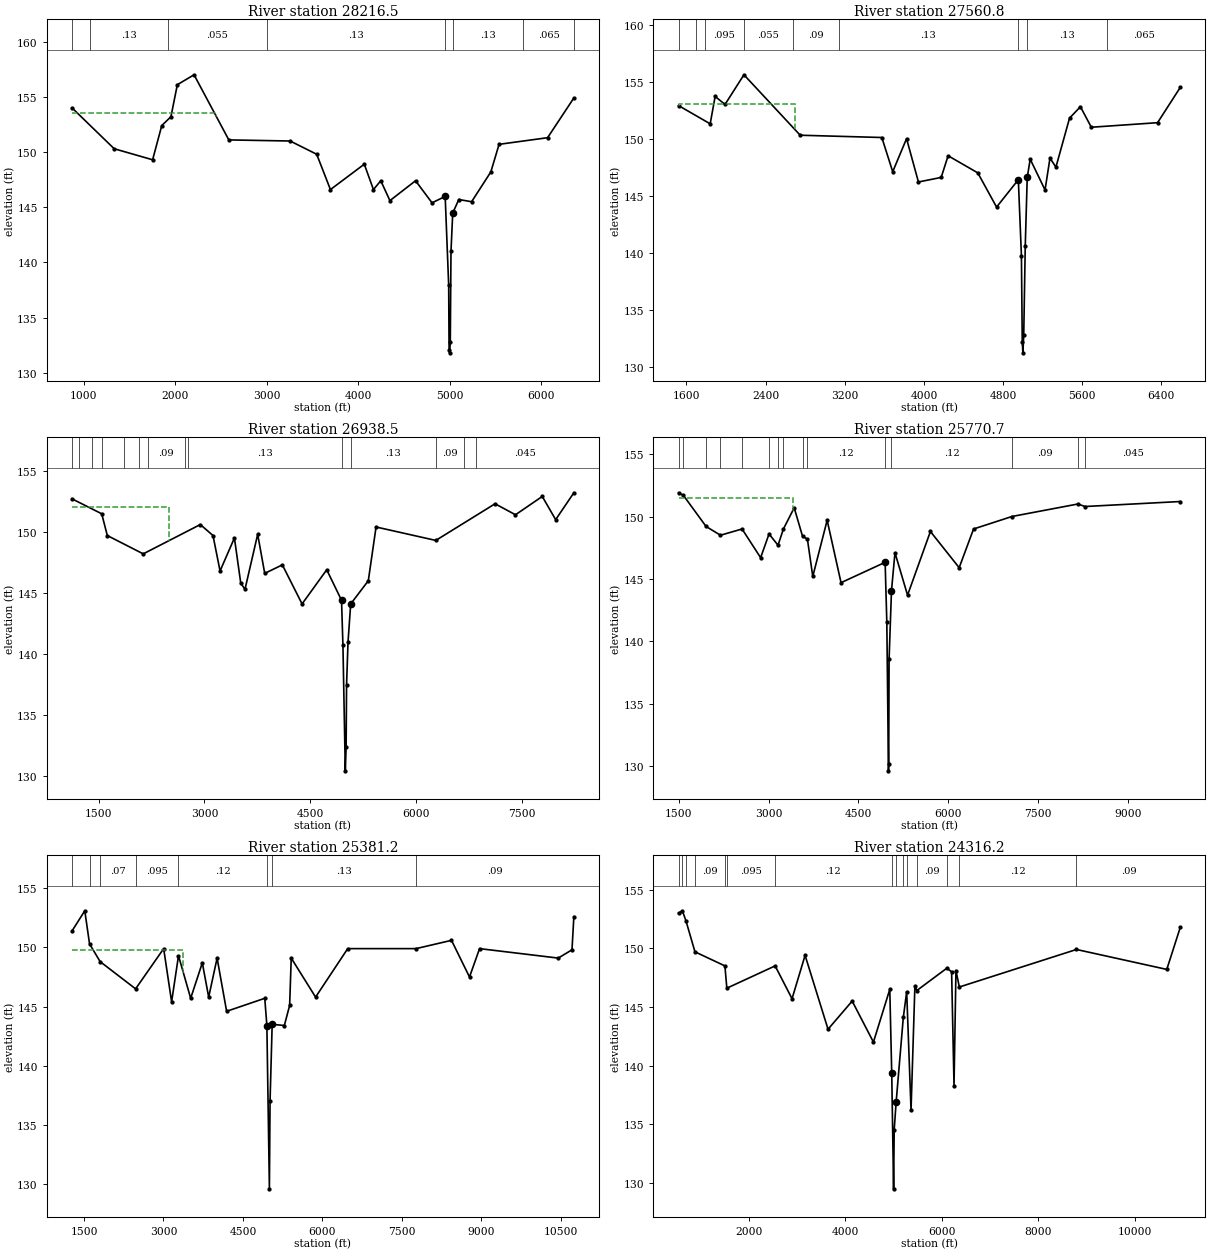
Type RM Length L Ch R = 1 ,28216.5 ,498.7,655.7,614
BEGIN DESCRIPTION:
Cross Section XS38
END DESCRIPTION:
XS GIS Cut Line= 5
    3025576.1634   13930037.5764    3025438.0772   13928742.4086
    3023389.5081   13926864.7721    3023287.2907   13926847.7359
    3022232.0332   13926093.5943
#Sta/Elev= 30
   872.9     154  1332.9   150.3  1752.9   149.3  1852.9   152.4  1952.9   153.2
  2022.9   156.1  2205.4     157  2585.4   151.1  3255.4     151  3545.4   149.8
  3695.4   146.6  4065.4   148.9  4165.4   146.6  4245.4   147.4  4345.4   145.6
  4625.4   147.4  4805.4   145.4  4949.1  145.98  4987.3  137.95  4991.7  132.07
  4997.6  131.81  5004.9   132.8  5012.6     141  5031.5  144.47  5097.9   145.7
  5237.9   145.5  5447.9   148.2  5537.9   150.7  6067.9   151.3  6354.9   154.9
#Mann= 8 ,-1 , 0
   872.9     .05       0  1068.8     .13       0  1918.3    .055       0
  3004.6     .13       0  4949.1     .08       0  5031.5     .13       0
  5800.8    .065       0  6354.9      .2       0
#XS Ineff= 2 , 0
       0    2450   153.5               0
Permanent Ineff=
       F       F
Bank Sta=4949.1,5031.5
XS Rating Curve= 0 ,0
Exp/Cntr=0.3,0.1

Type RM Length L Ch R = 1 ,27560.8 ,395.3,622.3,625.8
BEGIN DESCRIPTION:
Cross Section XS37
END DESCRIPTION:
XS GIS Cut Line= 4
    3025974.2338   13929156.4029    3024812.9681   13927497.1336
     3023372.756    13926215.806     3022282.632    13925958.832
#Sta/Elev= 30
  1519.5   152.9  1839.5   151.3  1889.5   153.7  1989.5     153  2180.7   155.6
  2749.5   150.3  3574.8   150.1  3684.8   147.1  3824.8     150  3944.8   146.2
  4174.8   146.6  4244.8   148.5  4544.8     147  4734.8     144  4954.8   146.4
  4986.1  139.71  4994.5  132.14  5001.1  131.22  5009.4   132.8  5024.8   140.6
  5044.8   146.6  5074.8   148.2  5224.8   145.5  5274.8   148.3  5334.8   147.5
  5472.5   151.8  5582.5   152.8  5692.5     151  6362.5   151.4  6592.5   154.5
#Mann= 9 ,-1 , 0
  1519.5    .095       0  1700.4     .03       0  1784.7    .095       0
  2180.7    .055       0  2675.9     .09       0  3137.1     .13       0
  4954.8     .08       0  5044.8     .13       0  5848.9    .065       0
#XS Ineff= 2 , 0
       0    2700     153               0
Permanent Ineff=
       F       F
Bank Sta=4954.8,5044.8
XS Rating Curve= 0 ,0
Exp/Cntr=0.3,0.1

Type RM Length L Ch R = 1 ,26938.5 ,829.7,1167.8,671.1
BEGIN DESCRIPTION:
Cross Section XS36
END DESCRIPTION:
XS GIS Cut Line= 4
     3026224.929    13928918.105     3024949.476    13927108.344
      3023208.71    13925516.978     3020925.239    13924385.491
#Sta/Elev= 30
  1121.8   152.7  1542.6  151.48  1621.8   149.7  2131.8   148.2  2941.8   150.6
  3121.8   149.7  3221.8   146.8  3425.8   149.5  3515.8   145.8  3575.8   145.3
  3755.8   149.8  3855.8   146.6  4105.8   147.3  4385.8   144.1  4735.8   146.9
  4945.8   144.4  4965.8   140.7  4999.4  130.44    5011  132.39  5017.2  137.45
  5037.9  140.98  5075.8   144.1  5325.8     146  5435.8   150.4  6283.7   149.3
  7124.4   152.3  7414.4   151.4  7794.4   152.9  7984.4     151  8242.8   153.2
#Mann= 14 ,-1 , 0
  1121.8    .065       0  1218.2     .03       0  1411.2    .065       0
  1542.6    .095       0  1857.1    .055       0  2069.3     .07       0
  2192.8     .09       0  2724.5    .045       0  2768.5     .13       0
  4945.8     .08       0  5075.8     .13       0  6283.7     .09       0
  6685.9    .065       0  6850.7    .045       0
#XS Ineff= 2 , 0
       0    2500     152               0
Permanent Ineff=
       F       F
Bank Sta=4945.8,5075.8
XS Rating Curve= 0 ,0
Exp/Cntr=0.3,0.1

Type RM Length L Ch R = 1 ,25770.7 ,285.7,389.5,404.9
BEGIN DESCRIPTION:
Cross Section XS35
END DESCRIPTION:
XS GIS Cut Line= 4
     3026503.386    13928755.672     3025466.509     13926304.44
     3024134.644    13925633.264     3020390.509    13923686.228
#Sta/Elev= 30
  1497.3   151.9  1577.3   151.7  1957.3   149.2  2197.3   148.5  2557.3     149
  2867.3   146.7  3007.3   148.6  3157.3   147.7  3247.3     149  3427.3   150.7
  3567.3   148.4  3647.3   148.2  3737.3   145.2  3977.3   149.7  4208.8   144.7
  4944.7  146.33  4972.9  141.52  5000.4  129.63  5004.4  130.17  5010.7  138.57
  5050.6  144.06  5108.8   147.1  5318.8   143.7  5700.2   148.8  6180.2   145.9
  6420.2     149  7060.2     150  8160.2     151  8280.2   150.8  9870.4   151.2
#Mann= 15 ,-1 , 0
  1497.3    .065       0  1577.3    .065       0  1957.3    .055       0
  2197.3     .07       0  2557.3    .045       0  3007.3    .095       0
  3157.3    .045       0  3247.3    .095       0  3567.3    .045       0
  3647.3     .12       0  4944.7     .08       0  5050.6     .12       0
  7060.2     .09       0  8160.2    .065       0  8280.2    .045       0
#XS Ineff= 2 , 0
       0    3400   151.5               0
Permanent Ineff=
       F       F
Bank Sta=4944.7,5050.6
XS Rating Curve= 0 ,0
Exp/Cntr=0.3,0.1

Type RM Length L Ch R = 1 ,25381.2 ,903.7,1065,952.4
BEGIN DESCRIPTION:
Cross Section XS34
END DESCRIPTION:
XS GIS Cut Line= 5
     3026596.205    13928628.046     3025607.489    13926148.834
      3023518.92    13924726.284     3021043.012    13923039.913
    3019980.7013   13922316.3602
#Sta/Elev= 30
  1273.5   151.4  1513.6   153.1  1603.6   150.3  1803.6   148.8  2473.6   146.5
  3003.6   149.9  3153.6   145.4  3283.6   149.3  3513.6   145.7  3733.6   148.7
  3853.6   145.8  4012.7   149.1  4192.7   144.6  4912.7   145.7  4952.7   143.4
  5000.4  129.59  5012.7     137  5052.7   143.5  5282.7   143.4  5382.7   145.1
  5412.7   149.1  5872.7   145.8  6479.7   149.9  7769.7   149.9  8439.7   150.6
  8779.7   147.5  8969.7   149.9 10455.4   149.1 10715.4   149.8 10750.7   152.6
#Mann= 8 ,-1 , 0
  1273.5    .065       0  1603.6    .055       0  1803.6     .07       0
  2473.6    .095       0  3283.6     .12       0  4952.7     .08       0
  5052.7     .13       0  7769.7     .09       0
#XS Ineff= 2 , 0
       0    3375   149.8               0
Permanent Ineff=
       F       F
Bank Sta=4952.7,5052.7
XS Rating Curve= 0 ,0
Exp/Cntr=0.3,0.1

Type RM Length L Ch R = 1 ,24316.2 ,772.1,1061.8,1085.3
BEGIN DESCRIPTION:
Cross Section XS33
END DESCRIPTION:
XS GIS Cut Line= 5
    3026747.0356   13928512.0224    3026172.8319   13925725.3788
    3025202.0163   13924718.6631    3021862.1832   13922619.0239
    3019999.3518   13921447.9253
#Sta/Elev= 30
   547.9     153   627.9   153.2   704.1  152.31   887.9   149.7  1507.9   148.5
  1547.9   146.6  2547.9   148.5  2897.9   145.7  3167.9   149.4  3643.1   143.1
  4143.1   145.5  4583.1     142  4921.6   146.5  4961.6   139.4  5000.6  129.49
    5013  134.52  5052.6  136.86  5201.6   144.1  5271.6   146.3  5361.6   136.2
  5441.6   146.8  5481.6   146.4  6101.6   148.3  6201.6     148  6251.6   138.3
  6291.6   148.1  6361.6   146.7  8786.6   149.9 10656.6   148.2   10937   151.8
#Mann= 15 ,-1 , 0
   547.9    .065       0   627.9    .065       0   704.1    .055       0
   887.9     .09       0  1507.9     .07       0  1547.9    .095       0
  2547.9     .12       0  4961.6     .08       0  5052.6     .13       0
  5201.6    .045       0  5271.6     .05       0  5481.6     .09       0
  6101.6     .05       0  6361.6     .12       0  8786.6     .09       0
#XS Ineff= 2 , 0
       0                    5942       0
Permanent Ineff=
       F       F
Bank Sta=4961.6,5052.6
XS Rating Curve= 0 ,0
Exp/Cntr=0.3,0.1

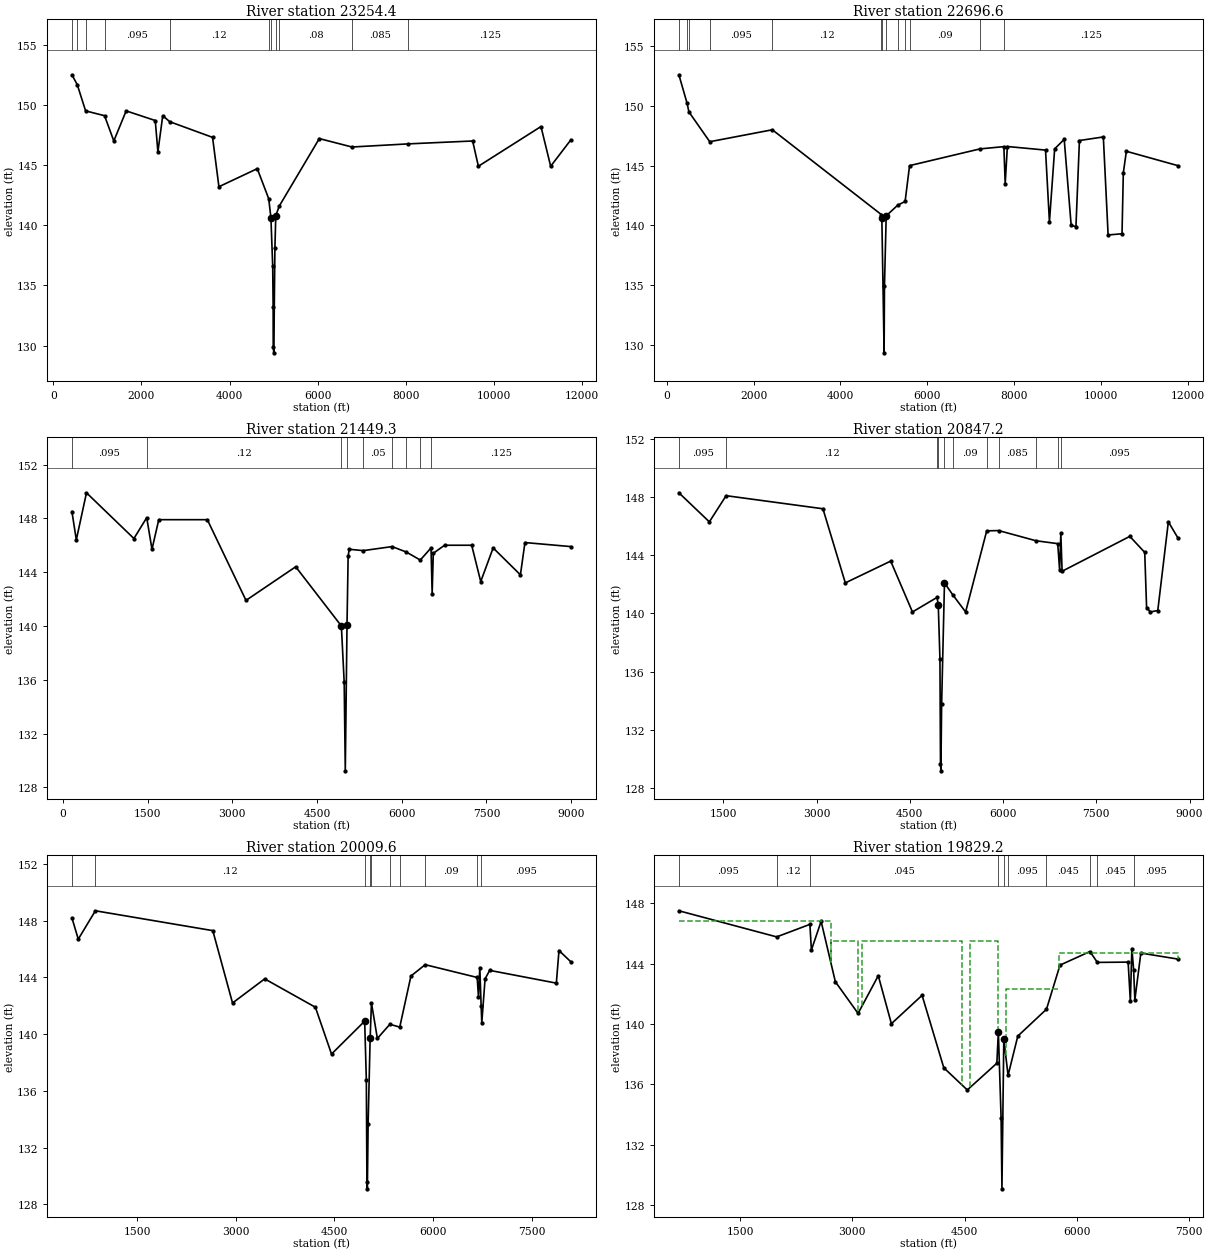
Type RM Length L Ch R = 1 ,23254.4 ,520,557.8,548
BEGIN DESCRIPTION:
Cross Section XS32
END DESCRIPTION:
XS GIS Cut Line= 5
    3026932.6733   13928488.8177    3026504.2115   13925283.0875
    3025721.5692   13923948.5226    3023767.3019    13921083.368
    3022037.8739   13918547.8507
#Sta/Elev= 30
   424.4   152.5   546.1  151.67   734.4   149.5  1164.4   149.1  1374.4     147
  1654.4   149.5  2314.4   148.7  2374.4   146.1  2484.4   149.1  2644.4   148.6
  3614.4   147.3  3758.6   143.2  4628.6   144.7  4888.6   142.2  4938.6   140.6
  4978.6   136.6  4988.6   133.2  4990.5  129.89    5004   129.4  5028.6   138.1
  5048.6   140.8  5128.6   141.6  6035.8   147.2  6775.8   146.5  8055.2  146.76
  9513.9     147  9643.9   144.9 11063.9   148.2 11283.9   144.9 11743.1   147.1
#Mann= 11 ,-1 , 0
   424.4     .09       0   546.1    .055       0   734.4     .09       0
  1164.4    .095       0  2644.4     .12       0  4888.6    .045       0
  4938.6     .05       0  5048.6    .045       0  5128.6     .08       0
  6775.8    .085       0  8055.2    .125       0
#XS Ineff= 2 , 0
       0                    6400       0
Permanent Ineff=
       F       F
Bank Sta=4938.6,5048.6
XS Rating Curve= 0 ,0
Exp/Cntr=0.3,0.1

Type RM Length L Ch R = 1 ,22696.6 ,728.2,1247.3,1010
BEGIN DESCRIPTION:
Cross Section XS31
END DESCRIPTION:
XS GIS Cut Line= 5
     3027083.504   13928454.0106    3026842.3884   13924912.6576
    3026274.7097   13923823.8712     3024226.033   13920927.4662
    3022404.2212   13918351.8013
#Sta/Elev= 30
   282.1   152.6   472.1   150.2   512.1   149.5   992.1     147  2432.1     148
  4941.7   140.9  4951.7   140.6    5004  129.34  5011.7   134.9  5051.7   140.8
  5319.5   141.7  5486.6     142  5589.5     145  7209.5   146.4  7758.9  146.59
  7789.5   143.5  7839.5   146.6  8717.3   146.3  8807.3   140.3  8927.3   146.4
  9147.3   147.2  9307.3     140  9417.3   139.9  9497.3   147.1 10047.3   147.4
 10157.3   139.2 10477.3   139.3 10507.3   144.4 10577.3   146.2 11762.1     145
#Mann= 13 ,-1 , 0
   282.1     .09       0   472.1    .055       0   512.1     .09       0
   992.1    .095       0  2432.1     .12       0  4941.7    .045       0
  4951.7     .05       0  5051.7    .045       0  5319.5     .08       0
  5486.6    .045       0  5589.5     .09       0  7209.5    .085       0
  7758.9    .125       0
#XS Ineff= 2 , 0
       0                    6735       0
Permanent Ineff=
       F       F
Bank Sta=4951.7,5051.7
XS Rating Curve= 0 ,0
Exp/Cntr=0.3,0.1

Type RM Length L Ch R = 1 ,21449.3 ,522.4,602.1,611.5
BEGIN DESCRIPTION:
Cross Section XS30
END DESCRIPTION:
XS GIS Cut Line= 6
      3027110.44      13927636.4    3026952.8529   13924788.3742
    3026524.0125   13922959.1022    3026508.4311   13922772.1251
    3025215.6156   13920512.8725    3024562.9186   13919372.2555
#Sta/Elev= 30
  159.93   148.5   237.6   146.4   417.6   149.9  1257.6   146.5  1484.5  148.05
  1577.6   145.7  1697.6   147.9  2557.6   147.9  3242.4   141.9  4122.4   144.4
  4931.2     140  4981.2   135.8  5000.7  129.23  5031.2   140.1  5051.2   145.2
  5071.2   145.7  5318.9   145.6  5828.9   145.9  6078.9   145.5  6328.9   144.9
  6518.9   145.8  6538.9   142.4  6558.9   145.4  6758.9     146  7238.9     146
  7398.9   143.3  7618.9   145.8  8101.9   143.8  8181.9   146.2    8996   145.9
#Mann= 9 ,-1 , 0
  159.93    .095       0  1484.5     .12       0  4931.2     .05       0
  5031.2    .045       0  5318.9     .05       0  5828.9    .065       0
  6078.9     .06       0  6328.9     .09       0  6518.9    .125       0
#XS Ineff= 2 , 0
       0                    6800       0
Permanent Ineff=
       F       F
Bank Sta=4931.2,5031.2
XS Rating Curve= 0 ,0
Exp/Cntr=0.3,0.1

Type RM Length L Ch R = 1 ,20847.2 ,430.8,837.6,702.9
BEGIN DESCRIPTION:
Cross Section XS29
END DESCRIPTION:
XS GIS Cut Line= 6
      3027228.97      13927030.5    3027186.2231   13925078.1759
    3027139.4788   13922943.5208    3026964.7522   13922336.4577
    3025681.5766   13920464.6697     3025103.113   13919620.8558
#Sta/Elev= 30
   785.9   148.3  1275.9   146.3  1545.9   148.1    3103   147.2    3463   142.1
    4193   143.6    4543   140.1  4938.1   141.1  4958.1   140.6  4985.1  136.86
  4993.9  129.64  5000.7  129.17  5012.3  133.77  5058.1   142.1  5188.1   141.3
  5398.1   140.1  5737.5  145.68  5929.9   145.7  6529.9     145  6879.9   144.8
  6909.9     143  6929.9   145.5  6949.9   142.9  8039.2   145.3  8279.2   144.2
  8309.2   140.4  8369.2   140.1  8489.2   140.2  8659.2   146.3  8812.3   145.2
#Mann= 11 ,-1 , 0
   785.9    .095       0  1545.9     .12       0  4938.1    .045       0
  4958.1     .04       0  5058.1    .045       0  5188.1     .09       0
  5737.5    .045       0  5929.9    .085       0  6529.9     .09       0
  6879.9    .045       0  6929.9    .095       0
#XS Ineff= 2 , 0
       0                    7250       0
Permanent Ineff=
       F       F
Bank Sta=4958.1,5058.1
XS Rating Curve= 0 ,0
Exp/Cntr=0.3,0.1

Type RM Length L Ch R = 1 ,20009.6 ,188.8,180.4,144.8
BEGIN DESCRIPTION:
Cross Section US Telge Road_Con
END DESCRIPTION:
XS GIS Cut Line= 6
      3027296.79      13926683.9    3027281.6587   13924158.0542
     3027485.675   13923281.3358    3027504.2774   13922295.8902
    3027241.3281   13921596.7085    3025548.8945   13919860.8792
#Sta/Elev= 30
     511   148.2   607.3   146.7   867.3   148.7  2651.7   147.3  2951.7   142.2
  3440.7   143.9  4210.7   141.9    4456   138.6 4959.86  140.92  4985.1  136.79
  4993.9  129.57  5000.7   129.1  5012.3   133.7  5042.8   139.7  5062.8   142.2
  5152.8   139.7  5342.8   140.7  5492.8   140.5  5662.8   144.1  5879.6   144.9
  6669.6     144  6689.6   142.6  6709.6   144.7  6729.6     142  6739.6   140.8
  6789.6   143.9  6859.6   144.5  7872.6   143.6  7912.6   145.9    8094   145.1
#Mann= 10 ,-1 , 0
     511    .095       0   867.3     .12       0 4959.86    .055       0
  5042.8    .045       0  5062.8     .12       0  5342.8    .045       0
  5492.8    .045       0  5879.6     .09       0  6669.6    .045       0
  6729.6    .095       0
#XS Ineff= 2 , 0
       0                    7500       0
Permanent Ineff=
       F       F
Bank Sta=4959.86,5042.8
XS Rating Curve= 0 ,0
Exp/Cntr=0.5,0.3

Type RM Length L Ch R = 1 ,19829.2 ,64,64,64
BEGIN DESCRIPTION:
Upstream Section of Bridge/Culvert/Weir
END DESCRIPTION:
XS GIS Cut Line= 6
    3027350.1762   13926411.0561    3027333.3898      13924237.5
     3027636.009   13923289.8121    3027640.1597    13922220.947
     3027351.558   13921514.1304    3026181.0287   13920330.7151
#Sta/Elev= 30
   683.9   147.5  1990.4  145.77  2433.9   146.6  2453.9   144.9  2583.9   146.8
  2773.9   142.8  3077.5   140.7  3347.5   143.2  3522.4  140.02  3932.4   141.9
  4222.4   137.1  4536.5  135.63  4931.2   137.4  4951.2   139.5  4988.1  133.74
  4999.2  129.08    5024  138.99  5081.2   136.6  5211.2   139.2  5594.4  140.98
  5774.7   143.9  6174.7   144.8  6273.9  144.08  6684.7   144.1  6714.7   141.5
  6734.7     145  6758.1  143.59  6774.7   141.6  6854.7   144.7  7349.2   144.3
#Mann= 10 ,-1 , 0
   683.9    .095       0  1990.4     .12       0  2433.9    .045       0
  4951.2    .055       0    5024    .045       0  5081.2    .095       0
  5594.4    .045       0  6174.7    .085       0  6273.9    .045       0
  6758.1    .095       0
#XS Ineff= 6 ,-1
       0    2715   146.8    2715    3070   145.5    3130    4466   145.5
    4577    4949   145.5    5050    5760   142.3    5760    7350   144.7
Permanent Ineff=
       F       F       F       F       F       F
Bank Sta=4951.2,5024
XS Rating Curve= 0 ,0
Exp/Cntr=0.5,0.3