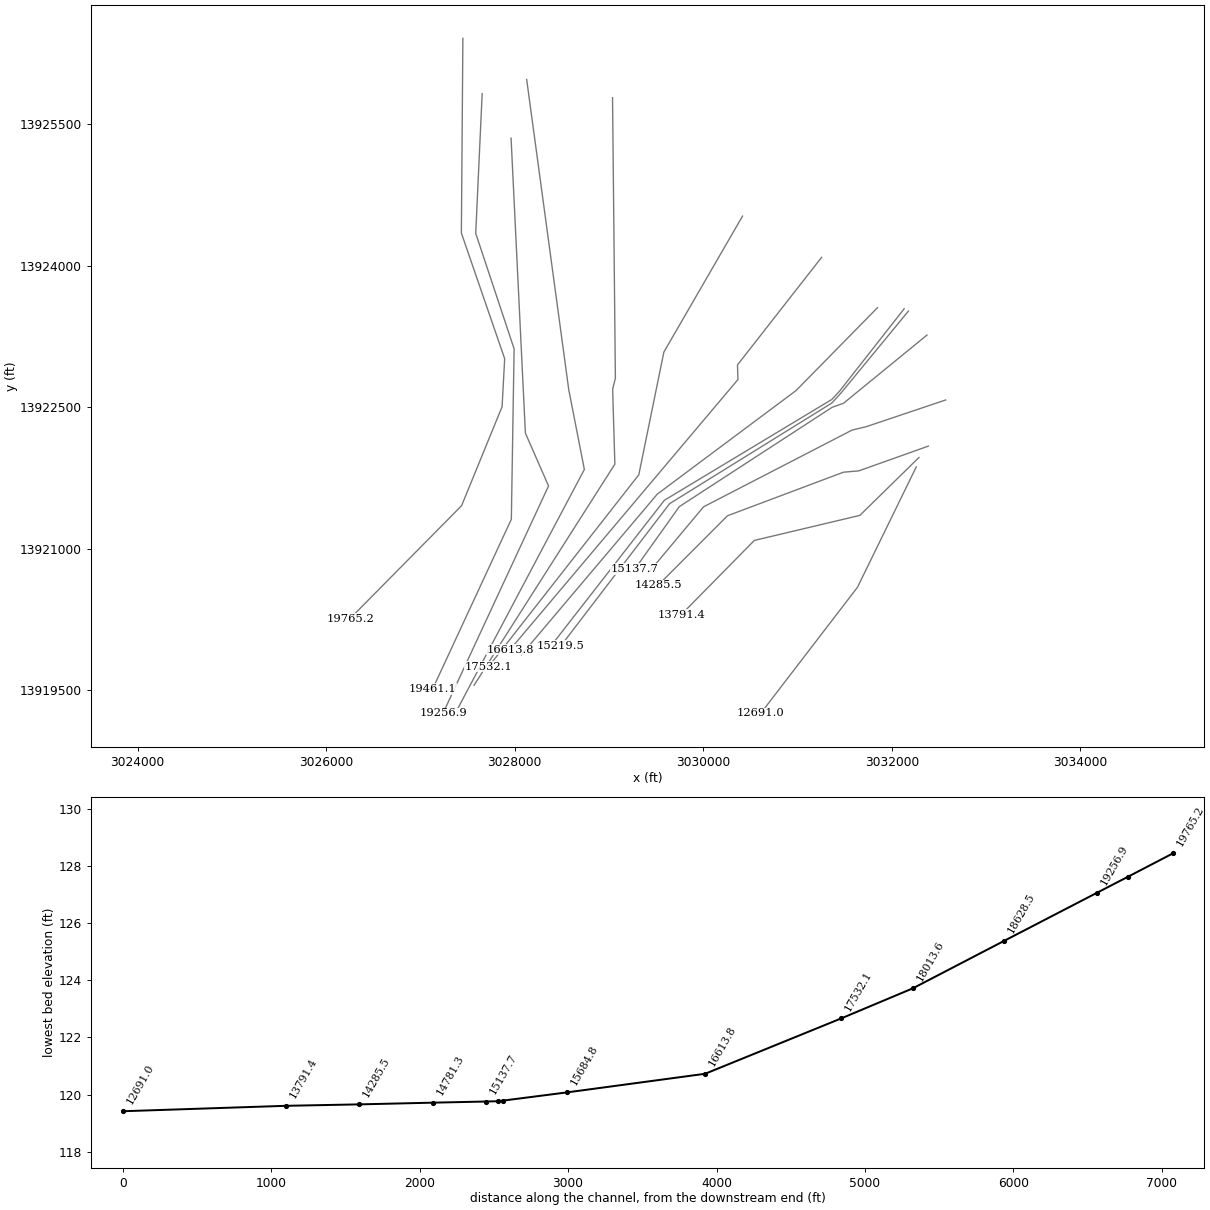
HEC-RAS study L100-00-00.prj: L100-00-00

--- L100-00-00.g01 (geometry) --- (continued)

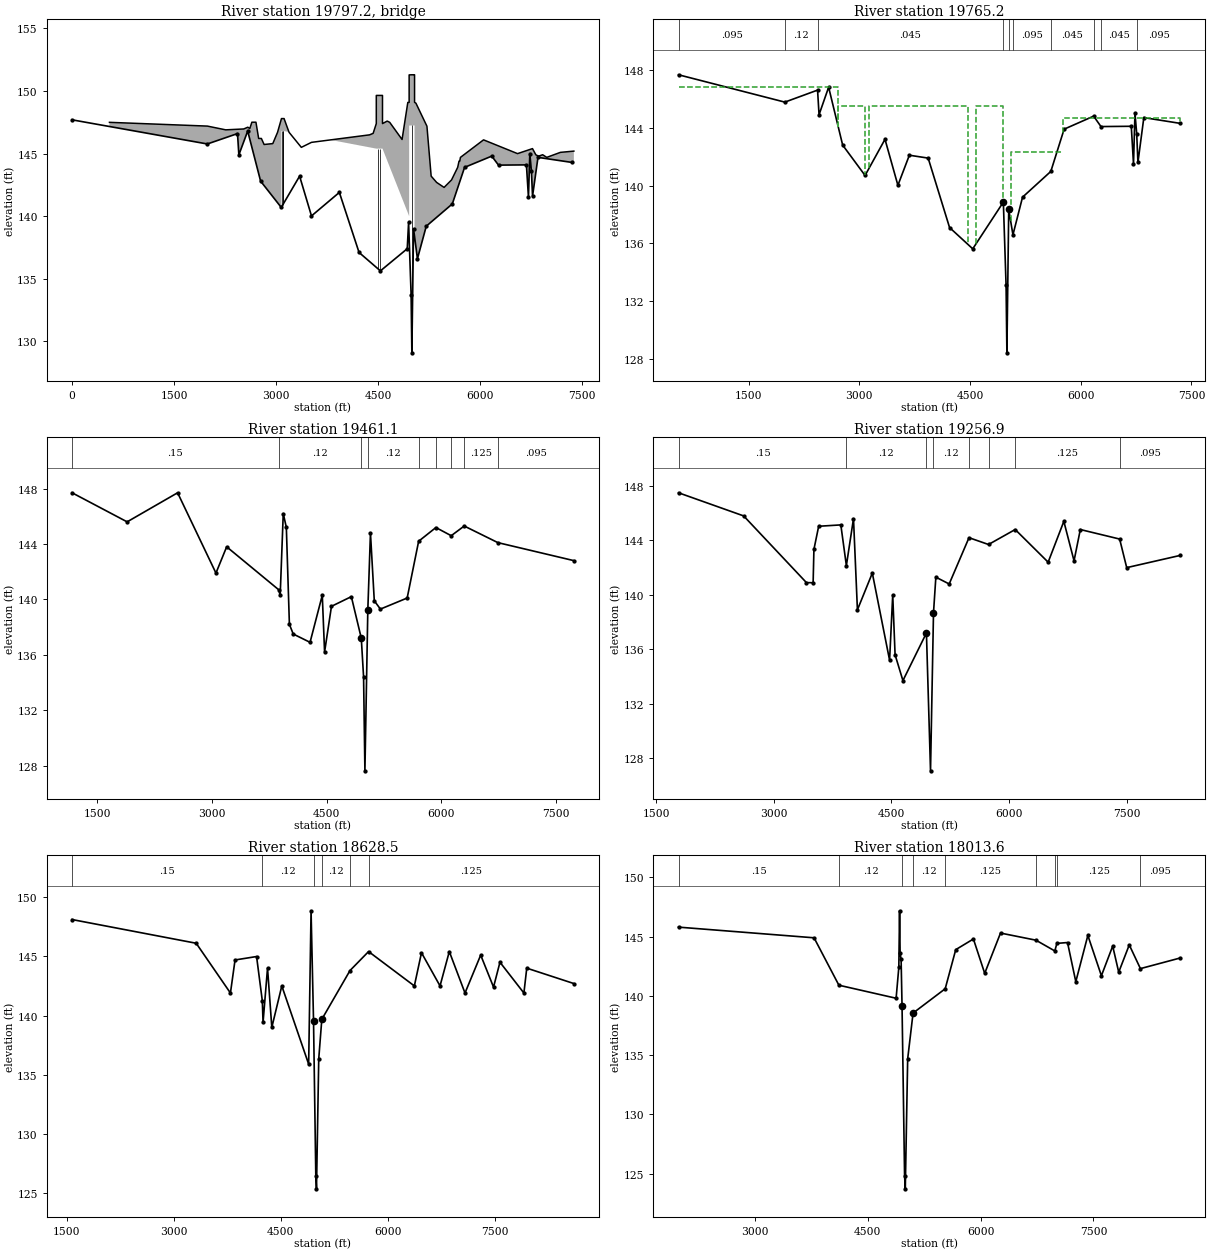
Type RM Length L Ch R = 3 ,19797.2 ,,,
BEGIN DESCRIPTION:
Spring-Cypress Road
Structure ID: L100-00-00-S3
END DESCRIPTION:
Bridge Culvert--1,0,-1,-1, 0
Deck Dist Width WeirC Skew NumUp NumDn MinLoCord MaxHiCord MaxSubmerge Is_Ogee
10,44,2.6,0, 60, 60, , , 0.95, 0, 1,1,,
     550  1990.5  2260.5  2525.2  2585.2  2615.2  2645.2  2705.2  2745.2  2785.2
  2825.2  2952.9  3022.9  3057.7  3080.7  3119.1  3157.7  3192.9  3372.9  3522.4
  4376.5  4429.5  4475.9    4476  4567.1  4567.2  4636.5  4673.2  4855.1  4939.5
 4958.99  4959.1  4959.3 4959.41  4959.5  4988.1 5038.59  5038.6  5038.7  5038.9
    5039  5059.1    5221  5283.2  5363.2  5473.2  5583.2  5673.2  5693.2    5704
    5714  6053.8  6553.8    6774    6824    6864  6923.8    6984    7184  7382.6
   147.5   147.2   146.9  146.97  147.11  147.01  147.51  147.51  146.21  146.21
  145.73   145.8   146.7  147.36   147.8   147.8  147.22   146.7   145.5   145.9
   146.5  146.62   147.4  149.65  149.65   147.4   147.6   147.5  146.13  149.09
  149.09  151.29  151.29  151.29  151.29   151.3   151.3   151.3   151.3   151.3
   149.1  149.03  147.19   143.2   142.7   142.3   142.9   143.9   144.4   144.4
   144.7   146.1     145   145.4   144.9   144.8  144.91   144.7   145.1   145.2
                                                                                
                                   146.8   146.8
                           145.4   145.4
                             140  147.24  147.25  147.25     140
                                                                                
                                                                                
     550  1990.5  2260.5  2525.2  2585.2  2615.2  2645.2  2705.2  2745.2  2785.2
  2825.2  2952.9  3022.9  3057.7  3080.7  3119.1  3157.7  3192.9  3372.9  3522.4
  4376.5  4429.5  4475.9    4476  4567.1  4567.2  4636.5  4673.2  4855.1  4939.5
 4958.99  4959.1  4959.3 4959.41  4959.5  4988.1 5038.59  5038.6  5038.7  5038.9
    5039  5059.1    5221  5283.2  5363.2  5473.2  5583.2  5673.2  5693.2    5704
    5714  6053.8  6553.8    6774    6824    6864  6923.8    6984    7184  7382.6
   147.5   147.2   146.9  146.97  147.11  147.01  147.51  147.51  146.21  146.21
  145.73   145.8   146.7  147.36   147.8   147.8  147.22   146.7   145.5   145.9
   146.5  146.62   147.4  149.65  149.65   147.4   147.6   147.5  146.13  149.09
  149.09  151.29  151.29  151.29  151.29   151.3   151.3   151.3   151.3   151.3
   149.1  149.03  147.19   143.2   142.7   142.3   142.9   143.9   144.4   144.4
   144.7   146.1     145   145.4   144.9   144.8  144.91   144.7   145.1   145.2
                                                                                
                                   146.8   146.8
                           145.4   145.4
                             140  146.63  146.64  146.64     140
                                                                                
                                                                                
Pier Skew, UpSta & Num, DnSta & Num=  ,3090.2, 2 ,3090.2, 2 , 0 , 0 , 0 ,,
       1       1
     135     147
       1       1
     135     147
Pier Skew, UpSta & Num, DnSta & Num=  ,3099.7, 2 ,3099.7, 2 , 0 , 0 , 0 ,,
       1       1
     135     147
       1       1
     135     147
Pier Skew, UpSta & Num, DnSta & Num=  ,3109.2, 2 ,3109.2, 2 , 0 , 0 , 0 ,,
       1       1
     135     147
       1       1
     135     147
Pier Skew, UpSta & Num, DnSta & Num=  ,4506.25, 2 ,4506.25, 2 , 0 , 0 , 0 ,,
       1       1
     135     146
     1.4     1.4
     135     146
Pier Skew, UpSta & Num, DnSta & Num=  ,4536.55, 2 ,4536.55, 2 , 0 , 0 , 0 ,,
       1       1
     135     146
     1.4     1.4
     135     146
Pier Skew, UpSta & Num, DnSta & Num=  ,4999.2, 2 ,4999.2, 2 , 0 , 0 , 0 ,,
     1.3     1.3
   128.1  148.25
     1.3     1.3
  127.49  147.64
Abutment Skew #Up #Dn= , 2 , 2
    4476    4502
   145.4     135
    4476    4502
   145.4     135
Abutment Skew #Up #Dn= , 2 , 2
  4541.1  4567.1
     135   145.4
  4541.1  4567.1
     135   145.4
Abutment Skew #Up #Dn= , 2 , 2
  4959.3  4960.7
  147.24  145.65
  4959.3  4960.7
  146.63  145.04
Abutment Skew #Up #Dn= , 2 , 2
  5037.7 5038.79
  143.49  147.25
  5037.7 5038.79
  142.88  146.64
BR Coef= 1 , 1 , 1 ,1.25, 0 ,,,0.8,-1,2,0,
WSPro=,,,, 1 ,,,, 0 ,,,, 0 ,,,,-1 ,-1 ,-1 , 0 , 0 , 0 , 0 , 0
BR U #Sta/Elev= 30
       0   147.7  1990.4  145.77  2433.9   146.6  2453.9   144.9  2583.9   146.8
  2773.9   142.8  3077.5   140.7  3347.5   143.2  3522.4  140.02  3932.4   141.9
  4222.4   137.1  4536.5  135.63  4931.2   137.4  4951.2   139.5  4988.1  133.74
  4999.2  129.08    5024  138.99  5081.2   136.6  5211.2   139.2  5594.4  140.98
  5774.7   143.9  6174.7   144.8  6273.9  144.08  6684.7   144.1  6714.7   141.5
  6734.7     145  6758.1  143.59  6774.7   141.6  6854.7   144.7  7349.2   144.3
BR U #Mann= 10
       0    .095  1990.4     .12  2433.9    .045  4951.2     .05    5024    .045
  5081.2    .095  5594.4    .045  6174.7    .085  6273.9    .045  6758.1    .095
BR D #Sta/Elev= 30
       0   147.7   723.9   148.4  1990.4  145.77  2433.9   146.6  2453.9   144.9
  2583.9   146.8  2773.9   142.8  3077.5   140.7  3347.5   143.2  3522.4  140.02
  3932.4   141.9  4222.4   137.1  4536.5  135.63  4951.2  138.86  4988.1   133.1
  4999.2  128.44    5024  138.35  5081.2   136.6  5211.2   139.2  5594.4  140.98
  5774.7   143.9  6174.7   144.8  6273.9  144.08  6684.7   144.1  6714.7   141.5
  6734.7     145  6758.1  143.59  6774.7   141.6  6854.7   144.7  7349.2   144.3
BR D #Mann= 10
       0    .095  1990.4     .12  2433.9    .045  4951.2     .05    5024    .045
  5081.2    .095  5594.4    .045  6174.7    .085  6273.9    .045  6758.1    .095
BC Design=,, 0 ,, 0 ,,,,,,
BC HTab HWMax=147.5
BC Use User HTab Curves=0
BC User HTab FreeFlow(D)= 0

Type RM Length L Ch R = 1 ,19765.2 ,128.9,303.5,380.5
BEGIN DESCRIPTION:
Downstream Section of Bridge/Culvert/Weir
END DESCRIPTION:
XS GIS Cut Line= 6
    3027450.1732   13926410.2838    3027434.2381   13924346.9588
    3027893.5715   13923015.1777    3027866.0941   13922506.9608
    3027436.6271   13921457.9341    3026252.1254   13920260.3926
#Sta/Elev= 30
     550  147.66  1990.4  145.77  2433.9   146.6  2453.9   144.9  2583.9   146.8
  2773.9   142.8  3077.5   140.7  3347.5   143.2  3522.4  140.02  3677.5   142.1
  3932.4   141.9  4222.4   137.1  4536.5  135.63  4951.2  138.86  4988.1   133.1
  4999.2  128.44    5024  138.35  5081.2   136.6  5211.2   139.2  5594.4  140.98
  5774.7   143.9  6174.7   144.8  6273.9  144.08  6684.7   144.1  6714.7   141.5
  6734.7     145  6758.1  143.59  6774.7   141.6  6854.7   144.7  7349.2   144.3
#Mann= 10 ,-1 , 0
     550    .095       0  1990.4     .12       0  2433.9    .045       0
  4951.2    .055       0    5024    .045       0  5081.2    .095       0
  5594.4    .045       0  6174.7    .085       0  6273.9    .045       0
  6758.1    .095       0
#XS Ineff= 6 ,-1
       0    2715   146.8    2715    3070   145.5    3130    4466   145.5
    4577    4949   145.5    5050    5760   142.3    5760    7350   144.7
Permanent Ineff=
       F       F       F       F       F       F
Bank Sta=4951.2,5024
XS Rating Curve= 0 ,0
Exp/Cntr=0.5,0.3

Type RM Length L Ch R = 1 ,19461.1 ,97.3,204.8,289.3
BEGIN DESCRIPTION:
Cross Section XS28.5
END DESCRIPTION:
XS GIS Cut Line= 6
    3027654.7674   13925824.2689     3027586.366    13924344.311
    3027993.6653   13923119.9256    3027964.3384   13921314.0415
    3027279.5653   13919839.2381    3027128.9874   13919514.9368
#Sta/Elev= 30
  1169.9   147.7  1889.9   145.6  2549.9   147.7  3051.4   141.9  3191.4   143.8
  3871.4   140.7  3891.4   140.3  3931.4   146.2  3971.8   145.2  4011.8   138.2
  4061.8   137.5  4281.8   136.9  4441.8   140.3  4471.8   136.2  4561.8   139.5
  4821.8   140.2  4951.8   137.2  4981.8   134.4  4999.2  127.62  5037.2  139.23
  5071.8   144.8  5121.8   139.9  5201.8   139.3  5551.8   140.1  5701.8   144.2
  5927.5  145.19  6127.9   144.6  6297.9   145.3  6737.9   144.1  7731.5   142.8
#Mann= 9 ,-1 , 0
  1169.9     .15       0  3871.4     .12       0  4951.8    .055       0
  5037.2     .12       0  5701.8    .075       0  5927.5    .045       0
  6127.9    .075       0  6297.9    .125       0  6737.9    .095       0
#XS Ineff= 2 , 0
       0                    5925       0
Permanent Ineff=
       F       F
Bank Sta=4951.8,5037.2
XS Rating Curve= 0 ,0
Exp/Cntr=0.3,0.1

Type RM Length L Ch R = 1 ,19256.9 ,479.2,628.4,581.5
BEGIN DESCRIPTION:
Cross Section XS28
END DESCRIPTION:
XS GIS Cut Line= 6
    3027961.3871   13925352.7234    3028113.3178   13922226.7752
    3028335.2511   13921720.7674    3028358.8654   13921666.9268
    3027574.5315   13919978.9589    3027240.1632   13919259.3637
#Sta/Elev= 30
  1787.5   147.5  2617.5   145.8  3417.5   140.9    3503  140.89  3513.1  143.34
  3573.6  145.04  3856.1  145.14  3926.7  142.15  4017.5   145.6  4067.5   138.9
  4257.5   141.6  4477.5   135.2  4517.5     140  4547.5   135.6  4647.5   133.7
  4947.1   137.2  4999.2  127.07  5037.2  138.68  5067.1   141.3  5237.1   140.8
  5489.7   144.2  5738.5   143.7  6078.5   144.8  6498.5   142.4  6698.5   145.4
  6828.5   142.5  6908.5   144.8  7409.8   144.1  7499.8     142  8183.2   142.9
#Mann= 8 ,-1 , 0
  1787.5     .15       0  3926.7     .12       0  4947.1    .065       0
  5037.2     .12       0  5489.7    .045       0  5738.5    .075       0
  6078.5    .125       0  7409.8    .095       0
#XS Ineff= 2 , 0
       0                    5522       0
Permanent Ineff=
       F       F
Bank Sta=4947.1,5037.2
XS Rating Curve= 0 ,0
Exp/Cntr=0.3,0.1

Type RM Length L Ch R = 1 ,18628.5 ,550,614.9,479.1
BEGIN DESCRIPTION:
Cross Section XS27
END DESCRIPTION:
XS GIS Cut Line= 5
    3028127.0059   13925973.7941    3028573.2639   13922687.6032
    3028738.8716   13921841.9032    3027776.3504   13920025.5325
    3027401.5791   13919318.3028
#Sta/Elev= 30
  1574.2   148.1  3314.2   146.1  3794.2   141.9  3858.8  144.69  4160.7  144.98
  4241.2  141.24  4251.3  139.42  4314.2     144  4374.2     139  4514.2   142.5
  4890.6   135.9  4924.4  148.84 4958.92  139.58  4990.9  126.49  5000.4  125.38
  5032.1  136.35    5075  139.68  5470.6   143.8  5730.6   145.4  6372.3   142.5
  6472.3   145.3  6732.3   142.5  6862.3   145.4  7082.3   141.9  7302.3   145.1
  7482.3   142.4  7572.3   144.5    7908   141.9    7948     144  8608.3   142.7
#Mann= 6 ,-1 , 0
  1574.2     .15       0  4241.2     .12       0 4958.92    .065       0
    5075     .12       0  5470.6    .045       0  5730.6    .125       0
#XS Ineff= 2 , 0
       0                    5875       0
Permanent Ineff=
       F       F
Bank Sta=4958.92,5075
XS Rating Curve= 0 ,0
Exp/Cntr=0.3,0.1

Type RM Length L Ch R = 1 ,18013.6 ,517.5,481.5,441.4
BEGIN DESCRIPTION:
Cross Section XS26
END DESCRIPTION:
XS GIS Cut Line= 6
    3029037.9096   13925780.5721    3029068.0476   13922808.8737
    3029038.9427    13922692.454    3029062.5086   13921897.9461
    3027853.9731   13920002.2457    3027568.9837   13919555.2133
#Sta/Elev= 30
  1988.5   145.8  3788.5   144.9  4118.5   140.9  4878.5   139.8  4914.5  142.42
  4924.4  147.18  4931.6  143.59  4944.8  143.08 4957.21  139.14  4990.9  124.83
  5000.4  123.72  5032.1  134.69  5103.6  138.55  5530.4   140.6  5670.4   143.9
  5905.2   144.8  6055.2   141.9  6265.2   145.3  6735.2   144.7  6986.5  143.79
    7014  144.43  7155.2   144.5  7265.2   141.2  7425.2   145.1  7605.2   141.7
  7755.2   144.2  7835.2     142  7975.2   144.3  8123.4   142.3  8653.5   143.2
#Mann= 9 ,-1 , 0
  1988.5     .15       0  4118.5     .12       0 4957.21    .065       0
  5103.6     .12       0  5530.4    .125       0  6735.2    .075       0
  6986.5     .04       0    7014    .125       0  8123.4    .095       0
#XS Ineff= 2 , 0
       0                    5625       0
Permanent Ineff=
       F       F
Bank Sta=4957.21,5103.6
XS Rating Curve= 0 ,0
Exp/Cntr=0.3,0.1

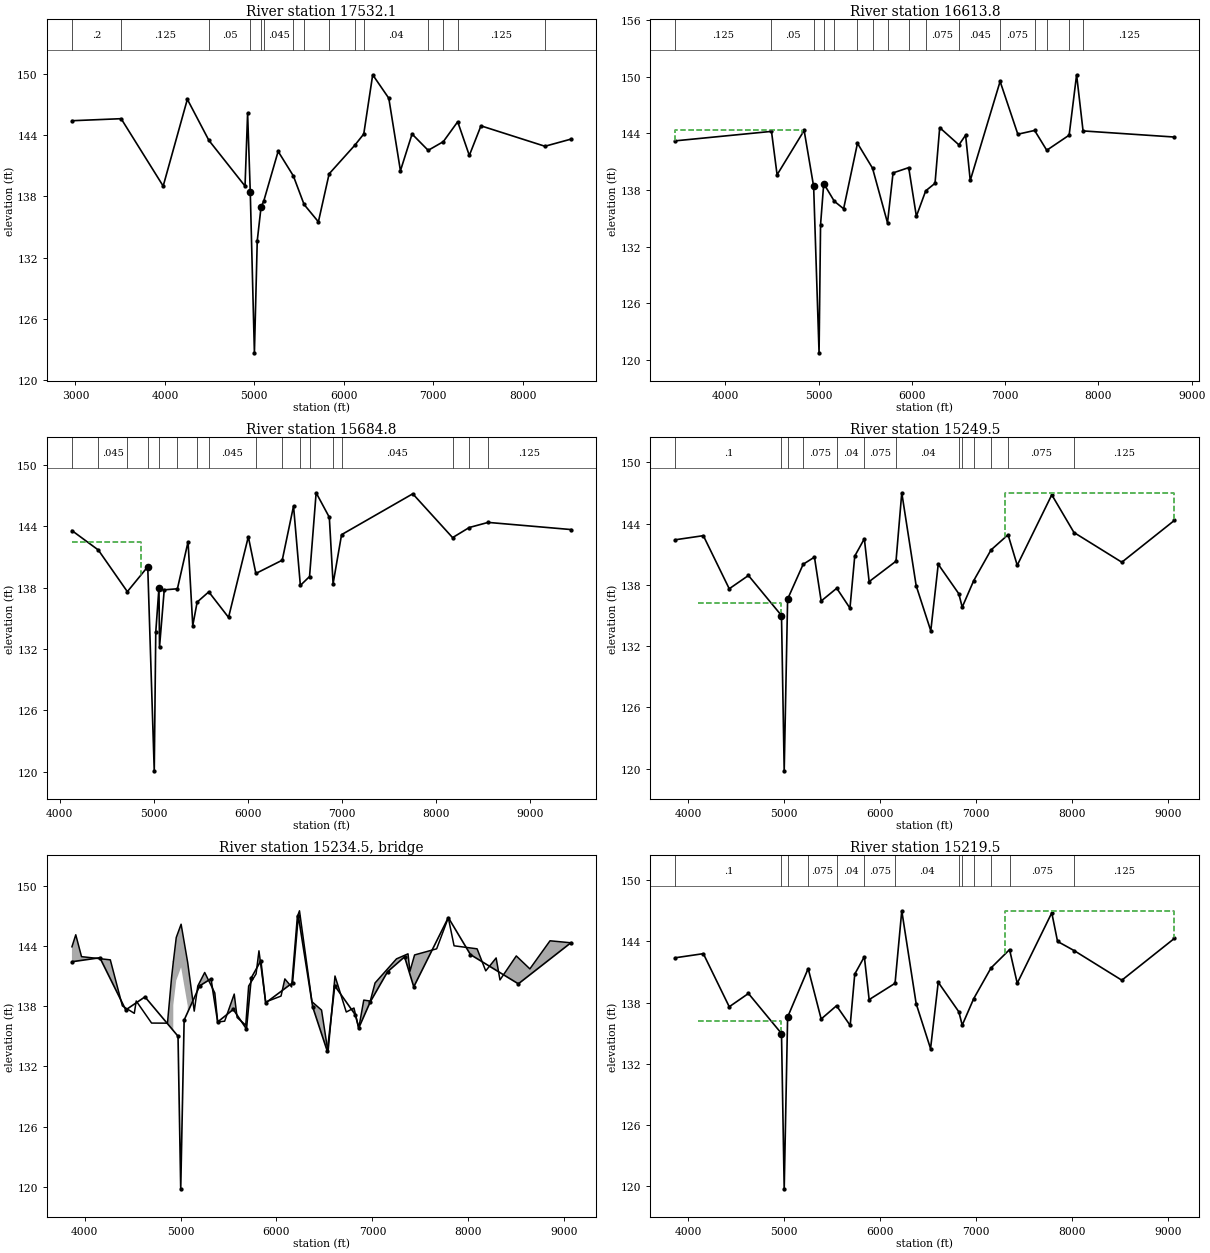
Type RM Length L Ch R = 1 ,17532.1 ,809.1,918.3,578.7
BEGIN DESCRIPTION:
Cross Section XS25
END DESCRIPTION:
XS GIS Cut Line= 5
    3030416.5758   13924526.0643    3029582.2346   13923085.3705
    3029316.3228   13921785.3571    3027900.5467   13919978.9589
    3027720.7929   13919749.6099
#Sta/Elev= 30
  2960.8   145.4  3510.8   145.6  3980.8     139  4250.8   147.5  4491.4  143.48
  4895.6     139  4924.4  146.13 4954.05  138.44  5000.4  122.67  5032.1  133.64
    5075  136.97  5104.2  137.51  5265.6   142.4  5435.6     140  5555.6   137.2
  5715.6   135.5  5835.6   140.2  6122.6     143  6222.6   144.1  6322.6   149.9
  6502.6   147.6  6632.6   140.5  6762.6   144.1  6942.6   142.5  7111.8  143.35
  7272.6   145.3  7402.6     142  7532.6   144.9  8247.7   142.9  8539.1   143.6
#Mann= 15 ,-1 , 0
  2960.8      .2       0  3510.8    .125       0  4491.4     .05       0
 4954.05    .065       0    5075     .12       0  5104.2    .045       0
  5435.6    .075       0  5555.6    .045       0  5835.6    .125       0
  6122.6    .075       0  6222.6     .04       0  6942.6     .03       0
  7111.8     .04       0  7272.6    .125       0  8247.7    .095       0
#XS Ineff= 2 , 0
       0    4250     145    5950       0
Permanent Ineff=
       F       F
Bank Sta=4954.05,5075
XS Rating Curve= 0 ,0
Exp/Cntr=0.3,0.1

Type RM Length L Ch R = 1 ,16613.8 ,1040.3,929,650.7
BEGIN DESCRIPTION:
Cross Section XS24
END DESCRIPTION:
XS GIS Cut Line= 6
    3031255.7678   13924089.4904    3030363.2168   13922949.5475
    3030368.0676   13922794.3213    3029440.4127   13921696.1111
    3028493.4002   13920574.9841    3027950.2636   13919931.9884
#Sta/Elev= 30
    3466   143.2    4496   144.2    4556   139.6    4846   144.3  4947.8  138.37
  5005.9  120.73    5022  134.32    5056  138.67  5169.1   136.8  5269.1     136
  5417.7  142.94  5579.1   140.3  5739.6  134.51  5799.1   139.8  5966.9  140.36
  6049.1   135.2  6149.1   137.9  6249.1   138.7  6299.1   144.6  6505.4  142.77
  6576.7   143.8  6626.7     139  6946.7   149.5  7136.7   143.9  7316.7   144.3
  7446.7   142.2  7686.7   143.8  7766.7   150.2  7835.9  144.25  8815.9   143.6
#Mann= 16 ,-1 , 0
    3466    .125       0    4496     .05       0  4947.8    .065       0
    5056      .1       0  5169.1    .045       0  5417.7    .075       0
  5579.1    .045       0  5739.6    .075       0  5966.9    .045       0
  6149.1    .075       0  6505.4    .045       0  6946.7    .075       0
  7316.7     .04       0  7446.7     .03       0  7686.7     .04       0
  7835.9    .125       0
#XS Ineff= 2 , 0
       0    4820   144.4    6900       0
Permanent Ineff=
       F       F
Bank Sta=4947.8,5056
XS Rating Curve= 0 ,0
Exp/Cntr=0.3,0.1

Type RM Length L Ch R = 1 ,15684.8 ,309.3,435.3,244.6
BEGIN DESCRIPTION:
Cross Section XS23
END DESCRIPTION:
XS GIS Cut Line= 4
    3031849.0178    13923556.455    3030984.2471   13922677.5078
    3029512.2333   13921580.1884    3028071.3166   13919878.0495
#Sta/Elev= 30
  4131.8   143.6  4411.8   141.7  4720.2  137.62  4936.7  140.06  5005.9  120.08
    5022  133.67    5056  138.02  5061.8   132.2  5111.8   137.8  5251.8   137.9
  5364.8   142.5  5414.8   134.3  5461.5   136.6  5584.8   137.6  5794.8   135.1
  6004.8     143  6084.8   139.4  6364.8   140.7  6484.8     146  6557.3  138.23
  6654.8   139.1  6724.8   147.3  6864.8   144.9  6904.8   138.4  6994.8   143.2
  7750.8   147.2  8173.7  142.91  8350.8   143.9  8550.8   144.4    9431   143.7
#Mann= 17 ,-1 , 0
  4131.8    .075       0  4411.8    .045       0  4720.2      .1       0
  4936.7    .065       0    5056      .1       0  5251.8    .045       0
  5461.5    .075       0  5584.8    .045       0  6084.8    .075       0
  6364.8    .045       0  6557.3    .075       0  6654.8    .045       0
  6904.8    .075       0  6994.8    .045       0  8173.7     .04       0
  8350.8    .075       0  8550.8    .125       0
#XS Ineff= 2 , 0
       0    4860   142.5    6800       0
Permanent Ineff=
       F       F
Bank Sta=4936.7,5056
XS Rating Curve= 0 ,0
Exp/Cntr=0.5,0.3

Type RM Length L Ch R = 1 ,15249.5 ,30,30,30
BEGIN DESCRIPTION:
Upstream Section of Bridge/Culvert/Weir
END DESCRIPTION:
XS GIS Cut Line= 5
    3032131.2281   13923544.2167    3031447.2783   13922673.1153
    3031364.6315   13922583.9438    3029587.8565   13921515.3102
    3028420.6187   13920017.7703
#Sta/Elev= 30
  3868.1  142.42  4159.2  142.82  4429.2  137.62  4629.2  138.924973.701     135
5001.899  119.79  5037.5  136.61  5199.6  140.025317.201  140.72  5387.2  136.42
5549.601  137.67  5687.2  135.72  5737.2  140.825837.201  142.52  5887.2  138.32
  6167.2  140.326227.201  147.02  6377.2  137.926529.599   133.5  6607.2  140.02
6821.701  137.136857.199  135.826977.201  138.42  7157.2  141.427334.899  142.91
7430.599  139.927790.599  146.82  8021.7  143.13  8520.6  140.22  9069.3  144.32
#Mann= 13 ,-1 , 0
  3868.1      .1       04973.701    .065       0  5037.5      .1       0
  5199.6    .075       05549.601     .04       05837.201    .075       0
  6167.2     .04       06821.701    .075       06857.199     .04       0
6977.201    .075       0  7157.2     .04       07334.899    .075       0
  8021.7    .125       0
#XS Ineff= 3 ,-1
    4100  4963.7   136.2  5047.55249.999   136.47299.999    9200     147
Permanent Ineff=
       F       F       F
Bank Sta=4973.701,5037.5
XS Rating Curve= 0 ,0
Exp/Cntr=0.5,0.3

Type RM Length L Ch R = 3 ,15234.5 ,,,
BEGIN DESCRIPTION:
GOLF COURSE BRIDGE US LONGWOOD TRACE
Structure ID: L100-00-00-S02A
END DESCRIPTION:
Bridge Culvert--1,0,-1,-1, 0
Deck Dist Width WeirC Skew NumUp NumDn MinLoCord MaxHiCord MaxSubmerge Is_Ogee
10,10,2.6,0, 60, 60, , , 0.95, 0, 1,1,,
  3868.1  3908.1  3968.1  4268.1  4393.7  4518.1  4538.1  4698.1  4863.7  4906.5
4924.3994924.5094924.601  4955.35005.8995075.1015075.189  5142.6  5179.65251.699
  5357.2  5387.2  5459.6  5559.65589.599  5679.65709.6015787.199  5817.2  5887.2
  6047.2  6087.2  6157.2  6217.2  6239.66369.599  6469.66537.1996609.601  6727.2
  6807.26857.199  6909.66977.201  7027.2  7250.6  7370.67390.5997439.1017669.099
7790.599  7850.6  8090.68180.599  8289.1  8329.1  8499.1  8640.6  8850.6  9069.3
  143.91  145.11  142.93  142.61  138.02  137.28  138.51  136.31   136.3  140.84
  142.38  142.38  142.39  144.84  146.16  142.31   142.3   137.5     140  141.35
  139.31  136.41   136.5   139.2  136.86   136.1     140  141.21  143.51  138.41
     139  140.71  139.91  146.91   147.5  138.44   137.6  133.41     141  137.41
  137.81  135.81   138.6   138.5  140.31  142.71  143.21  141.47   143.1  143.71
  146.81  144.01  143.71  141.51   142.8  140.61     143  141.71  144.51  144.31
                                                                                
     136     136   138.1  140.55  141.87  138.02
                                                                                
                                                                                
                                                                                
                                                                                
  3868.1  3908.1  3968.1  4268.1  4393.7  4518.1  4538.1  4698.1  4863.7  4906.5
4924.3994924.5094924.601  4955.35005.8995075.1015075.189  5142.6  5179.65251.699
  5357.2  5387.2  5459.6  5559.65589.599  5679.65709.6015787.199  5817.2  5887.2
  6047.2  6087.2  6157.2  6217.2  6239.66369.599  6469.66537.1996609.601  6727.2
  6807.26857.199  6909.66977.201  7027.2  7250.6  7370.67390.5997439.1017669.099
7790.599  7850.6  8090.68180.599  8289.1  8329.1  8499.1  8640.6  8850.6  9069.3
   143.9  145.11  142.93  142.61  138.02  137.28  138.51  136.31   136.3  140.84
  142.38  142.38  142.39  144.84  146.16  142.31   142.3   137.5     140  141.35
  139.31  136.41   136.5   139.2  136.86   136.1     140  141.21  143.51  138.41
     139  140.71  139.91  146.91   147.5  138.44   137.6  133.41     141  137.41
  137.81  135.81   138.6   138.5  140.31  142.71  143.21  141.47   143.1  143.71
  146.81  144.01  143.71  141.51   142.8   140.6     143  141.71  144.51   144.3
                                                                                
  135.99  135.99  138.09  140.54  141.86  138.01
                                                                                
                                                                                
                                                                                
                                                                                
BR Coef= 1 , 1 , 0 ,1.25, 0 ,,,0.8,0,2,0,
WSPro=,,,, 1 ,,,, 0 ,,,, 0 ,,,,-1 ,-1 ,-1 , 0 , 0 , 0 , 0 , 0
BR U #Sta/Elev= 30
  3868.1  142.42  4159.2  142.82  4429.2  137.62  4629.2  138.924973.701     135
5001.899  119.79  5037.5  136.61  5199.6  140.025317.201  140.72  5387.2  136.42
5549.601  137.67  5687.2  135.72  5737.2  140.825837.201  142.52  5887.2  138.32
  6167.2  140.326227.201  147.02  6377.2  137.926529.599   133.5  6607.2  140.02
6821.701  137.136857.199  135.826977.201  138.42  7157.2  141.427334.899  142.91
7430.599  139.927790.599  146.82  8021.7  143.13  8520.6  140.22  9069.3  144.32
BR U #Mann= 13
  3868.1      .14973.701     .06  5037.5      .1  5199.6    .0755549.601     .04
5837.201    .075  6167.2     .046821.701    .0756857.199     .046977.201    .075
  7157.2     .047334.899    .075  8021.7    .125
BR D #Sta/Elev= 30
  3868.1   142.4  4159.2   142.8  4429.2   137.6  4629.2   138.94973.701  134.98
5001.899  119.77  5037.5  136.595251.699  141.34  5387.2   136.4  5547.2   137.7
  5689.6  135.77  5737.2   140.85837.201   142.5  5887.2   138.3  6157.2   139.9
6227.201     147  6377.2   137.9  6527.2   133.5  6607.2     1406821.701  137.11
6857.199   135.86977.201   138.4  7157.2   141.4  7350.6   143.27430.599   139.9
7790.599   146.8  7850.6     144  8021.7  143.11  8520.6   140.2  9069.3   144.3
BR D #Mann= 13
  3868.1      .14973.701     .06  5037.5      .15251.699    .075  5547.2     .04
5837.201    .075  6157.2     .046821.701    .0756857.199     .046977.201    .075
  7157.2     .04  7350.6    .075  8021.7    .125
BC Design=,, 0 ,, 0 ,,,,,,
BC HTab HWMax=149.92
BC Use User HTab Curves=0
BC User HTab FreeFlow(D)= 0

Type RM Length L Ch R = 1 ,15219.5 ,157.3,81.8,53.1
BEGIN DESCRIPTION:
Downstream Section of Bridge/Culvert/Weir
END DESCRIPTION:
XS GIS Cut Line= 5
    3032176.5993   13923520.0171    3031464.6971   13922655.5645
    3031364.1081      13922545.5    3029643.4164   13921479.5409
    3028490.5114   13919973.5717
#Sta/Elev= 30
  3868.1   142.4  4159.2   142.8  4429.2   137.6  4629.2   138.94973.701  134.98
5001.899  119.77  5037.5  136.595251.699  141.34  5387.2   136.4  5547.2   137.7
  5689.6  135.77  5737.2   140.85837.201   142.5  5887.2   138.3  6157.2   139.9
6227.201     147  6377.2   137.9  6527.2   133.5  6607.2     1406821.701  137.11
6857.199   135.86977.201   138.4  7157.2   141.4  7350.6   143.27430.599   139.9
7790.599   146.8  7850.6     144  8021.7  143.11  8520.6   140.2  9069.3   144.3
#Mann= 13 ,-1 , 0
  3868.1      .1       04973.701    .065       0  5037.5      .1       0
5251.699    .075       0  5547.2     .04       05837.201    .075       0
  6157.2     .04       06821.701    .075       06857.199     .04       0
6977.201    .075       0  7157.2     .04       0  7350.6    .075       0
  8021.7    .125       0
#XS Ineff= 3 ,-1
    4100  4963.7   136.2  5047.55249.999   136.47299.999    9200     147
Permanent Ineff=
       F       F       F
Bank Sta=4973.701,5037.5
XS Rating Curve= 0 ,0
Exp/Cntr=0.5,0.3

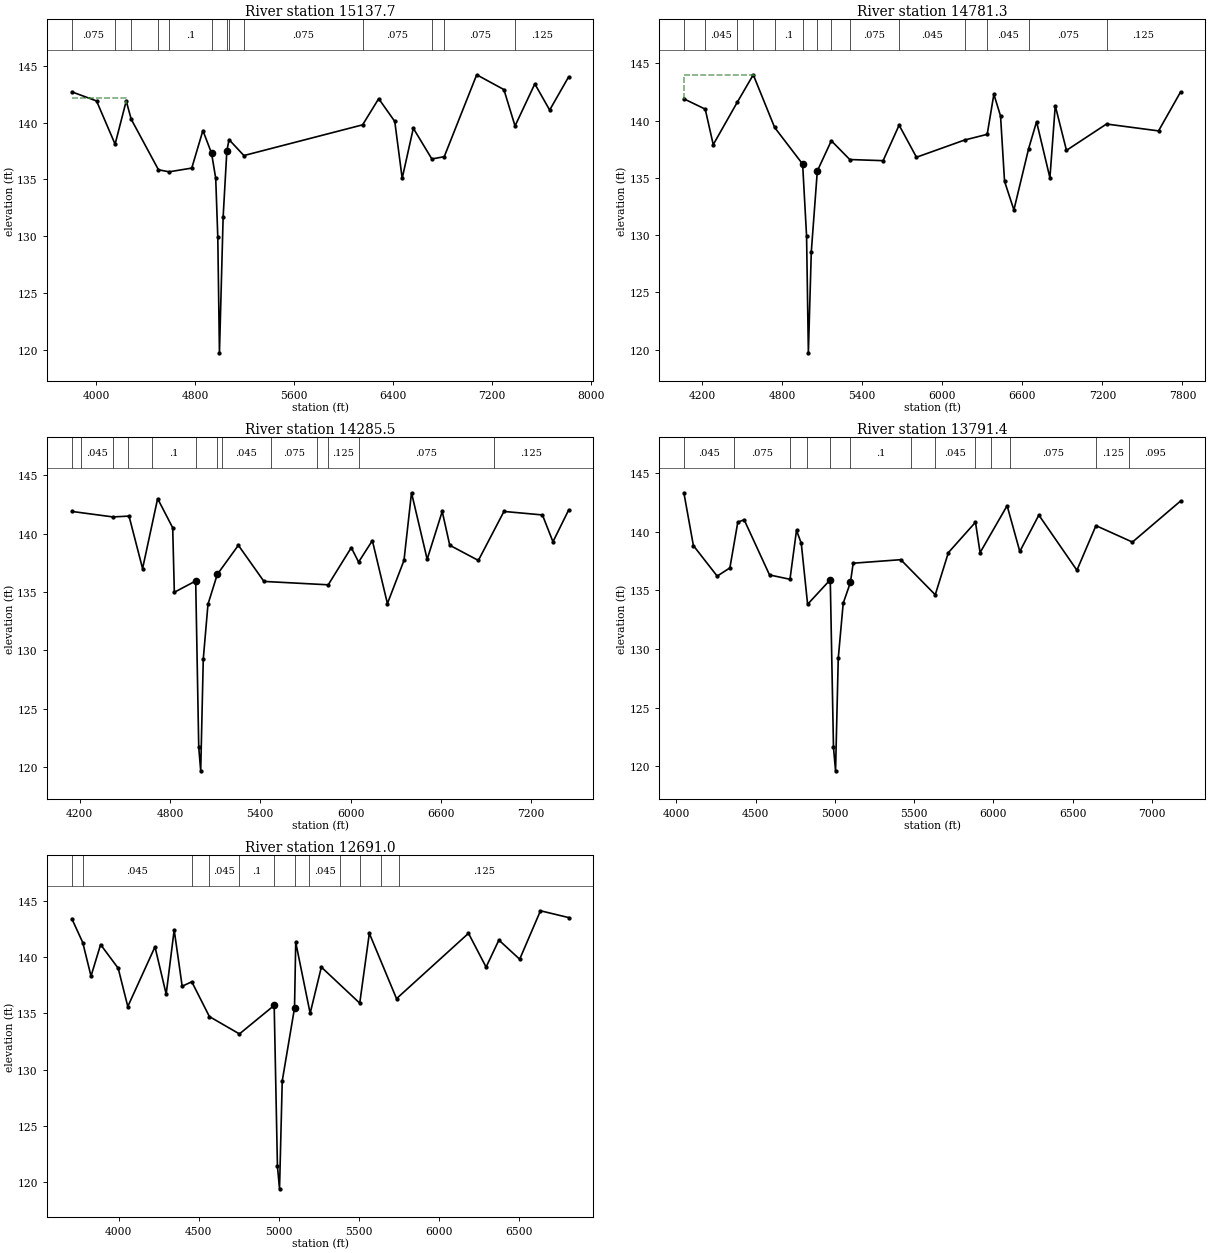
Type RM Length L Ch R = 1 ,15137.7 ,422,356.4,255
BEGIN DESCRIPTION:
Cross Section XS22
END DESCRIPTION:
XS GIS Cut Line= 5
    3032373.5509   13923265.8354    3031487.5153   13922542.8304
    3031367.0145   13922500.3007    3029746.2381   13921447.7646
    3029274.4681   13920786.2348
#Sta/Elev= 30
  3803.5   142.7  4003.5   141.9  4153.5   138.1  4243.5   141.9  4283.5   140.3
  4504.1  135.85    4591  135.67  4773.5     136  4863.5   139.3  4933.5   137.3
  4967.1   135.1  4983.8  129.96  4997.3  119.76  5027.1   131.7  5057.1   137.5
  5074.9   138.5  5194.9   137.1  6154.9   139.8  6284.9   142.1  6414.9   140.1
  6474.9   135.1  6564.9   139.5  6714.9   136.8  6814.9     137  7077.4   144.2
  7297.4   142.9  7387.4   139.7  7547.4   143.4  7667.4   141.1  7819.9     144
#Mann= 13 ,-1 , 0
  3803.5    .075       0  4153.5    .045       0  4283.5    .075       0
  4504.1    .045       0    4591      .1       0  4933.5    .065       0
  5057.1      .1       0  5074.9    .045       0  5194.9    .075       0
  6154.9    .075       0  6714.9    .045       0  6814.9    .075       0
  7387.4    .125       0
#XS Ineff= 2 , 0
       0    4238   142.2    7080       0
Permanent Ineff=
       F       F
Bank Sta=4933.5,5057.1
XS Rating Curve= 0 ,0
Exp/Cntr=0.3,0.1

Type RM Length L Ch R = 1 ,14781.3 ,495.8,495.8,360
BEGIN DESCRIPTION:
Cross Section XS21
END DESCRIPTION:
XS GIS Cut Line= 6
    3032572.0228   13922578.2718     3031728.517   13922294.7404
     3031579.663    13922259.299    3030003.1453   13921445.7934
    3029714.4339   13921100.6242    3029422.4951   13920751.5963
#Sta/Elev= 30
  4064.4   141.9  4224.4     141  4284.4   137.9  4464.4   141.6  4584.4     144
  4744.4   139.4  4954.3   136.2  4983.8  129.92  4997.3  119.72  5019.1  128.52
  5064.3   135.6  5169.4  138.24  5307.3   136.6  5557.3   136.5  5677.3   139.6
  5807.3   136.8  6167.3   138.3  6337.3   138.8  6387.3   142.3  6437.3   140.4
  6467.3   134.7  6537.3   132.2    6648  137.56  6707.3   139.9  6807.3     135
  6847.3   141.3  6931.3   137.4  7231.3   139.7  7621.3   139.1  7786.4   142.5
#Mann= 14 ,-1 , 0
  4064.4    .125       0  4224.4    .045       0  4464.4    .075       0
  4584.4    .045       0  4744.4      .1       0  4954.3    .065       0
  5064.3      .1       0  5169.4    .045       0  5307.3    .075       0
  5677.3    .045       0  6167.3    .075       0  6337.3    .045       0
    6648    .075       0  7231.3    .125       0
#XS Ineff= 2 , 0
       0    4590     144               0
Permanent Ineff=
       F       F
Bank Sta=4954.3,5064.3
XS Rating Curve= 0 ,0
Exp/Cntr=0.3,0.1

Type RM Length L Ch R = 1 ,14285.5 ,404.2,494.1,412.1
BEGIN DESCRIPTION:
Cross Section XS20
END DESCRIPTION:
XS GIS Cut Line= 6
    3032387.7274   13922089.1802    3031650.5458   13921826.9136
    3031487.5153   13921812.7371    3030257.2342   13921351.1548
    3029723.0282   13920816.9385    3029522.6748   13920616.5812
#Sta/Elev= 30
  4148.4   141.9  4420.9  141.43  4528.4   141.5  4618.4     137  4718.4     143
  4818.4   140.5  4829.3  134.97  4971.1  135.94  4991.4  121.67  5004.5  119.66
  5021.5  129.24  5052.7  133.94  5114.5   136.5  5254.5     139  5424.5   135.9
  5851.4  135.61  6004.5   138.8  6053.1  137.56  6144.5   139.4  6244.5     134
  6354.5   137.7  6404.5   143.5  6508.5   137.8  6608.5   141.9  6658.5     139
  6848.5   137.7  7018.5   141.9    7274   141.6    7344   139.3  7447.3     142
#Mann= 13 ,-1 , 0
  4148.4    .125       0    4208    .045       0  4420.9    .075       0
  4520.4    .045       0  4683.1      .1       0  4971.1    .065       0
  5114.5      .1       0  5145.3    .045       0    5470    .075       0
  5776.4    .035       0  5851.4    .125       0  6053.1    .075       0
    6951    .125       0
Bank Sta=4971.1,5114.5
XS Rating Curve= 0 ,0
Exp/Cntr=0.3,0.1

Type RM Length L Ch R = 1 ,13791.4 ,406.7,1100.4,950.5
BEGIN DESCRIPTION:
Cross Section XS19
END DESCRIPTION:
XS GIS Cut Line= 5
    3032288.4914   13921968.6793    3031661.3932   13921355.1415
    3030542.0078   13921089.7423    3029931.1441   13920470.0787
     3029767.357   13920303.9322
#Sta/Elev= 30
  4048.3   143.3  4108.3   138.8  4258.3   136.2  4338.3   136.9  4388.3   140.8
  4428.3     141  4588.3   136.3  4717.2  135.93  4758.3   140.1  4788.3     139
  4828.3   133.8  4971.1  135.89  4991.4  121.62  5004.5  119.61  5021.5  129.19
  5052.7  133.89  5098.2  135.66  5115.6   137.3  5415.6   137.6    5633  134.61
  5715.6   138.2  5886.5  140.79  5915.6   138.2    6086   142.2    6166   138.3
    6286   141.4    6526   136.7    6646   140.5    6876   139.1  7179.5   142.6
#Mann= 13 ,-1 , 0
  4048.3    .045       0  4365.3    .075       0  4717.2    .045       0
  4822.2      .1       0  4971.1    .065       0  5098.2      .1       0
  5478.2    .035       0    5633    .045       0  5886.5    .075       0
  5983.5    .125       0  6102.3    .075       0  6648.8    .125       0
  6857.3    .095       0
Bank Sta=4971.1,5098.2
XS Rating Curve= 0 ,0
Exp/Cntr=0.3,0.1

Type RM Length L Ch R = 1 ,12691.0 ,302.1,390.8,413.8
BEGIN DESCRIPTION:
Cross Section XS18
END DESCRIPTION:
XS GIS Cut Line= 3
    3032260.1383   13921869.4433    3031636.3693   13920593.5522
    3030609.5782    13919257.068
#Sta/Elev= 30
  3705.8   143.4  3774.2  141.28  3825.8   138.3  3885.8   141.1  3995.8     139
  4055.8   135.6  4225.8   140.9  4295.8   136.7  4345.8   142.4  4395.8   137.4
  4455.8   137.8    4566  134.71  4753.8  133.17  4971.1   135.7  4991.4  121.43
  5004.5  119.42  5021.5     129  5098.2  135.47  5105.8   141.3    5196     135
    5266   139.1    5506   135.9    5566   142.1    5736   136.3    6186   142.1
    6296   139.1    6376   141.5    6506   139.8    6636   144.1  6811.4   143.5
#Mann= 12 ,-1 , 0
  3705.8    .125       0  3774.2    .045       0  4455.8    .075       0
    4566    .045       0  4753.8      .1       0  4971.1    .065       0
  5098.2      .1       0  5187.4    .045       0  5385.2    .075       0
  5504.9     .04       0  5641.9    .075       0  5752.4    .125       0
Bank Sta=4971.1,5098.2
XS Rating Curve= 0 ,0
Exp/Cntr=0.3,0.1