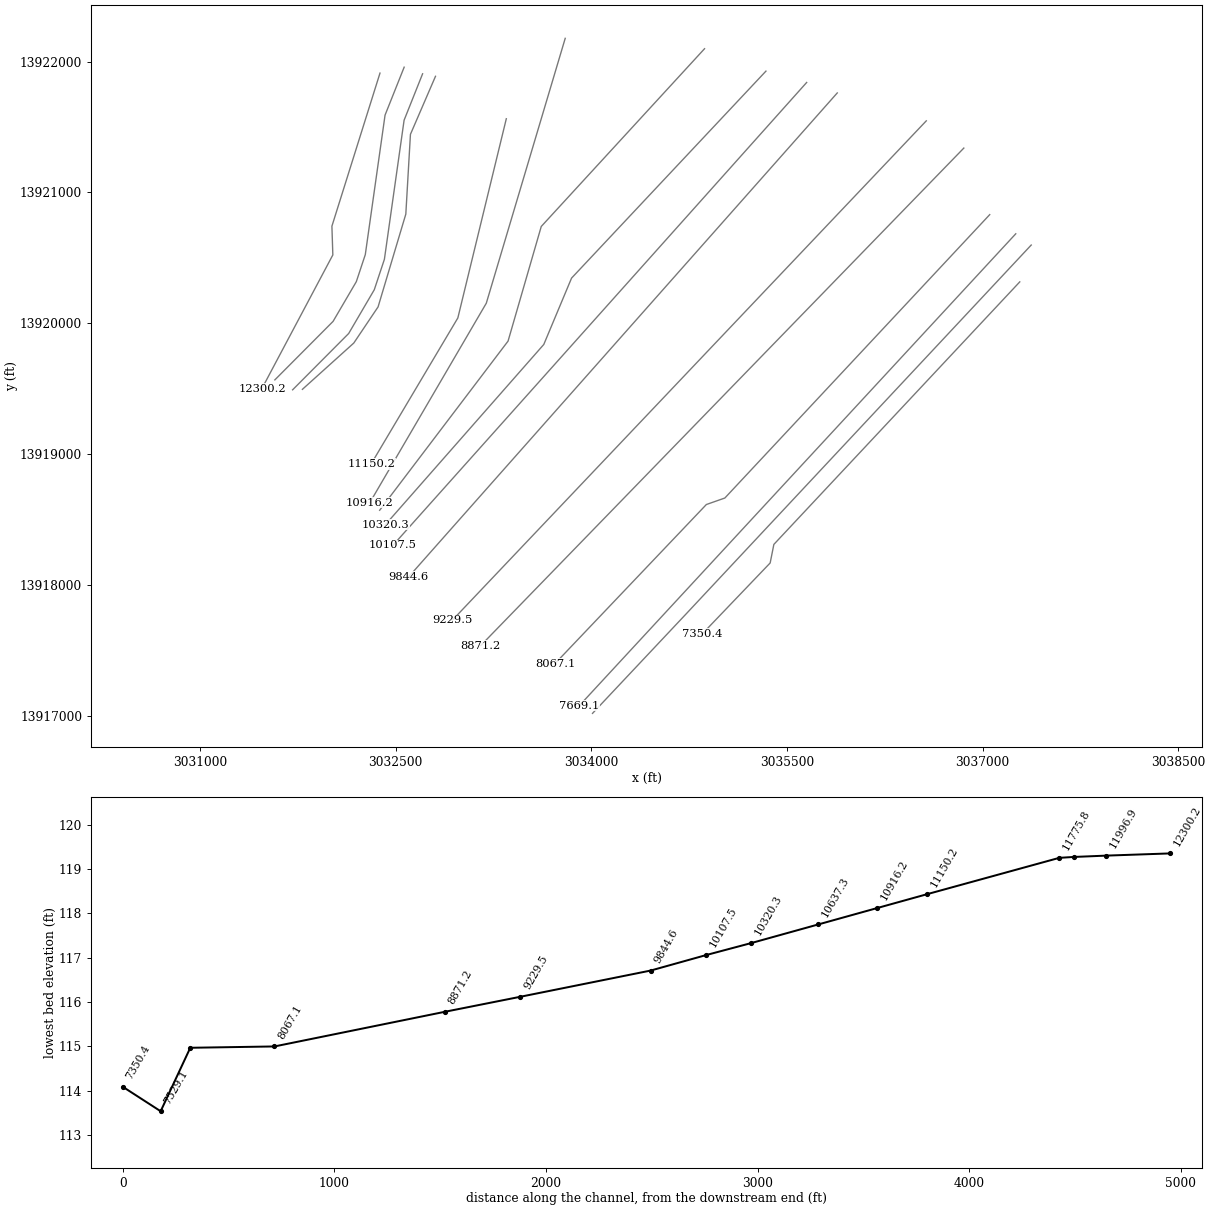
HEC-RAS study L100-00-00.prj: L100-00-00

--- L100-00-00.g01 (geometry) --- (continued)

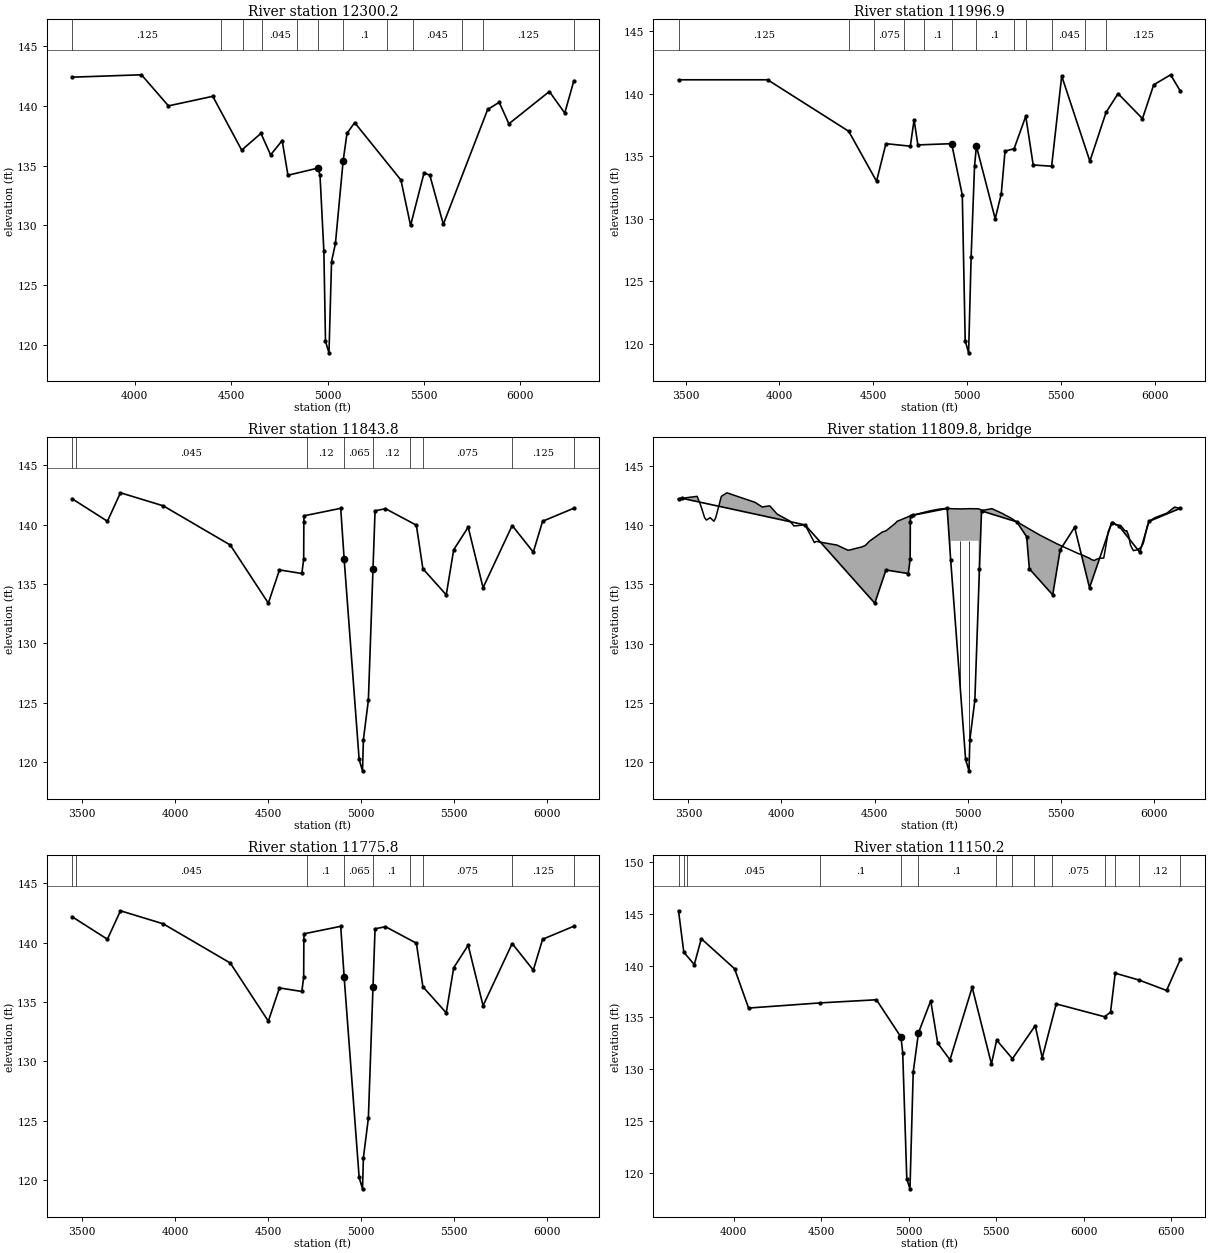
Type RM Length L Ch R = 1 ,12300.2 ,277.3,303.3,251
BEGIN DESCRIPTION:
Cross Section XS17
END DESCRIPTION:
XS GIS Cut Line= 4
    3032380.6391   13921911.9731    3032012.0484   13920742.4061
    3032019.1366   13920522.6693    3031475.1657   13919501.3488
#Sta/Elev= 30
  3674.7   142.4  4034.7   142.6  4174.7     140  4404.7   140.8  4554.7   136.3
  4654.7   137.7  4704.7   135.9  4764.7   137.1  4794.7   134.2    4951   134.8
    4961   134.2    4981  127.88  4989.5  120.31  5007.6  119.35  5020.9  126.98
    5041   128.5    5081   135.4    5101   137.7  5140.8   138.6  5380.8   133.8
  5430.8     130  5500.8   134.4  5530.8   134.2  5600.8   130.1  5830.8   139.7
  5890.8   140.3  5940.8   138.5  6150.8   141.2  6230.8   139.4    6278   142.1
#Mann= 12 ,-1 , 0
  3674.7    .125       0  4447.9    .045       0  4563.5    .075       0
  4661.1    .045       0  4843.1      .1       0    4951    .065       0
    5081      .1       0  5306.4    .045       0  5444.6    .045       0
  5695.7    .075       0    5805    .125       0    6278      .2       0
Bank Sta=4951,5081
XS Rating Curve= 0 ,0
Exp/Cntr=0.3,0.1

Type RM Length L Ch R = 1 ,11996.9 ,150.8,153.1,151.9
BEGIN DESCRIPTION:
Cross Section US Longwood Trace_Con
END DESCRIPTION:
XS GIS Cut Line= 6
      3032566.02   13921957.2806     3032419.525   13921591.0327
     3032267.998   13920525.0295    3032199.2326    13920318.573
    3032021.0427    13920015.098    3031574.6811   13919568.1333
#Sta/Elev= 30
  3462.8   141.1  3937.3   141.1  4369.1  136.99  4517.3     133  4567.3     136
  4697.3   135.8  4717.3   137.9  4737.3   135.9  4917.3     136    4974   131.9
  4989.5  120.26  5007.6   119.3    5021  126.93  5039.2   134.2  5049.2   135.8
  5149.2     130  5181.6     132  5201.6   135.4    5250   135.6    5312  138.19
  5351.6   134.3  5449.8   134.2  5503.5   141.4  5653.5   134.6  5739.4  138.49
  5803.5     140  5933.5     138  5993.5   140.7  6083.5   141.5  6135.2   140.2
#Mann= 12 ,-1 , 0
  3462.8    .125       0  4369.1    .045       0  4504.9    .075       0
  4663.3    .045       0  4768.1      .1       0  4917.3    .065       0
  5049.2      .1       0    5250    .045       0    5312    .075       0
  5449.8    .045       0  5629.5    .075       0  5739.4    .125       0
Bank Sta=4917.3,5049.2
XS Rating Curve= 0 ,0
Exp/Cntr=0.5,0.3

Type RM Length L Ch R = 1 ,11843.8 ,68,68,68
BEGIN DESCRIPTION:
Upstream Section of Bridge/Culvert/Weir
END DESCRIPTION:
XS GIS Cut Line= 6
    3032707.3383   13921906.6786    3032565.4943   13921552.0684
     3032414.419   13920489.2432    3032336.9777   13920256.9194
    3032140.7033    13919922.645    3031710.7797   13919492.1405
#Sta/Elev= 30
  3446.9   142.2  3636.9   140.3  3706.9   142.7  3936.9   141.6  4296.9   138.3
  4501.5   133.4  4561.5   136.2  4681.5   135.9  4691.5   137.1  4692.4  140.24
  4693.5  140.76  4890.5  141.39  4909.1  137.08  4989.5  120.23  5007.6  119.27
  5012.4   121.9  5039.1  125.22    5064  136.31    5075  141.18  5131.1  141.36
    5297  139.97    5332   136.3  5457.6   134.1  5497.6   137.9  5575.4   139.8
  5655.4   134.7  5811.9  139.94  5925.4   137.7  5975.4   140.3  6143.3   141.4
#Mann= 9 ,-1 , 0
  3446.9      .2       0    3467    .045       0    4708     .12       0
  4909.1    .065       0    5064     .12       0  5264.3    .045       0
    5332    .075       0  5811.9    .125       0  6143.3      .2       0
#XS Ineff= 2 , 0
       0    4890   137.7    5075       0     137
Permanent Ineff=
       F       F
Bank Sta=4909.1,5064
XS Rating Curve= 0 ,0
Exp/Cntr=0.5,0.3

Type RM Length L Ch R = 3 ,11809.8 ,,,
BEGIN DESCRIPTION:
LONGWOOD TRACE
Structure ID: L100-00-00-S2
END DESCRIPTION:
Bridge Culvert--1,0,-1,-1, 0
Deck Dist Width WeirC Skew NumUp NumDn MinLoCord MaxHiCord MaxSubmerge Is_Ogee
10,48,2.6,0, 161, 161, , , 0.95, 0, 1,1,,
  3446.9    3467    3507    3527  3546.9  3566.9    3577  3586.9    3587  3596.9
  3616.9  3636.9  3646.9    3657    3667  3676.9    3687  3706.9    3707    3727
    3757  3856.9    3857    3867    3877  3896.9    3897    3907  3930.5  3936.9
  3960.5  3976.9  4020.5  4046.9  4066.9  4110.5  4120.5  4126.9  4176.9  4186.9
  4256.9  4280.5  4296.9  4356.9  4361.5  4370.5  4411.5  4431.5  4451.5  4461.5
  4470.5  4471.5  4481.5  4491.5  4501.5  4521.5  4531.5  4541.1  4541.5  4551.5
  4561.5  4611.5  4621.1  4693.5    4708  4739.8  4740.1  4799.1  4799.5  4846.4
  4846.6  4888.9  4890.5  4909.1  4959.1  4960.6    4988  4988.9  4989.5  5000.4
  5007.6  5008.8  5010.5  5011.1  5012.4  5039.1  5058.6 5058.69  5058.8  5058.9
    5059    5064  5068.9    5075    5079  5131.1  5133.6  5186.9  5190.6  5201.1
  5231.1  5251.1  5381.2  5387.6  5417.6  5457.6  5467.6  5477.6  5481.2  5595.4
  5605.4  5611.2  5655.4  5665.4  5681.6  5691.6  5711.6  5715.4  5725.4  5731.6
  5741.6  5755.4  5775.4  5785.4  5795.4  5801.6  5811.6  5811.9  5821.6  5825.4
  5831.6  5841.6  5845.4  5851.6  5855.4  5861.6  5865.4  5871.6  5875.4  5881.6
  5885.4  5891.6  5911.6  5915.4  5925.4  5931.6  5941.6  5945.4  5961.6  5965.4
  5975.4  6001.6  6006.6  6011.6  6021.6  6031.6  6051.6  6061.6  6071.6  6111.6
  6143.3
   142.2  142.25  142.33  142.37  142.41  141.61   141.1  140.61  140.61  140.41
  140.61  140.31  140.61  141.22  141.82  142.41  142.51  142.71  142.71   142.6
  142.44  141.91  141.91  141.81  141.71  141.51  141.51  141.54  141.59  141.61
   141.2  140.91  140.54  140.31  139.91  139.98     140  140.01  138.51  138.61
  138.41  138.35  138.31  137.87  137.88   137.9  138.07  138.14  138.28  138.45
   138.6  138.61  138.72  138.84  138.95  139.18  139.29   139.4   139.4  139.45
   139.5  140.13   140.3  140.77  140.83  140.96  140.96  141.19  141.19  141.33
  141.33   141.4   141.4  141.37  141.35  141.35  141.36  141.36  141.36  141.37
  141.37  141.37  141.37  141.37  141.37  141.36  141.36  141.36  141.36  141.36
  141.36  141.33  141.29  141.25  141.22  141.37  141.35  140.97  140.94  140.84
   140.6  140.39   139.2  139.15  138.91  138.59  138.51  138.43   138.4  137.58
  137.53   137.5  137.19  137.08     137   137.1   137.2   137.2   137.2   137.2
  138.08  139.41  140.21  140.21  140.01  139.99  139.96  139.95  139.92  139.91
  139.79  139.59  139.51  139.51  139.51  139.26  139.11  138.61  138.31   138.1
  137.99  137.83   137.9  137.94  138.04   138.1  138.36  138.51  139.64  139.91
  140.31  140.56  140.61  140.64   140.7  140.76  140.87  140.93     141   141.5
   141.4
                                                                                
                                                                                
                                                                                
                                                                                
                                                                                
                                                                                
                                                                                
                          138.65  138.65  138.65  138.66  138.66  138.66  138.67
  138.67  138.67  138.67  138.67  138.67  138.66  138.66  138.66  134.01  134.06
   134.1
                                                                                
                                                                                
                                                                                
                                                                                
                                                                                
                                                                                
        
  3446.9    3467    3507    3527  3546.9  3566.9    3577  3586.9    3587  3596.9
  3616.9  3636.9  3646.9    3657    3667  3676.9    3687  3706.9    3707    3727
    3757  3856.9    3857    3867    3877  3896.9    3897    3907  3930.5  3936.9
  3960.5  3976.9  4020.5  4046.9  4066.9  4110.5  4120.5  4126.9  4176.9  4186.9
  4256.9  4280.5  4296.9  4356.9  4361.5  4370.5  4411.5  4431.5  4451.5  4461.5
  4470.5  4471.5  4481.5  4491.5  4501.5  4521.5  4531.5  4541.1  4541.5  4551.5
  4561.5  4611.5  4621.1  4693.5    4708  4739.8  4740.1  4799.1  4799.5  4846.4
  4846.6  4888.9  4890.5  4909.1  4959.1  4960.6    4988  4988.9  4989.5  5000.4
  5007.6  5008.8  5010.5  5011.1  5012.4  5039.1  5058.6 5058.69  5058.8  5058.9
    5059    5064  5068.9    5075    5079  5131.1  5133.6  5186.9  5190.6  5201.1
  5231.1  5251.1  5381.2  5387.6  5417.6  5457.6  5467.6  5477.6  5481.2  5595.4
  5605.4  5611.2  5655.4  5665.4  5681.6  5691.6  5711.6  5715.4  5725.4  5731.6
  5741.6  5755.4  5775.4  5785.4  5795.4  5801.6  5811.6  5811.9  5821.6  5825.4
  5831.6  5841.6  5845.4  5851.6  5855.4  5861.6  5865.4  5871.6  5875.4  5881.6
  5885.4  5891.6  5911.6  5915.4  5925.4  5931.6  5941.6  5945.4  5961.6  5965.4
  5975.4  6001.6  6006.6  6011.6  6021.6  6031.6  6051.6  6061.6  6071.6  6111.6
  6143.3
   142.2  142.25  142.33  142.37  142.41  141.61   141.1  140.61  140.61  140.41
  140.61  140.31  140.61  141.22  141.82  142.41  142.51  142.71  142.71   142.6
  142.44  141.91  141.91  141.81  141.71  141.51  141.51  141.54  141.59  141.61
   141.2  140.91  140.54  140.31  139.91  139.98     140  140.01  138.51  138.61
  138.41  138.35  138.31  137.87  137.88   137.9  138.07  138.14  138.28  138.45
   138.6  138.61  138.72  138.84  138.95  139.18  139.29   139.4   139.4  139.45
   139.5  140.13   140.3  140.77  140.83  140.96  140.96  141.19  141.19  141.33
  141.33   141.4   141.4  141.37  141.35  141.35  141.36  141.36  141.36  141.37
  141.37  141.37  141.37  141.37  141.37  141.36  141.36  141.36  141.36  141.36
  141.36  141.33  141.29  141.25  141.22  141.37  141.35  140.97  140.94  140.84
   140.6  140.39   139.2  139.15  138.91  138.59  138.51  138.43   138.4  137.58
  137.53   137.5  137.19  137.08     137   137.1   137.2   137.2   137.2   137.2
  138.08  139.41  140.21  140.21  140.01  139.99  139.96  139.95  139.92  139.91
  139.79  139.59  139.51  139.51  139.51  139.26  139.11  138.61  138.31   138.1
  137.99  137.83   137.9  137.94  138.04   138.1  138.36  138.51  139.64  139.91
  140.31  140.56  140.61  140.64   140.7  140.76  140.87  140.93     141   141.5
   141.4
                                                                                
                                                                                
                                                                                
                                                                                
                                                                                
                                                                                
                                                                                
                          138.64  138.64  138.64  138.65  138.65  138.65  138.66
  138.66  138.66  138.66  138.66  138.66  138.65  138.65  138.65     134  134.05
  134.09
                                                                                
                                                                                
                                                                                
                                                                                
                                                                                
                                                                                
        
Pier Skew, UpSta & Num, DnSta & Num=  ,4960.6, 2 ,4960.6, 2 , 0 , 0 , 0 ,,
     1.3     1.3
  124.64  139.65
     1.3     1.3
  124.63  139.64
Pier Skew, UpSta & Num, DnSta & Num=  ,5007.6, 2 ,5007.6, 2 , 0 , 0 , 0 ,,
     1.3     1.3
  118.28  139.67
     1.3     1.3
  118.27  139.66
BR Coef= 1 , 1 , 1 ,1.25, 0 ,,,0.8,0,2,0,
WSPro=,,,, 1 ,,,, 0 ,,,, 0 ,,,,-1 ,-1 ,-1 , 0 , 0 , 0 , 0 , 0
BR U #Sta/Elev= 30
  3446.9   142.2    3467  142.24  4126.9     140  4501.5   133.4  4561.5   136.2
  4681.5   135.9  4691.5   137.1  4692.4  140.24  4693.5  140.76    4708  140.82
  4890.5  141.39  4909.1  137.08  4989.5  120.23  5007.6  119.27  5012.4   121.9
  5039.1  125.22    5064  136.31    5075  141.18  5264.3  140.26  5317.6     139
    5332   136.3  5457.6   134.1  5497.6   137.9  5575.4   139.8  5655.4   134.7
  5775.4   140.2  5811.9  139.94  5925.4   137.7  5975.4   140.3  6143.3   141.4
BR U #Mann= 8
  3446.9      .2    3467    .045    4708     .12  4909.1     .06    5064      .1
  5264.3    .045    5332    .075  5811.9    .125
BR U Banks=,5064
BR D #Sta/Elev= 30
  3446.9  142.18    3467  142.22  4126.9  139.98  4501.5  133.38  4561.5  136.18
  4681.5  135.88  4691.5  137.08  4692.4  140.22  4693.5  140.74    4708   140.8
  4890.5  141.37  4909.1  137.06  4989.5  120.21  5007.6  119.25  5012.4  121.88
  5039.1   125.2    5064  136.29    5075  141.16  5264.3  140.24  5317.6  138.98
    5332  136.28  5457.6  134.08  5497.6  137.88  5575.4  139.78  5655.4  134.68
  5775.4  140.18  5811.9  139.92  5925.4  137.68  5975.4  140.28  6143.3  141.38
BR D #Mann= 8
  3446.9      .2    3467    .045    4708      .1  4909.1     .06    5064      .1
  5264.3    .045    5332    .075  5811.9    .125
BR D Banks=,5064
BC Design=,, 0 ,, 0 ,,,,,,
BC HTab HWMax=142.7
BC Use User HTab Curves=0
BC User HTab FreeFlow(D)= 0

Type RM Length L Ch R = 1 ,11775.8 ,580.2,625.6,574.5
BEGIN DESCRIPTION:
Downstream Section of Bridge/Culvert/Weir
END DESCRIPTION:
XS GIS Cut Line= 6
     3032806.199   13921887.4274    3032614.1105   13921444.1463
     3032578.669   13920834.5538    3032366.0205   13920125.7254
    3032179.8753   13919849.6624    3031785.8973   13919495.8703
#Sta/Elev= 30
  3446.9  142.18  3636.9  140.28  3706.9  142.68  3936.9  141.58  4296.9  138.28
  4501.5  133.38  4561.5  136.18  4681.5  135.88  4691.5  137.08  4692.4  140.22
  4693.5  140.74  4890.5  141.37  4909.1  137.06  4989.5  120.21  5007.6  119.25
  5012.4  121.88  5039.1   125.2    5064  136.29    5075  141.16  5131.1  141.34
    5297  139.95    5332  136.28  5457.6  134.08  5497.6  137.88  5575.4  139.78
  5655.4  134.68  5811.9  139.92  5925.4  137.68  5975.4  140.28  6143.3  141.38
#Mann= 9 ,-1 , 0
  3446.9      .2       0    3467    .045       0    4708      .1       0
  4909.1    .065       0    5064      .1       0  5264.3    .045       0
    5332    .075       0  5811.9    .125       0  6143.3      .2       0
#XS Ineff= 2 , 0
       0    4898   137.7    5068       0     137
Permanent Ineff=
       F       F
Bank Sta=4909.1,5064
XS Rating Curve= 0 ,0
Exp/Cntr=0.5,0.3

Type RM Length L Ch R = 1 ,11150.2 ,203.6,234,134.1
BEGIN DESCRIPTION:
Cross Section US Longwood Trace_Exp
END DESCRIPTION:
XS GIS Cut Line= 3
      3033349.11    13921563.281    3032977.5457    13920041.287
    3032312.6454   13918925.7322
#Sta/Elev= 30
  3686.1   145.3  3716.1   141.3  3776.1   140.1  3816.1   142.6  4006.1   139.7
  4086.1   135.9  4496.1   136.4  4816.1   136.7  4956.1   133.1  4966.1   131.6
  4989.5  119.39  5007.6  118.43  5026.1   129.7  5056.1   133.5  5126.1   136.6
  5166.1   132.5  5236.1   130.9  5362.8   137.9  5472.8   130.5  5502.8   132.8
  5592.8     131  5722.8   134.2  5762.8   131.1  5842.8   136.3  6118.9  135.06
  6152.8   135.5  6179.7  139.27  6316.5   138.6  6472.8   137.6  6551.4   140.6
#Mann= 14 ,-1 , 0
  3686.1    .045       0  3716.6     .08       0  3734.6    .045       0
  4496.1      .1       0  4956.1    .065       0  5056.1      .1       0
  5499.8    .045       0  5588.2    .075       0  5715.6    .045       0
  5816.9    .075       0  6118.9    .045       0  6179.7    .075       0
  6316.5     .12       0  6551.4      .2       0
Bank Sta=4956.1,5056.1
XS Rating Curve= 0 ,0
Exp/Cntr=0.3,0.1

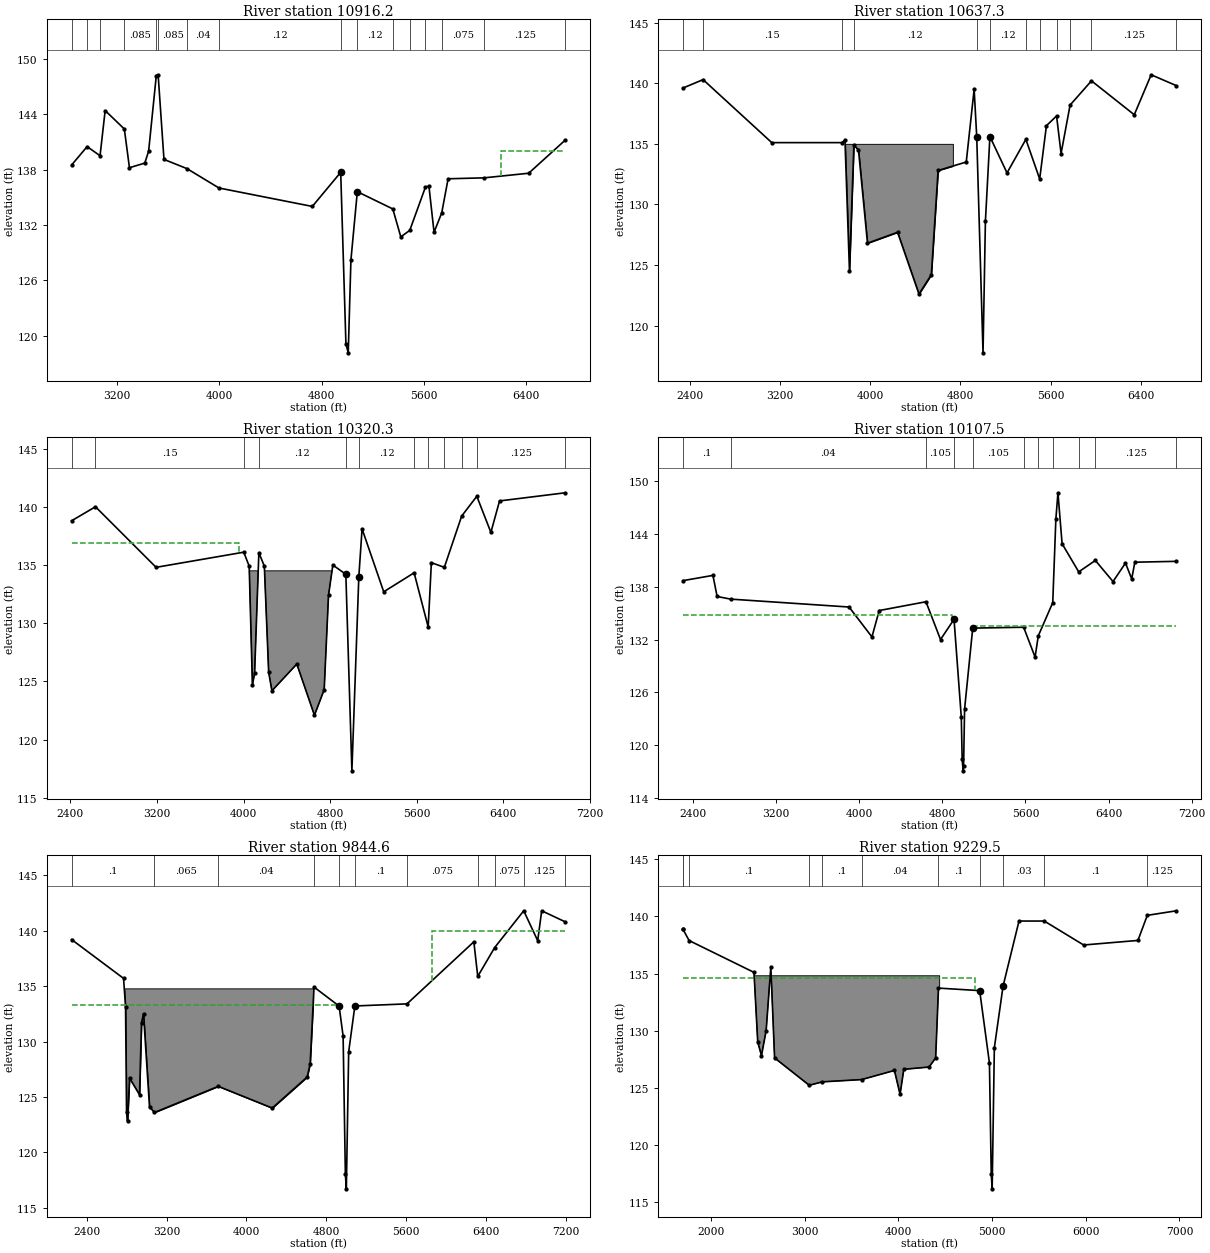
Type RM Length L Ch R = 1 ,10916.2 ,239.3,278.9,277.9
BEGIN DESCRIPTION:
Cross Section XS15
END DESCRIPTION:
XS GIS Cut Line= 3
    3033800.7067   13922177.5473    3033195.7918   13920154.0785
     3032302.668   13918630.0974
#Sta/Elev= 30
 2844.68   138.5  2965.7  140.49  3066.6   139.5  3106.6   144.4  3256.6   142.4
  3296.6   138.2  3416.6   138.7  3446.6     140  3506.6   148.2  3520.9  148.28
  3566.6   139.1  3746.6   138.1  3996.6     136  4726.6     134  4948.6   137.7
  4989.5  119.08  5007.6  118.12  5028.6   128.2  5078.6   135.6    5356  133.73
  5418.6   130.7  5488.6   131.4  5611.6  136.11  5638.6   136.2  5678.6   131.2
  5738.6   133.3  5788.6     137  6068.6   137.1  6418.6   137.6    6705   141.2
#Mann= 16 ,-1 , 0
 2844.68    .125       0  2965.7    .085       0  3066.6     .04       0
  3256.6    .085       0  3506.6     .04       0  3520.9    .085       0
  3746.6     .04       0  3996.6     .12       0  4948.6    .065       0
  5078.6     .12       0    5356    .045       0  5488.6    .075       0
  5611.6    .045       0  5738.6    .075       0  6068.6    .125       0
    6705      .2       0
#XS Ineff= 2 , 0
       0                    6200       0     140
Permanent Ineff=
       F       F
Bank Sta=4948.6,5078.6
XS Rating Curve= 0 ,0
Exp/Cntr=0.3,0.1

Type RM Length L Ch R = 1 ,10637.3 ,362.5,317,228.6
BEGIN DESCRIPTION:
Cross Section XS14.67
END DESCRIPTION:
XS GIS Cut Line= 4
      3034868.89   13922098.2864    3033616.9879   13920740.2183
    3033362.5156   13919864.3987    3032378.2355   13918571.9963
#Sta/Elev= 30
  2334.8   139.6  2514.8   140.3  3124.8   135.1  3744.8   135.1  3774.8   135.3
  3814.8   124.5  3853.9  134.88  3894.8   134.5  3974.8   126.8  4241.9   127.7
  4431.9   122.6  4541.9   124.2  4601.9   132.8  4851.9   133.5  4921.9   139.5
 4944.92  135.58  5000.8  117.75  5021.9   128.6  5061.9   135.6  5213.9   132.6
  5381.2  135.37  5503.9   132.1  5563.9   136.5  5653.9   137.3  5693.9   134.2
  5773.9   138.2  5963.9   140.2  6343.9   137.4  6493.9   140.7  6718.4   139.8
#Mann= 12 ,-1 , 0
  2334.8    .125       0  2514.8     .15       0  3744.8     .04       0
  3853.9     .12       0 4944.92    .065       0  5061.9     .12       0
  5381.2    .045       0  5503.9    .075       0  5653.9    .045       0
  5773.9    .075       0  5963.9    .125       0  6718.4      .2       0
#Block Obstruct= 2 , 0
       0    4733     135               0
Bank Sta=4944.92,5061.9
XS Rating Curve= 0 ,0
Exp/Cntr=0.3,0.1

Type RM Length L Ch R = 1 ,10320.3 ,466.2,212.8,178.7
BEGIN DESCRIPTION:
Cross Section XS14.33
END DESCRIPTION:
XS GIS Cut Line= 4
      3035339.63   13921927.1073    3033849.3381   13920345.7633
    3033636.4022   13919838.7219    3032421.0303   13918460.7298
#Sta/Elev= 30
    2412   138.8    2632     140    3192   134.8    4002   136.1    4052   134.9
    4082   124.7    4102   125.7  4141.4  136.06    4192   134.9    4232   125.8
    4262   124.2    4492   126.5  4654.9   122.1  4744.9   124.3  4784.9   132.4
  4824.9     135  4944.9   134.2  5000.8  117.33  5064.9     134  5094.9   138.1
  5294.9   132.7  5575.6  134.33  5705.6  129.68  5734.9   135.2  5854.9   134.8
  6014.9   139.2  6154.9   140.9  6284.9   137.8  6364.9   140.5  6972.3   141.2
#Mann= 12 ,-1 , 0
    2412    .125       0    2632     .15       0    4002     .04       0
  4141.4     .12       0  4944.9    .065       0  5064.9     .12       0
  5575.6    .045       0  5705.6    .075       0  5854.9    .045       0
  6014.9    .075       0  6154.9    .125       0  6972.3      .2       0
#XS Ineff= 2 , 0
       0    3959   136.9               0
Permanent Ineff=
       F       F
#Block Obstruct= 2 , 0
       0    4825   134.5               0
Bank Sta=4944.9,5064.9
XS Rating Curve= 0 ,0
Exp/Cntr=0.3,0.1

Type RM Length L Ch R = 1 ,10107.5 ,259.2,262.9,270.3
BEGIN DESCRIPTION:
Cross Section XS14
END DESCRIPTION:
XS GIS Cut Line= 2
    3035651.6946   13921840.3839    3032479.8751   13918304.0363
#Sta/Elev= 30
  2302.7   138.7  2592.7   139.3  2632.7   136.9  2762.7   136.6  3902.7   135.7
  4122.7   132.3  4192.7   135.3  4642.7   136.3  4782.7     132  4912.7   134.3
  4982.7  123.16    4991  118.38  5000.8  117.06  5004.7   117.6  5014.3  124.09
  5092.7   133.3  5582.7   133.4  5692.7     130  5723.6  132.42  5862.7   136.2
  5892.7   145.7  5912.7   148.7  5952.7   142.9  6112.7   139.7  6272.7     141
  6442.7   138.6  6562.7   140.7  6622.7   138.9  6652.7   140.8  7053.1   140.9
#Mann= 11 ,-1 , 0
  2302.7      .1       0  2762.7     .04       0  4642.7    .105       0
  4912.7    .065       0  5092.7    .105       0  5582.7    .045       0
  5723.6    .075       0  5862.7    .045       0  6112.7    .075       0
  6272.7    .125       0  7053.1      .2       0
#XS Ineff= 2 , 0
       0  4892.5   134.8    5103       0   133.5
Permanent Ineff=
       F       F
Bank Sta=4912.7,5092.7
XS Rating Curve= 0 ,0
Exp/Cntr=0.3,0.1

Type RM Length L Ch R = 1 ,9844.6  ,598.3,615.1,556.5
BEGIN DESCRIPTION:
Cross Section XS13 **Note**
A blocked obstruction was used in lieu of a permanent ineffective flow area due to the flow area cacluation error in RAS version 3.01.
END DESCRIPTION:
XS GIS Cut Line= 2
    3035886.2999   13921760.4049     3032600.376   13918063.0347
#Sta/Elev= 30
  2248.3   139.2  2768.3   135.7  2788.3   133.1  2798.3   123.6  2808.3   122.8
  2828.3   126.7  2928.3   125.2  2948.3   131.7  2968.3   132.5  3028.3   124.1
  3078.3   123.6  3717.5  125.96  4258.3     124  4608.3   126.8  4638.3     128
  4676.8  134.92  4928.3   133.2  4968.3   130.5    4991  118.03  5000.8  116.71
  5024.2  129.08 5086.13  133.21  5608.3   133.4  6278.3     139  6317.6  135.88
    6487  138.48  6778.3   141.8  6918.3   139.1  6958.3   141.8  7194.8   140.8
#Mann= 11 ,-1 , 0
  2248.3      .1       0  3078.3    .065       0  3717.5     .04       0
  4676.8      .1       0  4928.3    .065       0 5086.13      .1       0
  5608.3    .075       0  6317.6    .045       0    6487    .075       0
  6778.3    .125       0  7194.8      .2       0
#XS Ineff= 2 , 0
       0    4918   133.3    5858       0     140
Permanent Ineff=
       F       F
#Block Obstruct= 2 , 0
       0    4668   134.8               0
Bank Sta=4928.3,5086.13
XS Rating Curve= 0 ,0
Exp/Cntr=0.3,0.1

Type RM Length L Ch R = 1 ,9229.5  ,331.2,358.3,360.4
BEGIN DESCRIPTION:
Cross Section XS12 **Note**
A blocked obstruction was used in lieu of a permanent ineffective flow area due to the flow area cacluation error in RAS version 3.01.
END DESCRIPTION:
XS GIS Cut Line= 2
     3036568.788   13921547.1273    3032933.5253   13917729.8853
#Sta/Elev= 30
  1697.4   138.9  1697.5   138.9  1764.7  137.89  2457.4   135.1  2497.4     129
  2537.4   127.8  2587.4     130  2637.4   135.6  2677.4   127.6  3047.4   125.2
  3187.4   125.5  3607.4   125.7  3957.4   126.5  4017.4   124.4  4057.4   126.6
  4327.4   126.8  4397.4   127.6  4427.6  133.72  4867.4   133.5  4971.6  127.16
    4991  117.44  5000.8  116.12  5024.2  128.49  5117.4   133.9  5287.4   139.6
  5557.4   139.6  5977.4   137.5  6557.4   137.9  6657.4   140.1  6968.7   140.5
#Mann= 11 ,-1 , 0
  1697.4      .2       0  1697.5    .125       0  1764.7      .1       0
  3047.4     .04       0  3187.4      .1       0  3607.4     .04       0
  4427.6      .1       0  4867.4    .065       0  5117.4     .03       0
  5557.4      .1       0  6657.4    .125       0
#XS Ineff= 2 , 0
       0    4818   134.6               0
Permanent Ineff=
       F       F
#Block Obstruct= 2 , 0
       0    4440   134.8               0
Bank Sta=4867.4,5117.4
XS Rating Curve= 0 ,0
Exp/Cntr=0.3,0.1

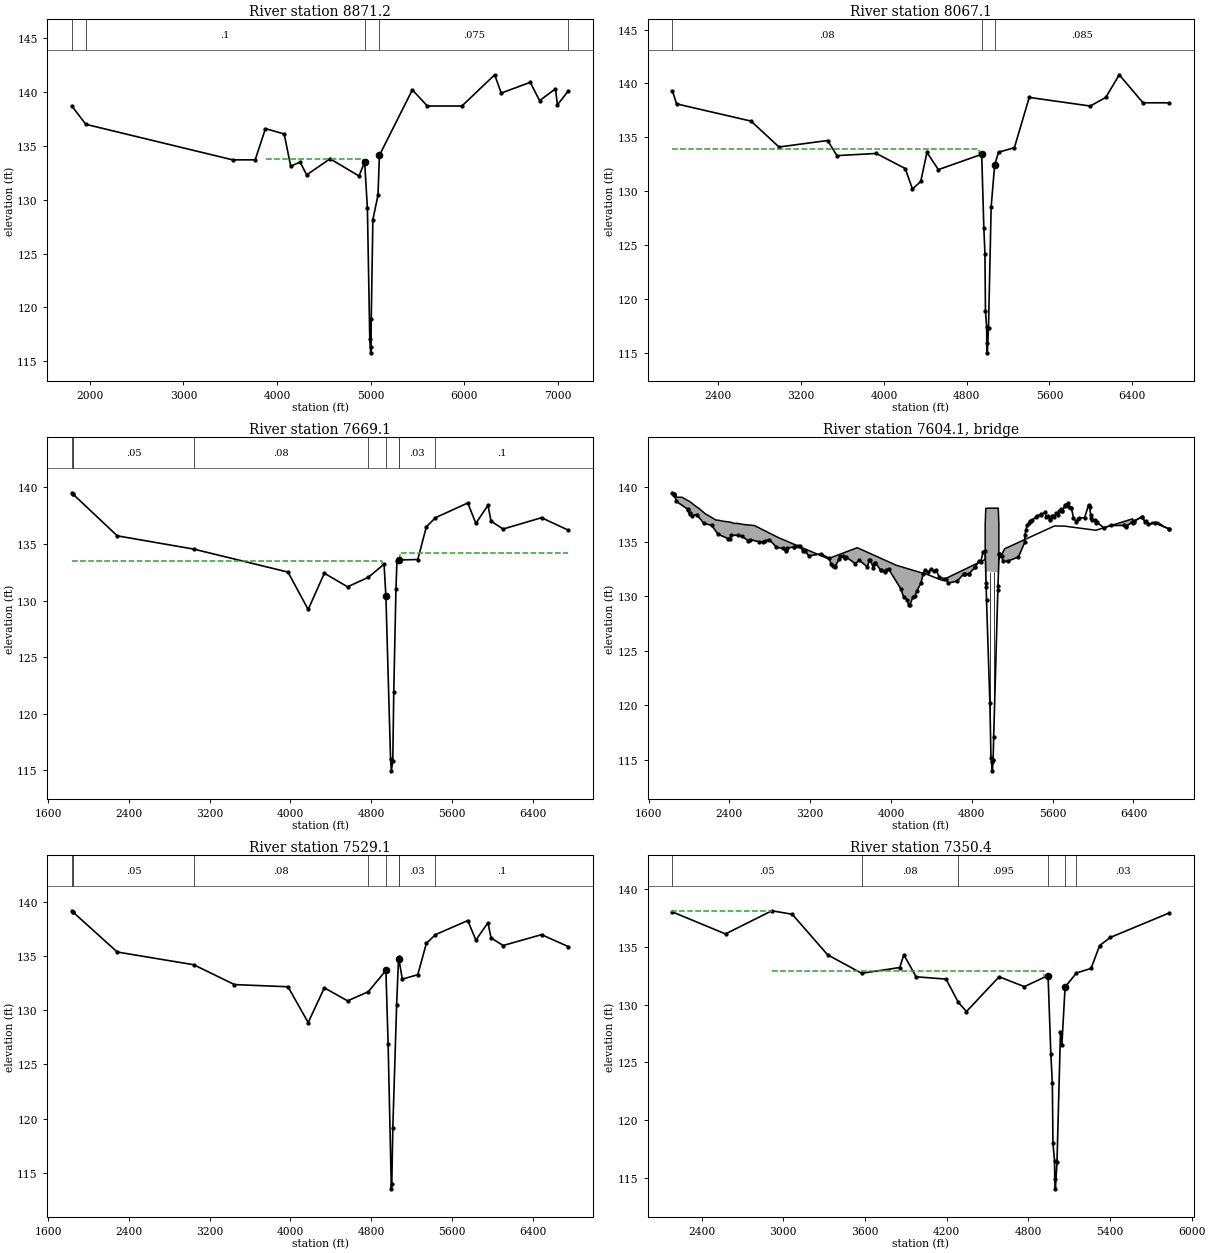
Type RM Length L Ch R = 1 ,8871.2  ,563.5,804.1,636.1
BEGIN DESCRIPTION:
Cross Section XS11
END DESCRIPTION:
XS GIS Cut Line= 2
    3036856.7126   13921339.1817    3033153.2621   13917538.5016
#Sta/Elev= 30
  1806.2   138.7  1956.2     137  3526.2   133.7  3766.2   133.7  3876.2   136.6
  4076.2   136.1  4146.2   133.1  4246.2   133.5  4316.2   132.3  4566.2   133.8
  4876.2   132.2  4936.2   133.5  4965.8  129.21    4991   117.1  5000.8  115.78
  5004.7  116.32  5006.8  118.88  5024.2  128.15  5078.8  130.41  5094.2  134.12
  5446.2   140.2  5606.2   138.7  5976.2   138.7  6326.2   141.6  6396.2   139.9
  6706.2   140.9  6806.2   139.2  6976.2   140.3  6996.2   138.8  7112.9   140.1
#Mann= 5 ,-1 , 0
  1806.2    .125       0  1956.2      .1       0  4936.2    .065       0
  5094.2    .075       0  7112.9      .2       0
#XS Ineff= 2 ,-1
    1800    3885   134.9    3885    4920   133.8
Permanent Ineff=
       F       F
Bank Sta=4936.2,5094.2
XS Rating Curve= 0 ,0
Exp/Cntr=0.3,0.1

Type RM Length L Ch R = 1 ,8067.1  ,278.8,398,346.8
BEGIN DESCRIPTION:
Cross Section XS10
END DESCRIPTION:
XS GIS Cut Line= 4
    3037055.1358   13920830.5924    3035024.5692   13918665.5388
    3034882.8035   13918615.9208    3033722.6578    13917400.857
#Sta/Elev= 30
  1955.7   139.3  1995.7   138.1  2715.7   136.5  2985.7   134.1  3455.7   134.7
  3545.7   133.3  3925.7   133.5  4205.7   132.1  4275.7   130.2  4355.7   130.9
  4415.7   133.6  4525.7     132    4945  133.42  4965.5  126.62  4976.4  124.15
  4981.1  118.92  4992.5  117.42  4994.3  115.88  4998.9     115  5010.6   117.3
  5036.3  128.56    5070  132.42  5107.6  133.62  5260.7  134.03  5404.2   138.7
  5994.2   137.9  6144.2   138.7  6274.2   140.8  6504.2   138.2  6754.2   138.2
#Mann= 3 ,-1 , 0
  1955.7     .08       0    4945    .065       0    5070    .085       0
#XS Ineff= 2 , 0
       0    4915   133.9               0
Permanent Ineff=
       F       F
Bank Sta=4945,5070
XS Rating Curve= 0 ,0
Exp/Cntr=0.5,0.3

Type RM Length L Ch R = 1 ,7669.1  ,140,140,140
BEGIN DESCRIPTION:
Upstream Section of Bridge/Culvert/Weir; updated with survey
END DESCRIPTION:
XS GIS Cut Line= 2
     3037254.768     13920684.27     3033909.716      13917080.1
#Sta/Elev= 30
  1835.7  139.51  1848.4  139.38  1848.9  139.38  2285.7  135.71    3042  134.54
  3975.7  132.51  4175.7  129.21  4335.7  132.41  4565.7  131.21  4770.9  132.05
  4926.7  133.21    4945   130.4  4991.2  116.03  4998.9  114.97  5013.2  115.81
    5023  121.94  5044.6     131  5054.4  133.45    5070  133.57  5070.6  133.58
  5260.7  133.62  5345.7  136.51  5435.7  137.31  5755.7  138.61  5835.7  136.81
  5955.7  138.41  5985.7  137.01  6105.7  136.31  6485.7  137.31  6750.6  136.21
#Mann= 9 ,-1 , 0
  1835.7      .2       0  1848.4    .065       0  1848.9     .05       0
    3042     .08       0  4770.9    .095       0    4945     .08       0
    5070    .095       0  5070.6     .03       0  5435.7      .1       0
#XS Ineff= 2 , 0
       0    4911   133.5    5081       0   134.2
Permanent Ineff=
       F       F
#Block Obstruct= 2 , 0
       0                    6000       0     137
Bank Sta=4945,5070
XS Rating Curve= 0 ,0
Exp/Cntr=0.5,0.3

Type RM Length L Ch R = 3 ,7604.1  ,,,
BEGIN DESCRIPTION:
KLUGE RD; Top of road defined from September 2013 survey
END DESCRIPTION:
Bridge Culvert--1,0,-1,-1, 0
Deck Dist Width WeirC Skew NumUp NumDn MinLoCord MaxHiCord MaxSubmerge Is_Ogee
25,76,2.6,0, 74, 74, , , 0.95, 0, 1,1,,
  1835.7  1848.4  1848.9  1855.7  1858.4  1875.7  1888.4  1928.4  1948.4  1985.7
  1988.4  2005.7  2008.4  2025.7  2048.4  2108.4  2145.7  2158.4  2268.4  2285.7
  2338.4  2405.7  2415.7  2435.7  2448.4  2478.4  2485.7  2525.7  2538.4  2585.7
  2605.7  2648.4 2883.95 3376.85 3665.65 4051.05 4367.75 4504.25  4931.9  4931.9
  4937.7 4938.76  4981.1  5022.5  5060.5  5060.5 5061.56 5067.36 5067.36 5125.95
 5616.85 5717.65 6027.65 6391.25  6395.7  6402.4  6405.7  6422.4  6482.4  6485.7
  6492.4  6515.7  6525.7  6532.4  6545.7  6552.4  6572.4  6582.4  6602.4  6615.7
  6642.4  6702.4  6750.5  6750.6
   139.5  139.37  139.37   139.3  139.23  139.14   139.1   139.1     139  138.81
   138.8  138.71   138.7  138.57   138.4     138   137.7   137.6     137     137
   136.9  136.82  136.79  136.74   136.7   136.7  136.69  136.62   136.6  136.56
  136.54   136.5   135.4  133.46  134.47  132.86  131.98  131.48  133.39  136.57
  138.06  138.08   138.1   138.1   138.1   138.1   138.1  136.58  133.39  134.38
  136.46  136.45  136.07  137.12   136.9   136.9  136.91  136.99  137.29  137.31
   137.2   136.8  136.91   136.8  136.73   136.7  136.65   136.8   136.8   136.8
   136.8   136.4   136.2   136.2
                                                                                
                                                                                
                                                                                
                                                                       0       0
  132.28  132.28  132.28  132.22  132.22       0       0       0       0
                                                                                
                                                                                
                                
  1835.7  1848.4  1848.9  1855.7  1858.4  1875.7  1888.4  1928.4  1948.4  1985.7
  1988.4  2005.7  2008.4  2025.7  2048.4  2108.4  2145.7  2158.4  2268.4  2285.7
  2338.4  2405.7  2415.7  2435.7  2448.4  2478.4  2485.7  2525.7  2538.4  2585.7
  2605.7  2648.4 2883.95 3376.85 3665.65 4051.05 4367.75 4504.25  4931.9  4931.9
  4937.7 4938.76  4981.1  5022.5  5060.5  5060.5 5061.56 5067.36 5067.36 5125.95
 5616.85 5717.65 6027.65 6391.25  6395.7  6402.4  6405.7  6422.4  6482.4  6485.7
  6492.4  6515.7  6525.7  6532.4  6545.7  6552.4  6572.4  6582.4  6602.4  6615.7
  6642.4  6702.4  6750.5  6750.6
   139.5  139.37  139.37   139.3  139.23  139.14   139.1   139.1     139  138.81
   138.8  138.71   138.7  138.57   138.4     138   137.7   137.6     137     137
   136.9  136.82  136.79  136.74   136.7   136.7  136.69  136.62   136.6  136.56
  136.54   136.5   135.4  133.46  134.47  132.86  131.98  131.48  133.39  136.57
  138.06  138.08   138.1   138.1   138.1   138.1   138.1  136.58  133.39  134.38
  136.46  136.45  136.07  137.12   136.9   136.9  136.91  136.99  137.29  137.31
   137.2   136.8  136.91   136.8  136.73   136.7  136.65   136.8   136.8   136.8
   136.8   136.4   136.2   136.2
                                                                                
                                                                                
                                                                                
                                                                       0       0
  132.28  132.28  132.28  132.22  132.22       0       0       0       0
                                                                                
                                                                                
                                
Pier Skew, UpSta & Num, DnSta & Num=  ,4981.1, 2 ,4981.1, 2 , 0 , 0 , 0 ,,
     1.3     1.3
  117.41  133.26
     1.3     1.3
  117.08  132.93
Pier Skew, UpSta & Num, DnSta & Num=  ,5022.5, 2 ,5022.5, 2 , 0 , 0 , 0 ,,
     1.3     1.3
  120.71  133.27
     1.3     1.3
  120.38  132.94
BR Coef= 1 , 1 , 1 ,1.25, 0 ,,,0.8,0,2,0,
WSPro=,,,, 1 ,,,, 0 ,,,, 0 ,,,,-1 ,-1 ,-1 , 0 , 0 , 0 , 0 , 0
BR U #Sta/Elev= 177
  1835.7  139.51  1848.4  139.38  1848.9  139.38  1855.7  139.31  1875.7  138.71
  1985.7  138.01  1988.4  137.96  2005.7  137.61  2008.4  137.58  2025.7  137.41
  2075.7  137.51  2145.7  136.71  2225.7  136.51  2285.7  135.71  2385.7  135.31
  2405.7  135.31  2415.7  135.61  2485.7  135.61  2525.7  135.51  2585.7  135.11
  2605.7  135.21  2695.7  135.01  2735.7  135.01  2755.7  135.11  2795.7  135.21
  2865.7  134.51  2925.7  134.41  2955.7  134.21  2958.4  134.26  2965.7  134.41
  3038.4  134.54    3042  134.54  3075.7  134.61  3095.7  134.61  3125.7  134.21
  3145.7  134.21  3185.7  133.71  3305.7  133.91  3385.7  133.51  3405.7  133.01
  3425.7  132.81  3445.7  132.71  3448.4  132.76  3485.7  133.41  3495.7  133.71
  3525.7  133.71  3545.7  133.51  3548.4  133.54  3555.7  133.61  3645.7  133.01
  3685.7  133.31  3765.7  132.71  3785.7  133.31  3795.7  133.31  3825.7  132.61
  3835.7  133.01  3838.4  133.04  3845.7  133.11  3895.7  132.41  3898.4   132.4
  3935.7  132.21  3945.7  132.41  3975.7  132.51  4095.7  130.71  4125.7  129.91
  4155.7  129.71  4175.7  129.21  4185.7  129.21  4215.7  129.91  4235.7  130.01
  4255.7  130.51  4295.7  131.21  4315.7  132.01  4335.7  132.41  4365.7  132.21
  4395.7  132.51  4425.7  132.31  4445.7  132.41  4475.7  131.81  4525.7  131.61
  4545.7  131.61  4565.7  131.21  4655.7  131.41  4718.4  132.04    4720  132.06
  4734.5  132.06  4770.9  132.05  4772.6  132.07  4832.3  132.69  4832.5  132.69
  4872.5  133.27  4887.7  133.17  4912.4  134.12  4931.9  134.18 4940.75   131.2
 4940.98  130.83    4945  129.69 4978.51  120.19 4989.05  115.21 4995.32  114.82
 5003.28  113.99 5009.17  115.01 5010.39     115 5015.92  117.08 5056.42  130.58
 5058.22  130.94 5069.22  133.87    5070  133.87  5070.6  133.86 5094.22  133.74
  5107.6  133.21  5154.6  133.23  5260.7  133.62  5323.3  134.95    5324   135.6
  5335.7  136.11  5345.7  136.51  5365.7  136.71  5375.7  136.91  5385.7  136.91
  5399.7  137.02  5435.7  137.31  5445.7  137.41  5485.7  137.51  5488.4  137.52
  5525.7  137.71  5535.7  137.31  5555.7  137.41  5575.7  137.01  5578.4  137.06
  5595.7  137.41  5598.4   137.4  5615.7  137.31  5635.7  137.61  5655.7  137.51
  5665.7  137.81  5685.7  138.01  5692.4  137.88  5695.7  137.81  5722.4  138.34
  5725.7  138.41  5735.7  138.41  5755.7  138.61  5765.7  138.21  5782.4  138.13
  5785.7  138.11  5805.7  137.21  5835.7  136.81  5852.4  137.14  5855.7  137.21
  5915.7  137.21  5955.7  138.41  5962.4  138.28  5965.7  138.21  5975.7  137.51
  5982.4  137.18  5985.7  137.01  6015.7  137.01  6025.7  136.71  6035.7  136.81
  6105.7  136.31  6175.7  136.51  6305.7  136.51  6322.4  136.43  6325.7  136.41
  6385.7  136.81  6395.7  136.71  6402.4  136.84  6405.7  136.91  6482.4  137.29
  6485.7  137.31  6515.7  136.81  6525.7  136.91  6545.7  136.61  6615.7  136.71
  6750.5  136.21  6750.6  136.21
BR U #Mann= 9
  1835.7      .2  1848.4    .065  1848.9     .05    3042     .08  4734.5     .03
    4945    .025    5070     .03  5070.6     .03  5399.7      .1
BR D #Sta/Elev= 176
  1835.7  139.16  1848.4  139.03  1848.9  139.03  1855.7  138.96  1875.7  138.36
  1985.7  137.66  1988.4  137.61  2005.7  137.26  2008.4  137.23  2025.7  137.06
  2075.7  137.16  2145.7  136.36  2225.7  136.16  2285.7  135.36  2385.7  134.96
  2405.7  134.96  2415.7  135.26  2485.7  135.26  2525.7  135.16  2585.7  134.76
  2605.7  134.86  2695.7  134.66  2735.7  134.66  2755.7  134.76  2795.7  134.86
  2865.7  134.16  2925.7  134.06  2955.7  133.86  2958.4  133.91  2965.7  134.06
  3038.4  134.19    3042  134.19  3075.7  134.26  3095.7  134.26  3125.7  133.86
  3145.7  133.86  3185.7  133.36  3305.7  133.56  3385.7  133.16  3405.7  132.66
  3425.7  132.46  3445.7  132.36  3448.4  132.41  3485.7  133.06  3495.7  133.36
  3525.7  133.36  3545.7  133.16  3548.4  133.19  3555.7  133.26  3645.7  132.66
  3685.7  132.96  3765.7  132.36  3785.7  132.96  3795.7  132.96  3825.7  132.26
  3835.7  132.66  3838.4  132.69  3845.7  132.76  3895.7  132.06  3898.4  132.05
  3935.7  131.86  3945.7  132.06  3975.7  132.16  4095.7  130.36  4125.7  129.56
  4155.7  129.36  4175.7  128.86  4185.7  128.86  4215.7  129.56  4235.7  129.66
  4255.7  130.16  4295.7  130.86  4315.7  131.66  4335.7  132.06  4365.7  131.86
  4395.7  132.16  4425.7  131.96  4445.7  132.06  4475.7  131.46  4525.7  131.26
  4545.7  131.26  4565.7  130.86  4655.7  131.06  4718.4  131.69    4720  131.71
  4770.9   131.7  4772.6  131.72  4832.3  132.34  4832.5  132.34  4872.5  132.92
 4918.91  134.29 4935.18  134.58 4944.36  131.34 4944.43  130.98    4945  130.81
 4985.63  119.04 4993.93  114.95 4999.43  114.82 5004.62  114.45 5010.71  114.84
 5012.54  115.03 5024.67  119.72 5056.53  129.79 5061.41  130.98 5065.92  133.49
    5070  133.57  5070.6  133.59 5087.07  133.92  5096.4  134.28  5107.6  132.86
  5154.6  132.88  5260.7  133.27  5323.3   134.6    5324  135.25  5335.7  135.76
  5345.7  136.16  5365.7  136.36  5375.7  136.56  5385.7  136.56  5399.7  136.67
  5435.7  136.96  5445.7  137.06  5485.7  137.16  5488.4  137.17  5525.7  137.36
  5535.7  136.96  5555.7  137.06  5575.7  136.66  5578.4  136.71  5595.7  137.06
  5598.4  137.05  5615.7  136.96  5635.7  137.26  5655.7  137.16  5665.7  137.46
  5685.7  137.66  5692.4  137.53  5695.7  137.46  5722.4  137.99  5725.7  138.06
  5735.7  138.06  5755.7  138.26  5765.7  137.86  5782.4  137.78  5785.7  137.76
  5805.7  136.86  5835.7  136.46  5852.4  136.79  5855.7  136.86  5915.7  136.86
  5955.7  138.06  5962.4  137.93  5965.7  137.86  5975.7  137.16  5982.4  136.83
  5985.7  136.66  6015.7  136.66  6025.7  136.36  6035.7  136.46  6105.7  135.96
  6175.7  136.16  6305.7  136.16  6322.4  136.08  6325.7  136.06  6385.7  136.46
  6395.7  136.36  6402.4  136.49  6405.7  136.56  6482.4  136.94  6485.7  136.96
  6515.7  136.46  6525.7  136.56  6545.7  136.26  6615.7  136.36  6750.5  135.86
  6750.6  135.86
BR D #Mann= 9
  1835.7      .2  1848.4    .065  1848.9     .05    3042     .08  4770.9     .03
    4945    .025    5070     .03  5070.6     .03  5399.7      .1
BC Design=,, 0 ,, 0 ,,,,,,
BC HTab HWMax=139.51
BC Use User HTab Curves=0
BC User HTab FreeFlow(D)= 0

Type RM Length L Ch R = 1 ,7529.1  ,129.3,178.7,233.9
BEGIN DESCRIPTION:
Downstream Section of Bridge/Culvert/Weir; updated with survey
END DESCRIPTION:
XS GIS Cut Line= 3
     3037373.258     13920598.33       3034733.8     13917786.66
     3034009.976     13917020.21
#Sta/Elev= 30
  1835.7  139.16  1848.4  139.03  1848.9  139.03  2285.7  135.36    3042  134.19
  3445.7  132.36  3975.7  132.16  4175.7  128.86  4335.7  132.06  4565.7  130.86
  4770.9   131.7    4945  133.66    4967  126.91  4998.9  113.54  5003.6     114
  5013.6  119.14  5051.2  130.45    5070  134.74  5070.6  134.88  5107.6  132.86
  5260.7  133.27  5345.7  136.16  5435.7  136.96  5755.7  138.26  5835.7  136.46
  5955.7  138.06  5985.7  136.66  6105.7  135.96  6485.7  136.96  6750.6  135.86
#Mann= 9 ,-1 , 0
  1835.7      .2       0  1848.4    .065       0  1848.9     .05       0
    3042     .08       0  4770.9    .095       0    4945     .08       0
    5070    .095       0  5070.6     .03       0  5435.7      .1       0
#XS Ineff= 2 , 0
       0    4911   133.1    5073       0   133.4
Permanent Ineff=
       F       F
#Block Obstruct= 2 , 0
       0                    5900       0     137
Bank Sta=4945,5070
XS Rating Curve= 0 ,0
Exp/Cntr=0.5,0.3

Type RM Length L Ch R = 1 ,7350.4  ,416.7,586.7,346.3
BEGIN DESCRIPTION:
Cross Section XS09
END DESCRIPTION:
XS GIS Cut Line= 4
    3037285.5364   13920316.9284    3035400.2483   13918311.1246
    3035371.8951   13918169.3589    3034852.3082   13917628.5643
#Sta/Elev= 30
  2185.5     138  2575.5   136.1  2915.5   138.1  3065.5   137.8  3325.5   134.3
  3575.5   132.7  3855.5   133.2  3885.5   134.3  3975.5   132.4  4195.5   132.2
  4285.5   130.2  4345.5   129.4  4585.5   132.4  4770.9  131.55    4945  132.51
  4965.5  125.71  4976.4  123.24  4981.1  118.01  4992.5  116.51  4994.3  114.97
  4998.9  114.09  5010.6  116.39  5036.3  127.65  5046.6  126.52    5070  131.51
  5153.5  132.73  5260.7  133.12    5324   135.1  5402.8   135.8  5832.8   137.9
#Mann= 6 ,-1 , 0
  2185.5     .05       0  3575.5     .08       0  4285.5    .095       0
    4945     .08       0    5070    .095       0  5153.5     .03       0
#XS Ineff= 2 ,-1
    2150    2915   138.1    2915    4914   132.9
Permanent Ineff=
       F       F
Bank Sta=4945,5070
XS Rating Curve= 0 ,0
Exp/Cntr=0.3,0.1