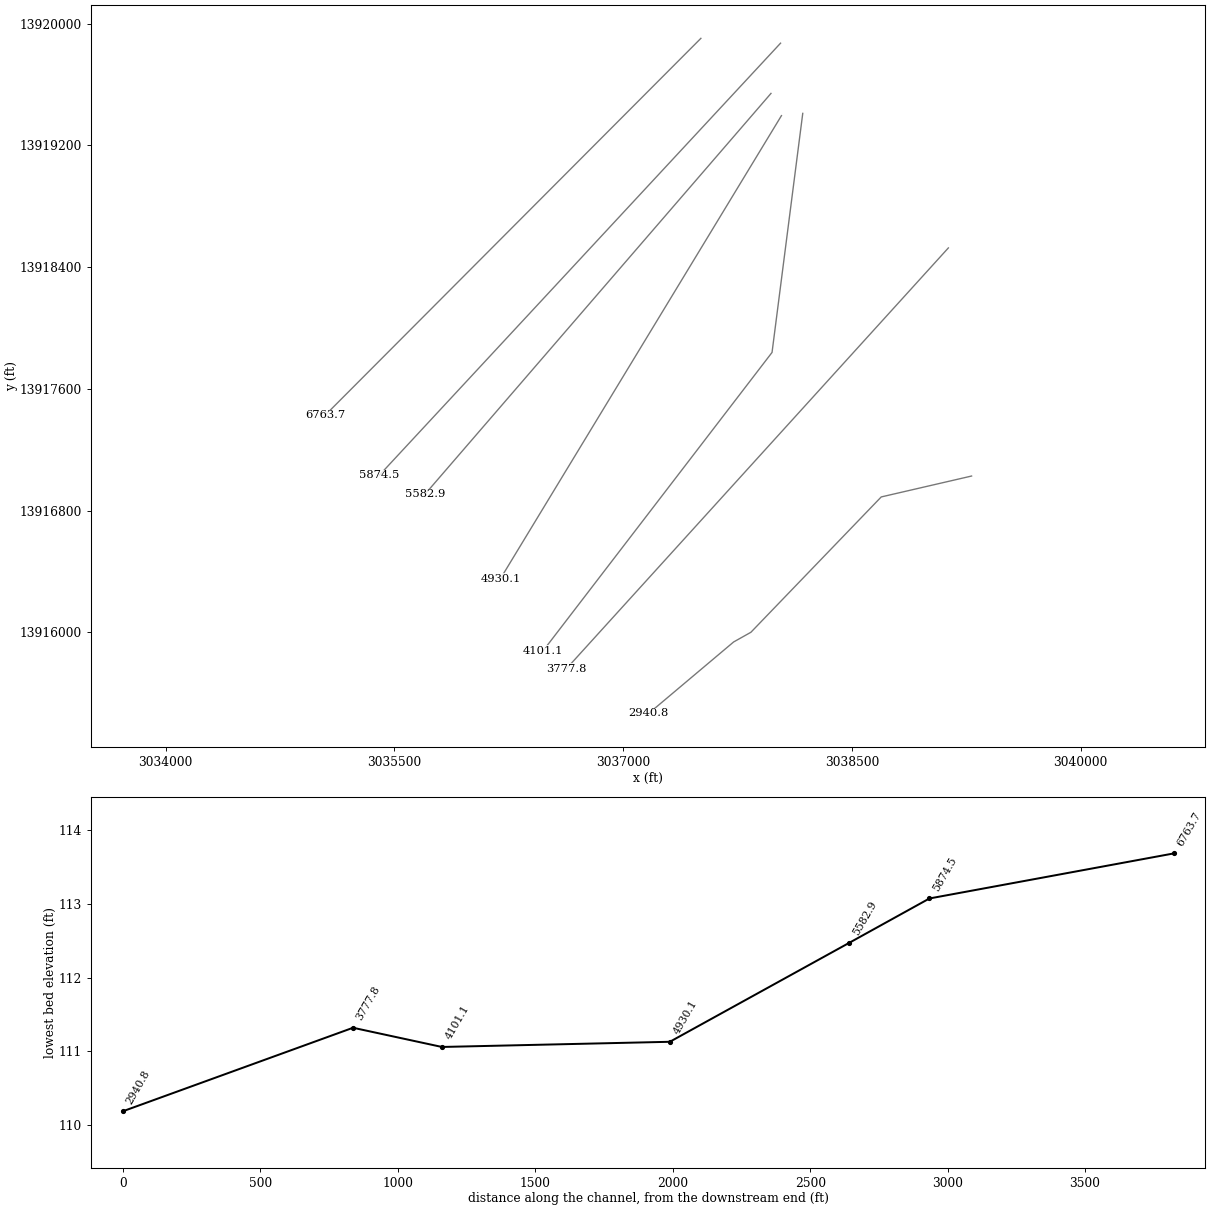
HEC-RAS study L100-00-00.prj: L100-00-00

--- L100-00-00.g01 (geometry) --- (continued)

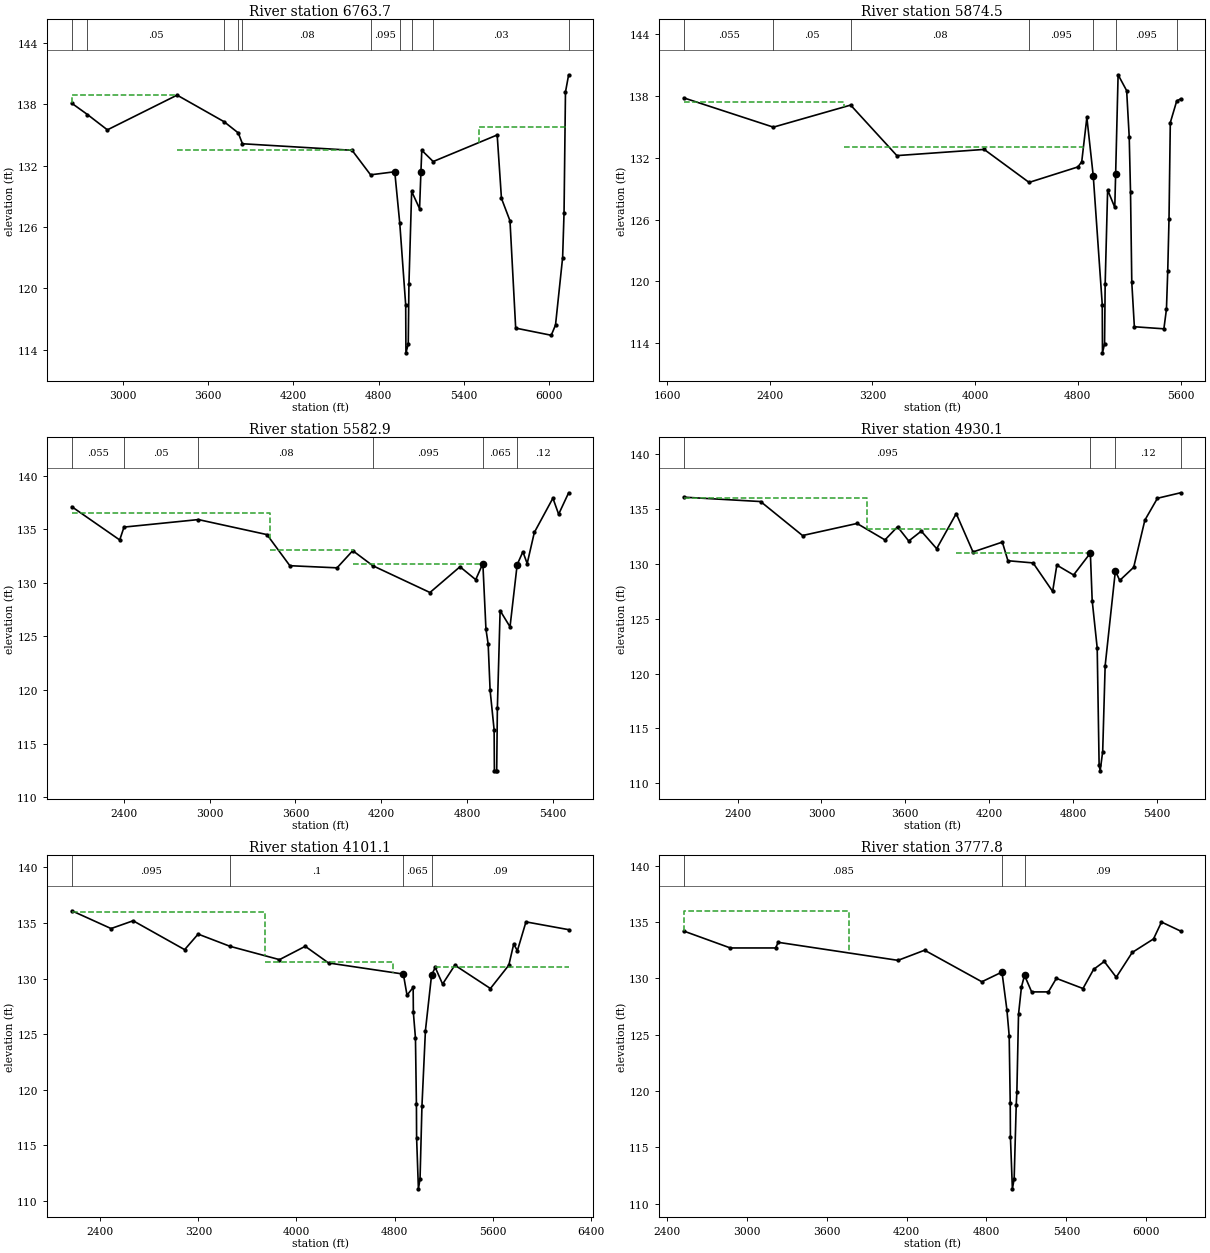
Type RM Length L Ch R = 1 ,6763.7  ,498.2,889.2,668.3
BEGIN DESCRIPTION:
Cross Section XS08
END DESCRIPTION:
XS GIS Cut Line= 2
    3037509.0276   13919903.8083    3035046.0826   13917427.9421
#Sta/Elev= 30
  2643.2   138.1  2753.2     137  2893.2   135.5  3383.2   138.9  3713.2   136.3
  3813.2   135.2  3842.5  134.14  4613.2   133.5  4743.2   131.1  4913.2   131.4
  4948.5  126.35  4990.1  118.36  4991.8  113.68  5008.1  114.54  5012.8  120.37
    5032  129.48  5087.6  127.79 5097.06  131.36  5103.2   133.5  5183.2   132.4
  5633.2     135  5663.2   128.8  5723.2   126.6  5763.2   116.1  6013.2   115.4
  6043.2   116.4  6093.2     123  6103.2   127.4  6113.2   139.2  6135.5  140.89
#Mann= 10 ,-1 , 0
  2643.2    .055       0  2753.2     .05       0  3713.2     .08       0
  3813.2     .05       0  3842.5     .08       0  4743.2    .095       0
  4948.5    .065       0    5032    .095       0  5183.2     .03       0
  6135.5     .12       0
#XS Ineff= 3 ,-1
  2643.2    3383   138.9    3383    4615   133.5    5504    6125   135.8
Permanent Ineff=
       F       F       T
Bank Sta=4913.2,5097.06
XS Rating Curve= 0 ,0
Exp/Cntr=0.3,0.1

Type RM Length L Ch R = 1 ,5874.5  ,277.3,291.6,311
BEGIN DESCRIPTION:
Cross Section XS07
END DESCRIPTION:
XS GIS Cut Line= 2
    3038031.4765   13919872.1375    3035401.1396   13917033.4042
#Sta/Elev= 30
  1730.2   137.8  2428.3  134.96  3030.2   137.1  3390.2   132.2  4070.2   132.8
  4420.2   129.6  4800.2   131.1  4830.2   131.6  4870.2   135.9  4920.2   130.2
  4990.1  117.75  4991.8  113.07  5008.1  113.93  5012.8  119.76    5032  128.87
  5087.6  127.18 5094.34  130.38  5113.6  140.04  5180.2   138.5  5200.2     134
  5210.2   128.7  5220.2   119.9  5240.2   115.6  5470.2   115.4  5490.2   117.3
  5500.2     121  5510.2   126.1  5520.2   135.4  5570.2   137.5  5600.2   137.7
#Mann= 7 ,-1 , 0
  1730.2    .055       0  2428.3     .05       0  3030.2     .08       0
  4420.2    .095       0  4920.2    .065       0 5094.34    .095       0
  5570.2     .12       0
#XS Ineff= 3 ,-1
  1730.2    2977   137.4    2977    4840     133    5180    5600   135.8
Permanent Ineff=
       F       F       T
Bank Sta=4920.2,5094.34
XS Rating Curve= 0 ,0
Exp/Cntr=0.3,0.1

Type RM Length L Ch R = 1 ,5582.9  ,559.9,652.8,725.3
BEGIN DESCRIPTION:
Cross Section XS06
END DESCRIPTION:
XS GIS Cut Line= 2
    3037968.6338   13919542.0116    3035700.7252   13916909.0824
#Sta/Elev= 30
  2036.3   137.1  2371.3     134  2401.3   135.2  2921.3   135.9  3401.3   134.5
  3561.3   131.6  3891.3   131.4  4001.3     133  4141.3   131.6  4541.3   129.1
  4751.3   131.5  4861.3   130.3  4911.3   131.8  4932.9  125.68  4948.5  124.28
    4962  119.98  4990.1  116.29  4991.9  112.49  5002.3  112.47  5008.1  112.47
  5012.8   118.3    5032  127.41  5101.3   125.9  5151.3   131.7  5191.3   132.9
  5221.3   131.8  5271.3   134.7  5401.3   137.9  5441.3   136.4  5511.3   138.4
#Mann= 6 ,-1 , 0
  2036.3    .055       0  2401.3     .05       0  2921.3     .08       0
  4141.3    .095       0  4911.3    .065       0  5151.3     .12       0
#XS Ineff= 3 ,-1
  2036.3    3425   136.5    3425    4000   133.1    4000    4906   131.8
Permanent Ineff=
       F       F       F
Bank Sta=4911.3,5151.3
XS Rating Curve= 0 ,0
Exp/Cntr=0.3,0.1

Type RM Length L Ch R = 1 ,4930.1  ,704.7,829,586.9
BEGIN DESCRIPTION:
Cross Section XS05
END DESCRIPTION:
XS GIS Cut Line= 2
    3038037.2796   13919395.8737    3036195.3635   13916354.5322
#Sta/Elev= 30
    2015   136.1    2565   135.7    2865   132.6    3255   133.7    3455   132.2
    3545   133.4    3625   132.1    3715     133    3825   131.4    3965   134.6
    4085   131.1    4295     132    4335   130.3    4515   130.1    4655   127.5
    4685   129.9    4805     129    4925     131    4938  126.67  4973.9  122.34
  4987.7  111.64  4995.2  111.13  5013.2  112.89  5030.8  120.72    5104  129.38
    5135   128.5    5235   129.7    5315     134    5405     136  5570.6   136.5
#Mann= 4 ,-1 , 0
    2015    .095       0    4925    .065       0    5104     .12       0
  5570.6      .2       0
#XS Ineff= 3 ,-1
    2000    3325     136    3325    3960   133.2    3960    4920     131
Permanent Ineff=
       F       F       F
Bank Sta=4925,5104
XS Rating Curve= 0 ,0
Exp/Cntr=0.3,0.1

Type RM Length L Ch R = 1 ,4101.1  ,340.7,323.3,311
BEGIN DESCRIPTION:
Cross Section XS4.5
END DESCRIPTION:
XS GIS Cut Line= 3
    3038176.9526   13919410.8246    3037975.5716   13917840.0527
    3036475.2087   13915880.5748
#Sta/Elev= 30
  2168.3   136.1  2488.3   134.5  2668.3   135.2  3088.3   132.6  3198.3     134
  3458.3   132.9  3861.9   131.7  4071.9   132.9  4261.9   131.4  4871.9   130.4
  4901.9   128.5  4951.9   129.2  4953.6  126.94  4970.7  124.64  4978.5  118.67
    4980  115.68  4994.7  111.06    5008  111.94  5023.7  118.54  5051.9   125.3
  5101.9   130.3  5131.9     131  5191.9   129.5  5291.9   131.2  5581.9   129.1
  5731.9   131.2  5771.9   133.1  5801.9   132.5  5871.9   135.1  6219.9   134.4
#Mann= 4 ,-1 , 0
  2168.3    .095       0  3458.3      .1       0  4871.9    .065       0
  5101.9     .09       0
#XS Ineff= 3 ,-1
    2100    3745     136    3745    4791   131.5    5132    6300     131
Permanent Ineff=
       F       F       F
Bank Sta=4871.9,5101.9
XS Rating Curve= 0 ,0
Exp/Cntr=0.3,0.1

Type RM Length L Ch R = 1 ,3777.8  ,769,837,707.8
BEGIN DESCRIPTION:
Cross Section XS04
END DESCRIPTION:
XS GIS Cut Line= 2
    3039131.6679   13918526.7229    3036625.4163    13915759.681
#Sta/Elev= 30
  2525.2   134.2  2875.2   132.7  3215.2   132.7  3235.2   133.2  4135.2   131.6
  4335.2   132.5  4765.2   129.7  4916.5  130.56  4953.6   127.2  4970.7   124.9
  4978.5  118.93    4980  115.94  4994.7  111.32    5008   112.2  5023.7   118.8
  5028.4  119.92  5040.8   126.8  5062.9  129.24    5086  130.27  5139.4   128.8
  5265.2   128.8  5325.2     130  5525.2   129.1  5605.2   130.8  5685.2   131.5
  5775.2   130.1  5895.2   132.3  6055.2   133.5  6115.2     135  6258.6   134.2
#Mann= 3 ,-1 , 0
  2525.2    .085       0  4916.5    .065       0    5086     .09       0
#XS Ineff= 2 , 0
       0    3770     136    5086       0   130.2
Permanent Ineff=
       F       F
Bank Sta=4916.5,5086
XS Rating Curve= 0 ,0
Exp/Cntr=0.3,0.1

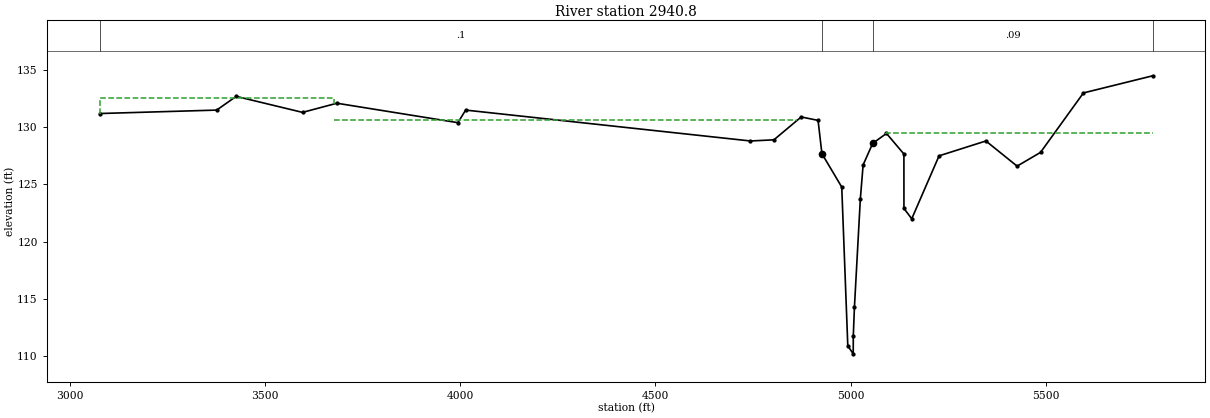
Type RM Length L Ch R = 1 ,2940.8  ,752.3,816.6,750.9
BEGIN DESCRIPTION:
Cross Section XS03
END DESCRIPTION:
XS GIS Cut Line= 5
    3039283.8972   13917027.9151    3038691.5083   13916890.5795
    3037837.0377   13916001.3975    3037723.6251    13915937.603
    3037167.3625   13915468.4558
#Sta/Elev= 30
  3075.5   131.2  3375.5   131.5  3425.5   132.7  3595.5   131.3  3683.6   132.1
  3993.6   130.4  4013.6   131.5  4743.6   128.8  4803.6   128.9  4873.6   130.9
  4916.8   130.6  4926.7  127.69  4977.5  124.77    4993  110.89  5006.9  110.19
  5007.1  111.76    5010  114.27  5025.2  123.76  5032.3  126.71  5056.8  128.59
  5092.1  129.46  5136.8  127.66  5136.9   122.9  5156.9     122  5226.9   127.5
  5346.9   128.8  5426.9   126.6  5486.9   127.8  5596.9     133  5774.6   134.5
#Mann= 4 ,-1 , 0
  3075.5      .1       0  4926.7    .065       0  5056.8     .09       0
  5774.6      .2       0
#XS Ineff= 3 ,-1
    3000    3675   132.6    3675    4860   130.6    5091    5800   129.5
Permanent Ineff=
       F       F       F
Bank Sta=4926.7,5056.8
XS Rating Curve= 0 ,0
Exp/Cntr=0.3,0.1