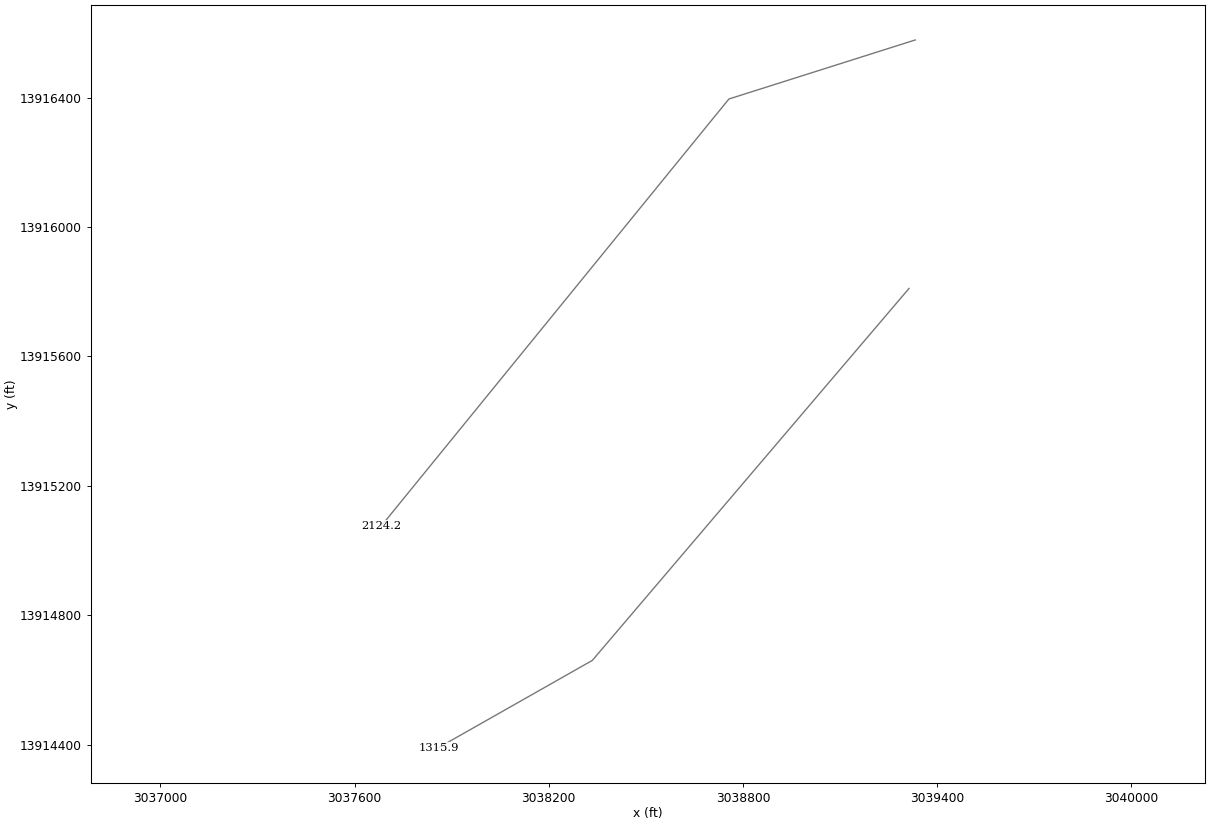
HEC-RAS study L100-00-00.prj: L100-00-00

--- L100-00-00.g01 (geometry) --- (continued)

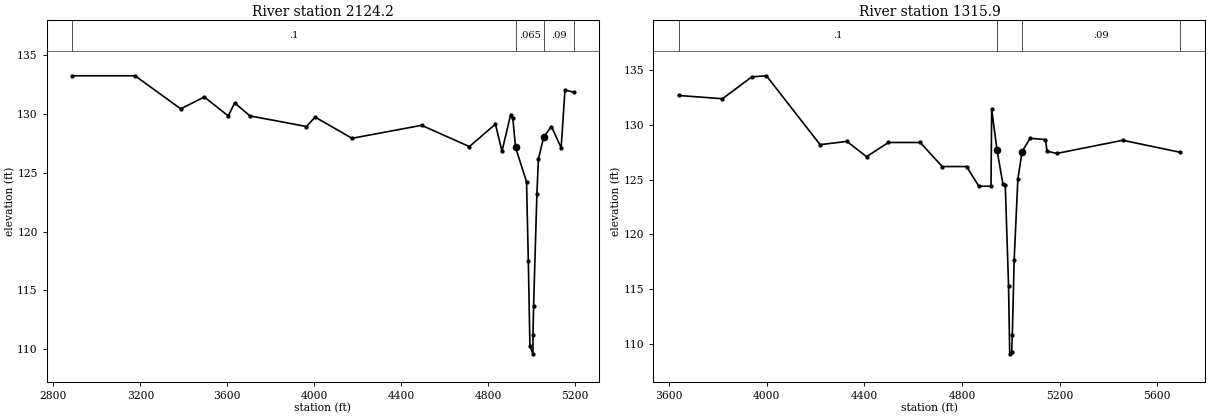
Type RM Length L Ch R = 1 ,2124.2  ,819.1,808.3,728.9
BEGIN DESCRIPTION:
Cross Section XS02
END DESCRIPTION:
XS GIS Cut Line= 3
      3039332.53      13916577.8    3038756.7864   13916395.3734
    3037682.8979   13915076.4341
#Sta/Elev= 30
  2885.8   133.2  3175.8   133.2  3385.8   130.4  3494.4   131.4  3604.4   129.8
  3634.4   130.9  3704.4   129.8  3964.4   128.9  4004.4   129.7  4174.4   127.9
  4494.4     129  4714.4   127.2  4834.4   129.1  4864.4   126.8  4904.4   129.9
  4914.4   129.6  4926.8  127.13  4977.5  124.21  4985.7  117.52    4993  110.33
  5006.9  109.63  5007.1   111.2    5010  113.71  5025.2   123.2  5032.3  126.15
  5056.8  128.03  5092.1   128.9  5136.8   127.1  5154.4     132  5195.3   131.8
#Mann= 4 ,-1 , 0
  2885.8      .1       0  4926.8    .065       0  5056.8     .09       0
  5195.3      .2       0
#XS Ineff= 2 , 0
       0    4905   129.8               0
Permanent Ineff=
       F       F
Bank Sta=4926.8,5056.8
XS Rating Curve= 0 ,0
Exp/Cntr=0.3,0.1

Type RM Length L Ch R = 1 ,1315.9  ,0,0,0
BEGIN DESCRIPTION:
Cross Section XS01
END DESCRIPTION:
XS GIS Cut Line= 3
    3039313.3661   13915810.0369     3038334.798   13914660.6582
    3037859.8829   13914391.3034
#Sta/Elev= 30
  3639.3   132.7  3819.3   132.4  3939.3   134.4  3999.3   134.5  4219.3   128.2
  4329.3   128.5  4409.3   127.1  4499.3   128.4  4629.3   128.4  4719.3   126.2
  4819.3   126.2  4869.3   124.4  4919.3   124.4  4922.1  131.43    4944  127.68
    4968  124.62  4977.7  124.54  4991.1  115.31  4995.9  109.07  5003.9  109.23
  5006.6  110.81  5014.2  117.69  5029.3  125.05  5046.7  127.57  5079.4  128.78
  5142.3  128.67  5148.8   127.6  5188.8   127.4  5458.8   128.6  5694.8   127.5
#Mann= 4 ,-1 , 0
  3639.3      .1       0    4944    .065       0  5046.7     .09       0
  5694.8      .2       0
Bank Sta=4944,5046.7
XS Rating Curve= 0 ,0
Exp/Cntr=0.3,0.1

Chan Stop Cuts=-1
Use User Specified Reach Order=0
Composite Channel Slope=5